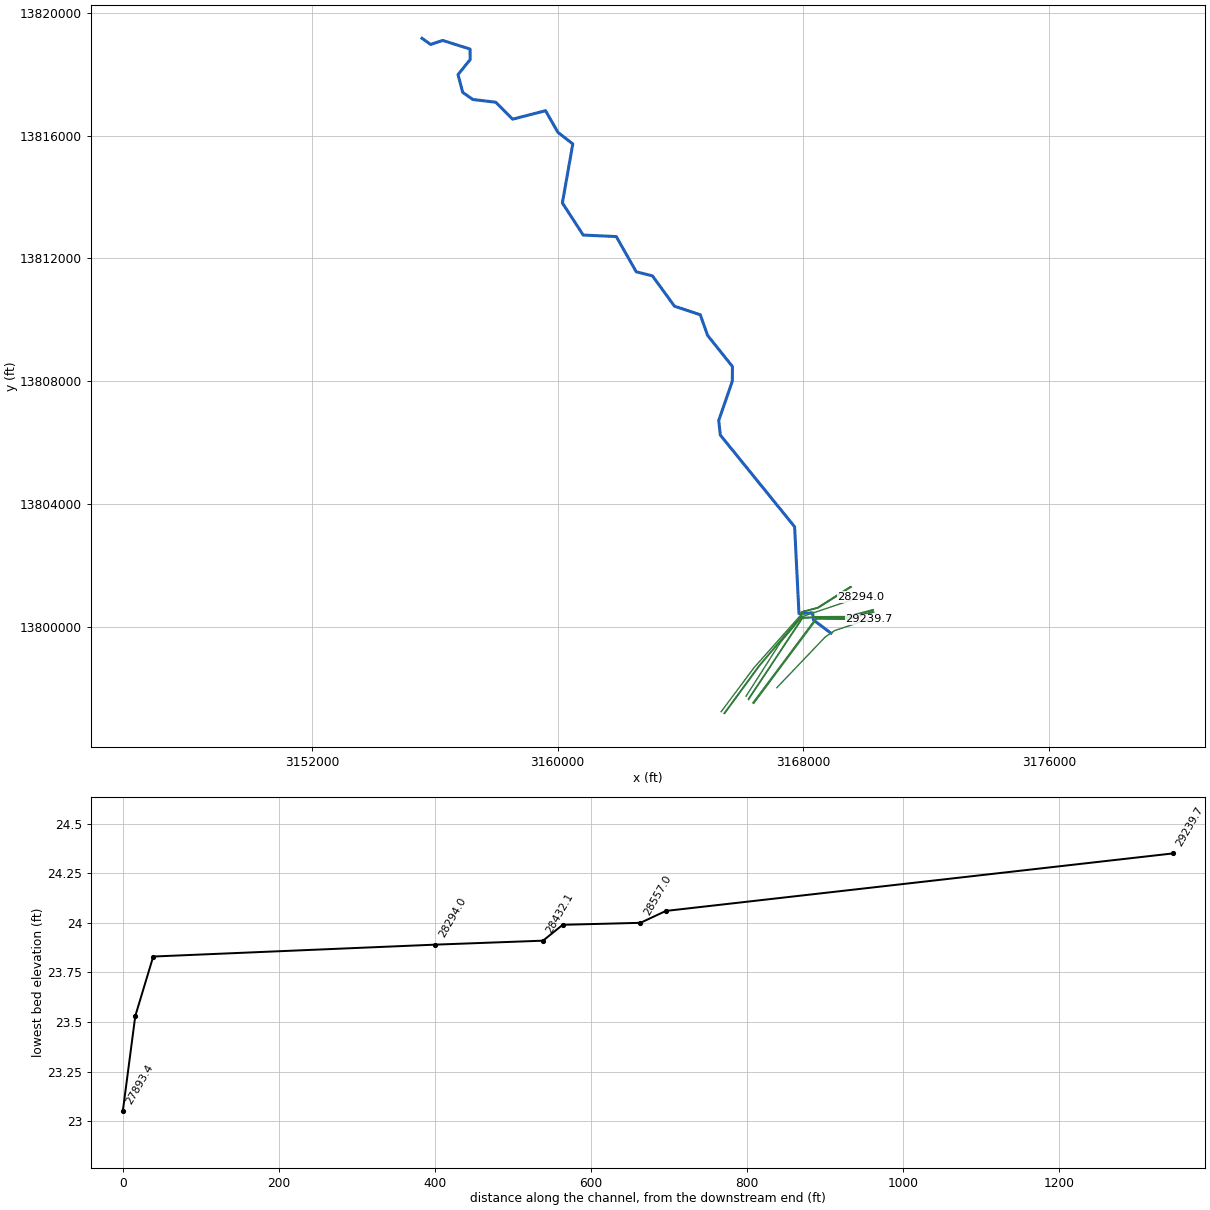
--- C106-00-00.PRJ (project) ---

Proj Title=C106-00-00 2015
Current Plan=p01
Default Exp/Contr=0.3,0.1
English Units
Geom File=g01
Flow File=f01
Flow File=f02
Plan File=p01
Plan File=p02
Y Axis Title=Elevation
X Axis Title(PF)=Main Channel Distance
X Axis Title(XS)=Station
BEGIN DESCRIPTION:
Sims Bayou Watershed
Berry Bayou
HCFCD Unit C106-00-00
Flood Hazard Model
10, 2, 1, 0.2% Event
Filename C106-00-00.prj
Prepared by:  Watershed Concepts  Date:
Reviewed by:                      Date:
STATUS FINAL
END DESCRIPTION:
DSS File=dss
DSS Export Rating Curves= 0
DSS Export Rating Curve Sorted= 0
DSS Export Volume Flow Curves= 0
DXF OffsetX= 0
DXF OffsetY= 0
DXF ScaleX= 1
DXF ScaleY= 10

--- C106-00-00.p01 (plan) ---

Plan Title=Effective Multi-Profile 2015
Program Version=4.10
Short Identifier=Eff+RiskMAP MP
Geom File=g01
Flow File=f01
Subcritical Flow
K Sum by GR= 0
Std Step Tol= 0.01
Critical Tol= 0.01
Num of Std Step Trials= 20
Max Error Tol= 0.3
Flow Tol Ratio= 0.001
Split Flow NTrial= 30
Split Flow Tol= 0.02
Split Flow Ratio= 0.02
Log Output Level= 0
Friction Slope Method= 1
Unsteady Friction Slope Method= 2
Unsteady Bridges Friction Slope Method= 1
Parabolic Critical Depth
Global Vel Dist= 0 , 0 , 0
Global Log Level= 0
CheckData=True
Encroach Param=-1 ,0,0, 0
Computation Interval=1HOUR
Output Interval=1HOUR
Run HTab= 0
Run UNet= 0
Run PostProcess= 0
Run WQNet= 0
UNET Theta= 1
UNET Theta Warmup= 1
UNET ZTol= 0.02
UNET ZSATol= 0.05
UNET MxIter= 20
UNET MaxInSteps= 0
UNET DtIC= 0
UNET DtMin= 0
UNET MaxCRTS= 20
UNET WFStab= 2
UNET SFStab= 1
UNET WFX= 1
UNET SFX= 1
UNET DSS MLevel= 4
UNET DZMax Abort= 100
UNET Convert EG Bridges=-1
UNET Use Existing IB Tables=-1
UNET Froude Reduction=False
UNET Froude Limit= 1
UNET Froude Power= 10
UNET Time Slicing=0,0, 5
UNET Junction Losses=0
Instantaneous Interval=1HOUR
Write IC File= 0
IC Time=0,,
Write IC File at Sim End=0
Echo Input=False
Echo Parameters=False
Echo Output=False
Write Detailed= 0
WQ AD Non Conservative
WQ ULTIMATE=-1
WQ Max Comp Step=1HOUR
WQ Output Interval=15MIN
WQ Output Selected Increments= 0
WQ Output face flow=0
WQ Output face velocity=0
WQ Output face area=0
WQ Output face dispersion=0
WQ Output cell volume=0
WQ Output cell surface area=0
WQ Output cell continuity=0
WQ Output cumulative cell continuity=0
WQ Output face conc=0
WQ Output face dconc_dx=0
WQ Output face courant=0
WQ Output face peclet=0
WQ Output face adv mass=0
WQ Output face disp mass=0
WQ Output cell mass=0
WQ Output cell source sink temp=0
WQ Output cell source sink nsm=0
WQ Output MaxMinRange=-1
WQ Daily Max Min Mean=-1
WQ Daily Range=0
WQ Daily Time=0
WQ Create Restart=0
WQ Fixed Restart=0
WQ System Summary=0
WQ Use Fixed Temperature=0
Sorting and Armoring Iterations= 10
XS Update Threshold= 0.02
Hydraulics Update Threshold= 0.02
Energy Slope Method= 1
Volume Change Method= 0
XS Weighting Method= 0
Number of US Weighted Cross Sections= 1
Number of DS Weighted Cross Sections= 1
Upstream XS Weight=0.25
Main XS Weight=0.5
Downstream XS Weight=0.25
Number of DS XS's Weighted with US Boundary= 1
Upstream Boundary Weight= 1
Weight of XSs Associated with US Boundary= 0
Number of US XS's Weighted with DS Boundary= 1
Downstream Boundary Weight= 0.5
Weight of XSs Associated with DS Boundary= 0.5
Sediment Output Level= 4
Mass or Volume Output= 0
Output Increment Type= 1
Profile and TS Output Increment= 10
XS Output Flag= 0
XS Output Increment= 10
Disregard all LS=0
Disregard all Conn=0
Disregard all Breaches=0
Disregard all Pumps=0

--- C106-00-00.p02 (plan) ---

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Plan Title=Effective Floodway 2015
Short Identifier=Eff+RiskMAP FW
Geom File=g01
Flow File=f02
Encroach Param=-1 ,0,0, 2
Encroach River=C106-00-00
Encroach Reach=C106-00-00_0003
Encroach Node=29239.7
       1    4800    5150
Encroach Node=28589.6
       1    4800    5200
Encroach Node=28557.0
       1    4800    5200
Encroach Node=28457.3
       1    4800    5200
Encroach Node=28432.1
       1    4800    5200
Encroach Node=28294.0
       1    4630    5150
Encroach Node=27932.4
       1    4875    5032
Encroach Node=27909.4
       1    4875    5032
Encroach Node=27893.4
       1    4930    5025
Encroach Node=27870.4
       1    4930    5025
Encroach Node=27716.7
       1    4950    5030
Encroach Node=27615.0
       1    4775    5200
Encroach Node=27562.0
       1    4775    5200
Encroach Node=26999.9
       1    4785    5200
Encroach Node=26536.2
       1    4775    5200
Encroach Node=26418.2
       1    4775    5200
Encroach Node=26033.3
       1    4800    5200
Encroach Node=25286.3
       1    4800    5060
Encroach Node=24222.6
       1    4800  5058.4
Encroach Node=24131.8
       1    4800    5024
Encroach Node=24097.4
       1    4800    5024
Encroach Node=23940.1
       1    4800  5030.8
Encroach Node=23755.5
       1    4800  5030.8
Encroach Node=23725.0
       1    4920  5030.8
Encroach Node=23655.0
       1    4920  5030.8
Encroach Node=23579.7
       1    4920    5050
Encroach Node=23488.7
       1    4920    5050
Encroach Node=23291.9
       1    4950    5050
Encroach Node=22341.4
       1    4950    5050
Encroach Node=22215.8
       1    4940    5050
Encroach Node=22153.8
       1    4940    5050
Encroach Node=21918.7
       1    4950    5045
Encroach Node=21050.3
       1    4958    5044
Encroach Node=21014.3
       1    4958    5044
Encroach Node=20616.4
       1    4940 5039.68
Encroach Node=20295.6
       1    4951 5039.68
Encroach Node=20111.0
       1    4956 5034.54
Encroach Node=20059.0
       1    4956 5034.54
Encroach Node=19789.7
       1    4948 5043.69
Encroach Node=19028.6
       1 4958.49 5043.69
Encroach Node=18982.7
       1 4958.49 5043.69
Encroach Node=18961.7
       1 4958.49 5043.69
Encroach Node=18858.7
       1  4954.8  5065.1
Encroach Node=18742.7
       1  4954.8  5065.1
Encroach Node=18227.8
       1  4932.4  5070.1
Encroach Node=18031.3
       1  4932.4  5070.1
Encroach Node=17973.1
       1  4932.4  5070.1
Encroach Node=17169.8
       1  4941.8  5046.3
Encroach Node=16644.4
       1 4944.17 5078.97
Encroach Node=16456.9
       1 4944.17 5078.97
Encroach Node=16434.9
       1 4944.17 5078.97
Encroach Node=16416.9
       1  4944.3    5079
Encroach Node=16358.9
       1  4944.3    5079
Encroach Node=15961.0
       1  4954.3  5063.6
Encroach Node=15277.0
       1    4902 5077.88
Encroach Node=14992.8
       1  4919.4  5077.9
Encroach Node=14920.8
       1  4919.4  5077.9
Encroach Node=13835.3
       1  4919.7  5078.3
Encroach Node=13007.2
       1  4913.9  5073.8
Encroach Node=11965.1
       1    4918  5076.6
Encroach Node=11862.3
       1    4918  5066.4
Encroach Node=11789.3
       1    4918  5066.4
Encroach Node=11271.4
       1  4911.6  5081.5
Encroach Node=10683.0
       1  4923.2  5077.4
Encroach Node=10270.0
       1  4905.8  5077.4
Encroach Node=9880.2
       1  4923.2  5077.4
Encroach Node=9202.4
       1 4898.67 5070.77
Encroach Node=8982.1
       1  4898.7  5070.8
Encroach Node=8877.7
       1  4898.7  5070.8
Encroach Node=8475.5
       1  4904.7 5050.38
Encroach Node=7825.3
       1 4915.28 5050.38
Encroach Node=7801.3
       1 4915.28 5050.38
Encroach Node=7488.3
       1  4919.7  5058.9
Encroach Node=7324.2
       1  4923.9  5069.9
Encroach Node=7250.2
       1  4923.9  5069.9
Encroach Node=6769.7
       1    4900    5115
Encroach Node=5788.7
       1 4875.44  5139.4
Encroach Node=5579.9
       1    4895    5100
Encroach Node=5484.9
       1    4895    5100
Encroach Node=4596.0
       1    4850    5180
Encroach Node=3503.4
       1    4900    5180
Encroach Node=2097.3
       1    4850    5160
Encroach Node=1126.7
       1    4850    5100
Encroach Node=1103.5
       1    4850    5100
Encroach Node=297.6
       1  4858.3    5072
BEGIN DESCRIPTION:
FEMA Effective Risk Map Study Floodway May 02, 2019
END DESCRIPTION:
UNET ZSATol= 0.1
UNET MaxInSteps= 20
DSS File=dss

--- C106-00-00.f01 (steady flow) ---

Flow Title=Effective Multi-Profile 2015
Program Version=4.10
Number of Profiles= 6
Profile Names=10PCT_10yr,4PCT_25yr,2PCT_50yr,1PCT_100yr,1PCT_Plus,0.2PCT_500yr
River Rch & RM=C106-00-00,C106-00-00_0003 ,29239.7
     756     949    1126    1321    1585    1893
River Rch & RM=C106-00-00,C106-00-00_0003 ,27920.9
     807    1013    1203    1411    1693    2022
River Rch & RM=C106-00-00,C106-00-00_0003 ,26477.2
     979    1229    1460    1711    2054    2453
River Rch & RM=C106-00-00,C106-00-00_0003 ,24114.6
    1090    1368    1625    1905    2286    2731
River Rch & RM=C106-00-00,C106-00-00_0003 ,23534.2
    1123    1410    1675    1964    2357    2814
River Rch & RM=C106-00-00,C106-00-00_0003 ,21050.3
    1279    1606    1907    2238    2685    3206
River Rch & RM=C106-00-00,C106-00-00_0003 ,21032.3
    2260    2826    3346    3914    4697    5563
River Rch & RM=C106-00-00,C106-00-00_0003 ,20085
    2505    3130    3705    4331    5197    6151
River Rch & RM=C106-00-00,C106-00-00_0003 ,18972.2
    2827    3530    4177    4878    5853    6920
River Rch & RM=C106-00-00,C106-00-00_0003 ,18800.7
    2880    3596    4254    4968    5962    7047
River Rch & RM=C106-00-00,C106-00-00_0003 ,18002.2
    3141    3921    4636    5410    6492    7670
River Rch & RM=C106-00-00,C106-00-00_0003 ,16445.9
    3721    4217    4636    6389    7667    9044
River Rch & RM=C106-00-00,C106-00-00_0003 ,14956.8
    4374    5449    6435    7491    8989   10590
River Rch & RM=C106-00-00,C106-00-00_0003 ,13835.3
    4942    6152    7260    8444   10133   11926
River Rch & RM=C106-00-00,C106-00-00_0003 ,11825.8
    5427    6763    7987    9266   11120   13097
River Rch & RM=C106-00-00,C106-00-00_0003 ,8929.9
    6212    7751    9164   10594   12713   14988
River Rch & RM=C106-00-00,C106-00-00_0003 ,7825.3
    6540    8165    9658   11149   13379   15779
River Rch & RM=C106-00-00,C106-00-00_0003 ,7287.2
    6635    8287    9804   11322   13587   16000
River Rch & RM=C106-00-00,C106-00-00_0003 ,1115.1
    7834    9819   11648   13518   16221   18771
Boundary for River Rch & Prof#=C106-00-00,C106-00-00_0003 , 1
Up Type= 0
Dn Type= 3
Dn Slope=0.0002
Boundary for River Rch & Prof#=C106-00-00,C106-00-00_0003 , 2
Up Type= 0
Dn Type= 3
Dn Slope=0.0002
Boundary for River Rch & Prof#=C106-00-00,C106-00-00_0003 , 3
Up Type= 0
Dn Type= 3
Dn Slope=0.0002
Boundary for River Rch & Prof#=C106-00-00,C106-00-00_0003 , 4
Up Type= 0
Dn Type= 3
Dn Slope=0.0002
DSS Import GetInterval= 0
DSS Import GetPeak= 0
DSS Import FillOption= 0

--- C106-00-00.f02 (steady flow) ---

Flow Title=Effective Floodway 2015
Program Version=4.10
Number of Profiles= 2
Profile Names=1PCT_100yr,Floodway
River Rch & RM=C106-00-00,C106-00-00_0003 ,29239.7
    1321    1321
River Rch & RM=C106-00-00,C106-00-00_0003 ,27920.9
    1411    1411
River Rch & RM=C106-00-00,C106-00-00_0003 ,26477.2
    1711    1711
River Rch & RM=C106-00-00,C106-00-00_0003 ,24114.6
    1905    1905
River Rch & RM=C106-00-00,C106-00-00_0003 ,23534.2
    1964    1964
River Rch & RM=C106-00-00,C106-00-00_0003 ,21050.3
    2238    2238
River Rch & RM=C106-00-00,C106-00-00_0003 ,21032.3
    3914    3914
River Rch & RM=C106-00-00,C106-00-00_0003 ,20085
    4331    4331
River Rch & RM=C106-00-00,C106-00-00_0003 ,18972.2
    4878    4878
River Rch & RM=C106-00-00,C106-00-00_0003 ,18800.7
    4968    4968
River Rch & RM=C106-00-00,C106-00-00_0003 ,18002.2
    5410    5410
River Rch & RM=C106-00-00,C106-00-00_0003 ,16445.9
    6389    6389
River Rch & RM=C106-00-00,C106-00-00_0003 ,14956.8
    7491    7491
River Rch & RM=C106-00-00,C106-00-00_0003 ,13835.3
    8444    8444
River Rch & RM=C106-00-00,C106-00-00_0003 ,11825.8
    9266    9266
River Rch & RM=C106-00-00,C106-00-00_0003 ,8929.9
   10594   10594
River Rch & RM=C106-00-00,C106-00-00_0003 ,7825.3
   11149   11149
River Rch & RM=C106-00-00,C106-00-00_0003 ,7287.2
   11322   11322
River Rch & RM=C106-00-00,C106-00-00_0003 ,1115.1
   13518   13518
Boundary for River Rch & Prof#=C106-00-00,C106-00-00_0003 , 1
Up Type= 0
Dn Type= 3
Dn Slope=0.0002
Boundary for River Rch & Prof#=C106-00-00,C106-00-00_0003 , 2
Up Type= 0
Dn Type= 1
Dn Known WS=19.31
DSS Import GetInterval= 0
DSS Import GetPeak= 0
DSS Import FillOption= 0

--- C106-00-00.g01 (geometry) ---

Geom Title=C106-00-00 2015
Program Version=4.10

River Reach=C106-00-00      ,C106-00-00_0003
Reach XY= 30
      3168904.48     13799803.74        3168334.       13800234.
      3168306.75       13800466.      3167862.98     13800443.56
       3167721.5       13803267.      3165301.75       13806252.
       3165248.5       13806726.       3165692.5       13808007.
        3165696.       13808484.        3164889.       13809491.
      3164648.25       13810168.       3163807.5       13810447.
      3163089.25       13811435.      3162562.75       13811566.
       3161911.5       13812714.      3160834.25       13812763.
      3160155.75       13813809.      3160495.25       13815729.
      3160012.25       13816105.        3159607.       13816811.
      3158533.93      13816534.7        3157986.       13817086.
      3157236.93     13817176.44      3156909.25       13817408.
      3156755.92     13817986.17      3157151.74     13818475.54
      3157148.14     13818817.37      3156257.25       13819098.
      3155863.55      13818968.5      3155583.34     13819166.55

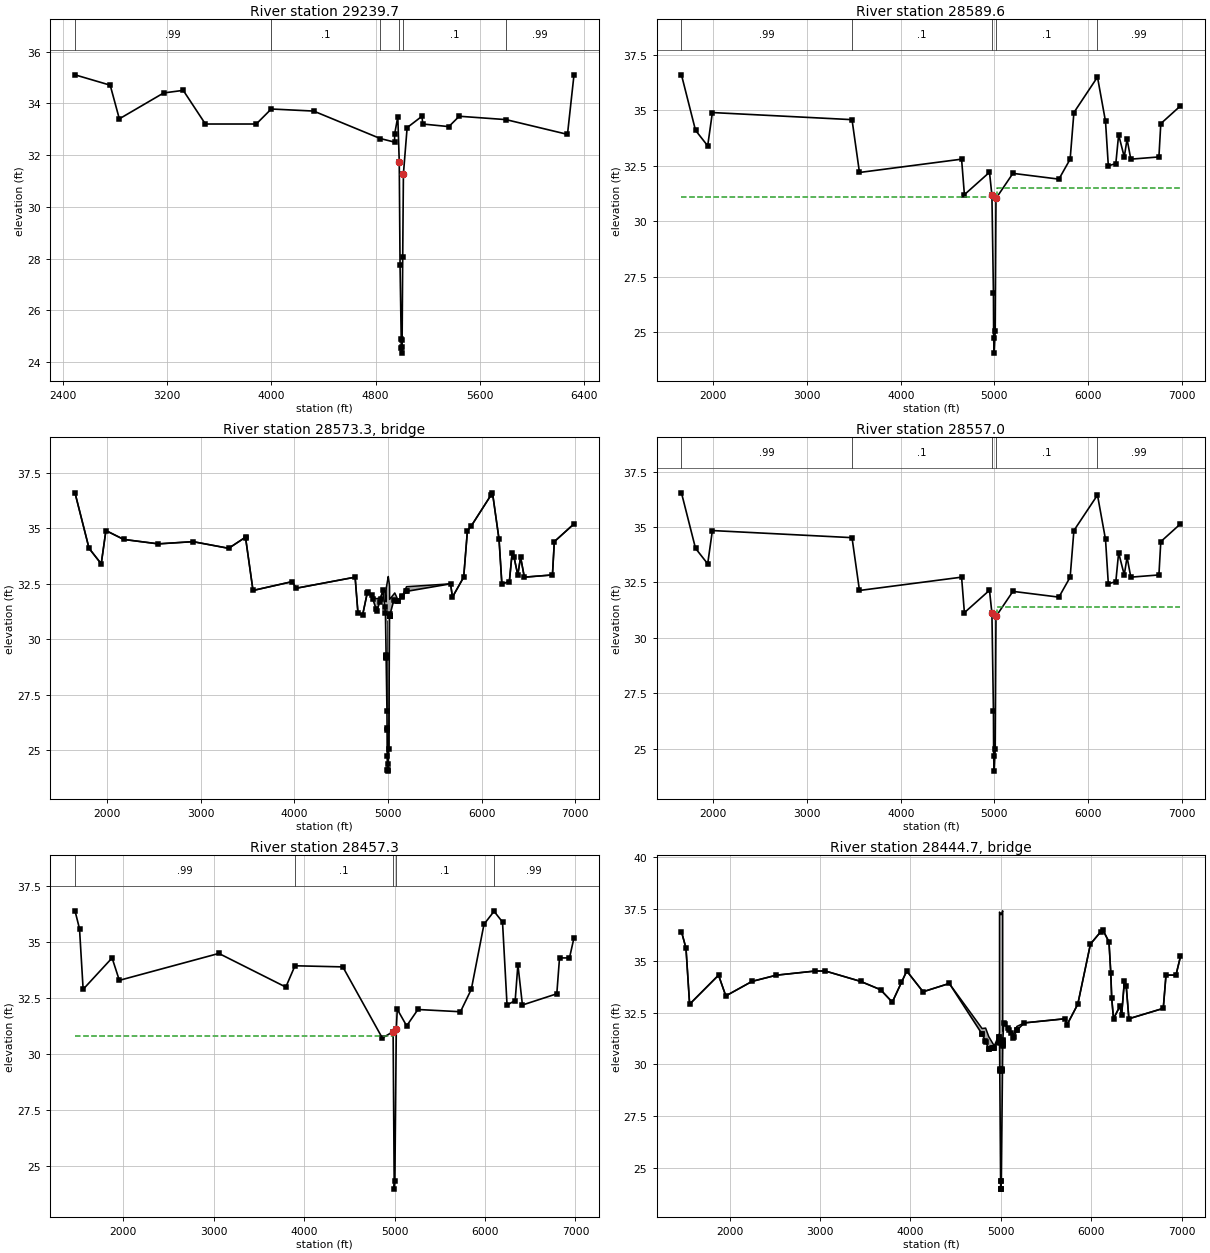
Type RM Length L Ch R = 1 ,29239.7 ,522.6,650.1,320.7
BEGIN DESCRIPTION:
Cross Section 29239.7
END DESCRIPTION:
XS GIS Cut Line= 4
       3167142.8     13798029.61       3168717.8     13799679.52
      3169039.03     13799893.27      3170140.46     13800257.16
#Sta/Elev= 30
  2494.8    35.1  2764.8    34.7  2834.8    33.4  3174.8    34.4  3324.8    34.5
  3494.8    33.2  3884.8    33.2    4000   33.78  4324.8    33.7  4835.4   32.64
  4945.8    32.5  4946.1   32.81  4970.4   33.48  4981.5   31.73  4987.6   27.74
  4996.6   24.89  4996.7   24.53  4999.6   24.35  5003.4   24.58  5003.5   24.86
    5008   28.05  5013.4   31.27  5041.9   33.06  5155.8    33.5  5161.6    33.2
  5361.6    33.1  5441.6    33.5    5800   33.37  6271.6    32.8  6321.6    35.1
#Mann= 6 , 1 , 0
  2494.8     .99       0    4000      .1       0  4835.4      .1       0
  4981.5     .04       0  5013.4      .1       0    5800     .99       0
Bank Sta=4981.5,5013.4
XS Rating Curve= 0 ,0
Exp/Cntr=0.5,0.3

Type RM Length L Ch R = 1 ,28589.6 ,32.6,32.6,32.6
BEGIN DESCRIPTION:
Upstream Section of Bridge/Culvert/Weir
END DESCRIPTION:
XS GIS Cut Line= 6
      3166388.13     13797517.75       3168375.5     13800176.53
      3168393.04     13800225.43      3168440.36     13800265.19
       3169461.1     13800252.88      3170301.22     13800487.18
#Sta/Elev= 30
  1659.5    36.6  1809.5    34.1  1939.5    33.4  1989.5    34.9    3480   34.58
  3559.5    32.2  4649.5    32.8  4679.5    31.2  4947.4   32.21  4973.2   31.17
  4989.5   26.75  4991.8   24.73  4997.3   24.06  5008.3   25.05  5016.6   31.03
  5197.4   32.16  5688.2    31.9  5808.2    32.8  5848.2    34.9    6100    36.5
  6185.7    34.5  6215.7    32.5  6295.7    32.6  6325.7    33.9  6385.7    32.9
  6415.7    33.7  6455.7    32.8  6755.7    32.9  6775.7    34.4  6985.7    35.2
#Mann= 5 , 1 , 0
  1659.5     .99       0    3480      .1       0  4973.2     .04       0
  5016.6      .1       0    6100     .99       0
#XS Ineff= 2 , 0
       0  4973.5    31.1    5026       0    31.5
Permanent Ineff=
       F       F
Bank Sta=4973.2,5016.6
XS Rating Curve= 0 ,0
Exp/Cntr=0.5,0.3

Type RM Length L Ch R = 3 ,28573.3 ,,,
BEGIN DESCRIPTION:
EVALYN WILSON PARK 2
Structure ID: C06-23
END DESCRIPTION:
Node Name=EVALYN WILSON PA
Bridge Culvert--1,0,-1,-1, 0
Deck Dist Width WeirC Skew NumUp NumDn MinLoCord MaxHiCord MaxSubmerge Is_Ogee
10,12.6,2.6,0, 52, 52, , , 0.95, 0, 1,1,,
  1659.5  1809.5  1939.5  1989.5  2179.5  2549.5  2919.5  3299.5  3479.5  3559.5
  3979.5  4019.5  4649.5  4679.5  4729.5  4781.9  4824.7  4838.2  4881.2    4921
  4947.4  4966.2  4973.2 4980.29  4980.4  4980.5  5003.4  5008.3 5017.57 5017.68
  5061.6  5072.7  5111.9  5152.4    5198  5668.2  5688.2  5808.2  5848.2  5888.2
  6115.7  6185.7  6215.7  6295.7  6325.7  6345.7  6385.7  6415.7  6455.7  6755.7
  6775.7  6985.7
    36.6    34.1    33.4    34.9    34.5    34.3    34.4    34.1    34.6    32.2
    32.6    32.3    32.8    31.2    31.1   32.15   31.99   31.87   31.83   31.88
   32.22    32.2   31.94   31.69   32.29   32.29   32.83   32.68    32.4    31.8
   32.03   32.09   31.73   31.94   32.37    32.5    31.9    32.8    34.9    35.1
    36.6    34.5    32.5    32.6    33.9    33.7    32.9    33.7    32.8    32.9
    34.4    35.2
    36.6    34.1    33.4    34.9    34.5    34.3    34.4    34.1    34.6    32.2
    32.6    32.3    32.8    31.2    31.1   32.14   31.98   31.81   31.28   31.81
   32.21   31.45   31.17   29.25   29.22   30.64   31.18   31.03   31.05   31.05
   31.75   31.74   31.72   31.94   32.16    32.5    31.9    32.8    34.9    35.1
    36.6    34.5    32.5    32.6    33.9    33.7    32.9    33.7    32.8    32.9
    34.4    35.2
  1659.5  1809.5  1939.5  1989.5  2179.5  2549.5  2919.5  3299.5  3479.5  3559.5
  3979.5  4019.5  4649.5  4679.5  4729.5  4781.9  4824.7  4838.2  4881.2    4921
  4947.4  4966.2  4973.2 4980.29  4980.4  4980.5  5003.4  5008.3 5017.57 5017.68
  5061.6  5072.7  5111.9  5152.4    5198  5668.2  5688.2  5808.2  5848.2  5888.2
  6115.7  6185.7  6215.7  6295.7  6325.7  6345.7  6385.7  6415.7  6455.7  6755.7
  6775.7  6985.7
    36.6    34.1    33.4    34.9    34.5    34.3    34.4    34.1    34.6    32.2
    32.6    32.3    32.8    31.2    31.1   32.15   31.99   31.87   31.83   31.88
   32.22    32.2   31.94   31.69   32.29   32.29   32.83   32.68    32.4    31.8
   32.03   32.09   31.73   31.94   32.37    32.5    31.9    32.8    34.9    35.1
    36.6    34.5    32.5    32.6    33.9    33.7    32.9    33.7    32.8    32.9
    34.4    35.2
   36.54   34.04   33.34   34.84   34.44   34.24   34.34   34.04   34.54   32.14
   32.54   32.24   32.74   31.14   31.04   32.08   31.92   31.75   31.22   31.75
   32.15   31.39   31.11   29.19   29.16   30.58   31.12   30.97   30.99   30.99
   31.69   31.68   31.66   31.88    32.1   32.44   31.84   32.74   34.84   35.04
   36.54   34.44   32.44   32.54   33.84   33.64   32.84   33.64   32.74   32.84
   34.34   35.14
Pier Skew, UpSta & Num, DnSta & Num=  ,4989.5, 2 ,4989.5, 2 , 0 , 0 , 0 ,,
       1       1
   25.42   31.86
       1       1
   25.36    31.8
Pier Skew, UpSta & Num, DnSta & Num=  ,5008.3, 2 ,5008.3, 2 , 0 , 0 , 0 ,,
       1       1
   23.98   32.05
       1       1
   23.92   31.99
Abutment Skew #Up #Dn= , 2 , 2
  4980.3  4990.7
   30.64   25.91
  4980.3  4990.7
   30.58   25.85
BR Coef= 1 , 1 , 0 ,1.25, 0 ,,,0.8,0,2,0,
WSPro=,,,, 1 ,,,, 0 ,,,, 0 ,,,,-1 ,-1 ,-1 , 0 , 0 , 0 , 0 , 0
BR U #Sta/Elev= 76
  1659.5    36.6  1809.5    34.1  1939.5    33.4  1989.5    34.9  2179.5    34.5
  2549.5    34.3  2919.5    34.4  3299.5    34.1  3479.5    34.6    3480   34.58
  3559.5    32.2  3979.5    32.6  4019.5    32.3  4649.5    32.8  4679.5    31.2
  4729.5    31.1  4778.8   32.08  4781.9   32.14  4824.7   31.98  4838.2   31.81
  4872.8   31.38  4881.2   31.28  4911.4   31.67    4921   31.81  4947.4   32.21
  4966.2   31.45  4973.2   31.17  4980.1    29.3 4980.21   29.27 4980.29   29.25
  4980.4   29.22  4980.5   29.19 4980.61   29.16  4989.5   26.75  4990.6   26.02
  4990.7   25.91  4991.8   24.73  4994.1   24.13  4997.3   24.06  5001.6    24.1
  5003.4   24.36  5008.3   25.05  5016.6   31.03  5017.4   31.04 5017.46   31.04
 5017.57   31.05 5017.68   31.05 5017.79   31.05  5017.9   31.05  5023.7   31.14
  5061.6   31.75  5072.7   31.74  5109.4   31.71  5111.9   31.72  5147.4   31.91
  5152.4   31.94  5197.4   32.16    5198   32.16  5668.2    32.5  5688.2    31.9
  5808.2    32.8  5848.2    34.9  5888.2    35.1    6100    36.5  6115.7    36.6
  6185.7    34.5  6215.7    32.5  6295.7    32.6  6325.7    33.9  6345.7    33.7
  6385.7    32.9  6415.7    33.7  6455.7    32.8  6755.7    32.9  6775.7    34.4
  6985.7    35.2
BR U #Mann= 5
  1659.5     .99    3480      .1  4973.2     .04  5016.6      .1    6100     .99
BR U Banks=4973.2,5016.6
BR D #Sta/Elev= 76
  1659.5   36.54  1809.5   34.04  1939.5   33.34  1989.5   34.84  2179.5   34.44
  2549.5   34.24  2919.5   34.34  3299.5   34.04  3479.5   34.54    3480   34.52
  3559.5   32.14  3979.5   32.54  4019.5   32.24  4649.5   32.74  4679.5   31.14
  4729.5   31.04  4778.8   32.02  4781.9   32.08  4824.7   31.92  4838.2   31.75
  4872.8   31.32  4881.2   31.22  4911.4   31.61    4921   31.75  4947.4   32.15
  4966.2   31.39  4973.2   31.11  4980.1   29.24 4980.21   29.21 4980.29   29.19
  4980.4   29.16  4980.5   29.13 4980.61    29.1  4989.5   26.69  4990.6   25.96
  4990.7   25.85  4991.8   24.67  4994.1   24.07  4997.3      24  5001.6   24.04
  5003.4    24.3  5008.3   24.99  5016.6   30.97  5017.4   30.98 5017.46   30.98
 5017.57   30.99 5017.68   30.99 5017.79   30.99  5017.9   30.99  5023.7   31.08
  5061.6   31.69  5072.7   31.68  5109.4   31.65  5111.9   31.66  5147.4   31.85
  5152.4   31.88  5197.4    32.1    5198    32.1  5668.2   32.44  5688.2   31.84
  5808.2   32.74  5848.2   34.84  5888.2   35.04    6100   36.44  6115.7   36.54
  6185.7   34.44  6215.7   32.44  6295.7   32.54  6325.7   33.84  6345.7   33.64
  6385.7   32.84  6415.7   33.64  6455.7   32.74  6755.7   32.84  6775.7   34.34
  6985.7   35.14
BR D #Mann= 5
  1659.5     .99    3480      .1  4973.2     .04  5016.6      .1    6100     .99
BR D Banks=4973.2,5016.6
BC Design=,, 0 ,, 0 ,,,,,,
BC HTab HWMax=36.6
BC Use User HTab Curves=0
BC User HTab FreeFlow(D)= 0

Type RM Length L Ch R = 1 ,28557.0 ,156.2,99.7,59.8
BEGIN DESCRIPTION:
Downstream Section of Bridge/Culvert/Weir
END DESCRIPTION:
XS GIS Cut Line= 6
      3166362.07     13797537.35      3168349.44     13800196.13
      3168366.98     13800245.03       3168414.3     13800284.79
      3169435.04     13800272.48      3170275.16     13800506.77
#Sta/Elev= 30
  1659.5   36.54  1809.5   34.04  1939.5   33.34  1989.5   34.84    3480   34.52
  3559.5   32.14  4649.5   32.74  4679.5   31.14  4947.4   32.15  4973.2   31.11
  4989.5   26.69  4991.8   24.67  4997.3      24  5008.3   24.99  5016.6   30.97
  5197.4    32.1  5688.2   31.84  5808.2   32.74  5848.2   34.84    6100   36.44
  6185.7   34.44  6215.7   32.44  6295.7   32.54  6325.7   33.84  6385.7   32.84
  6415.7   33.64  6455.7   32.74  6755.7   32.84  6775.7   34.34  6985.7   35.14
#Mann= 5 , 1 , 0
  1659.5     .99       0    3480      .1       0  4973.2     .04       0
  5016.6      .1       0    6100     .99       0
#XS Ineff= 2 , 0
       0  4973.5      31    5026       0    31.4
Permanent Ineff=
       F       F
Bank Sta=4973.2,5016.6
XS Rating Curve= 0 ,0
Exp/Cntr=0.5,0.3

Type RM Length L Ch R = 1 ,28457.3 ,25.2,25.2,25.2
BEGIN DESCRIPTION:
Upstream Section of Bridge/Culvert/Weir
END DESCRIPTION:
XS GIS Cut Line= 6
      3166217.36     13797639.82      3167976.86     13800289.23
      3168273.44     13800302.55      3168355.09     13800315.42
      3169438.23     13800320.91      3170279.04     13800546.58
#Sta/Elev= 30
  1468.9    36.4  1518.9    35.6  1558.9    32.9  1878.9    34.3  1958.9    33.3
  3058.9    34.5  3798.9      33    3900   33.95  4428.9    33.9    4865   30.73
  4984.6   31.01    4997   23.99    5004   24.36  5019.8   31.13  5030.6   32.01
  5134.2   31.27  5258.9      32  5728.9    31.9  5848.9    32.9  5988.9    35.8
    6100   36.38  6193.7    35.9  6243.7    32.2  6333.7    32.4  6363.7      34
  6413.7    32.2  6793.7    32.7  6823.7    34.3  6933.7    34.3  6983.7    35.2
#Mann= 5 , 1 , 0
  1468.9     .99       0    3900      .1       0  4984.6     .04       0
  5019.8      .1       0    6100     .99       0
#XS Ineff= 2 , 0
       0    4985    30.8  5023.3       0    31.4
Permanent Ineff=
       F       F
Bank Sta=4984.6,5019.8
XS Rating Curve= 0 ,0
Exp/Cntr=0.5,0.3

Type RM Length L Ch R = 3 ,28444.7 ,,,
BEGIN DESCRIPTION:
EVALYN WILSON PARK 1
Structure ID: C06-22
END DESCRIPTION:
Node Name=EVALYN WILSON PA
Bridge Culvert--1,0,-1,-1, 0
Deck Dist Width WeirC Skew NumUp NumDn MinLoCord MaxHiCord MaxSubmerge Is_Ogee
10,5.2,2.6,0, 56, 56, , , 0.95, 0, 1,1,,
  1468.9  1518.9  1558.9  1878.9  1958.9  2248.9  2518.9  2948.9  3058.9  3448.9
  3668.9  3798.9  3958.9  4138.9  4428.9  4791.3  4830.6    4865  4926.3  4979.3
 4983.59  4983.7  4984.6 4986.71  4986.9  5000.4 5016.49  5016.6  5019.3 5019.41
  5019.8  5030.6  5094.1  5107.5  5134.2  5141.2  5175.7  5258.9  5708.9  5728.9
  5848.9  5988.9  6123.7  6193.7  6213.7  6223.7  6243.7  6313.7  6333.7  6363.7
  6383.7  6413.7  6793.7  6823.7  6933.7  6983.7
    36.4    35.6    32.9    34.3    33.3      34    34.3    34.5    34.5      34
    33.6      33    34.5    33.5    33.9   31.73   31.75   31.34   30.89   31.44
   31.54   37.34   37.33   37.32   37.32   37.21   37.37   37.37    37.4    31.6
    31.6   32.02   31.67   31.54   31.47   31.47   31.83      32    32.2    31.9
    32.9    35.8    36.5    35.9    34.4    33.2    32.2    32.8    32.4      34
    33.8    32.2    32.7    34.3    34.3    35.2
    36.4    35.6    32.9    34.3    33.3      34    34.3    34.5    34.5      34
    33.6      33    34.5    33.5    33.9   31.46    31.1   30.73   30.77   31.33
   31.07   31.06   31.01   29.78   29.87   29.76   29.92   29.76   30.92   30.96
   31.13   32.01   31.66   31.53   31.27   31.33   31.65      32    32.2    31.9
    32.9    35.8    36.5    35.9    34.4    33.2    32.2    32.8    32.4      34
    33.8    32.2    32.7    34.3    34.3    35.2
  1468.9  1518.9  1558.9  1878.9  1958.9  2248.9  2518.9  2948.9  3058.9  3448.9
  3668.9  3798.9  3958.9  4138.9  4428.9  4791.3  4830.6    4865  4926.3  4979.3
 4983.59  4983.7  4984.6 4986.71  4986.9  5000.4 5016.49  5016.6  5019.3 5019.41
  5019.8  5030.6  5094.1  5107.5  5134.2  5141.2  5175.7  5258.9  5708.9  5728.9
  5848.9  5988.9  6123.7  6193.7  6213.7  6223.7  6243.7  6313.7  6333.7  6363.7
  6383.7  6413.7  6793.7  6823.7  6933.7  6983.7
    36.4    35.6    32.9    34.3    33.3      34    34.3    34.5    34.5      34
    33.6      33    34.5    33.5    33.9   31.73   31.75   31.34   30.89   31.44
   31.54   37.34   37.33   37.32   37.32   37.21   37.37   37.37    37.4    31.6
    31.6   32.02   31.67   31.54   31.47   31.47   31.83      32    32.2    31.9
    32.9    35.8    36.5    35.9    34.4    33.2    32.2    32.8    32.4      34
    33.8    32.2    32.7    34.3    34.3    35.2
   36.32   35.52   32.82   34.22   33.22   33.92   34.22   34.42   34.42   33.92
   33.52   32.92   34.42   33.42   33.82   31.38   31.02   30.65   30.69   31.25
   30.99   30.98   30.93    29.7   29.79   29.68   29.84   29.68   30.84   30.88
   31.05   31.93   31.58   31.45   31.19   31.25   31.57   31.92   32.12   31.82
   32.82   35.72   36.42   35.82   34.32   33.12   32.12   32.72   32.32   33.92
   33.72   32.12   32.62   34.22   34.22   35.12
BR Coef= 1 , 1 , 0 ,1.25, 0 ,,,0.8,0,2,0,
WSPro=,,,, 1 ,,,, 0 ,,,, 0 ,,,,-1 ,-1 ,-1 , 0 , 0 , 0 , 0 , 0
BR U #Sta/Elev= 78
  1468.9    36.4  1518.9    35.6  1558.9    32.9  1878.9    34.3  1958.9    33.3
  2248.9      34  2518.9    34.3  2948.9    34.5  3058.9    34.5  3448.9      34
  3668.9    33.6  3798.9      33    3900   33.95  3958.9    34.5  4138.9    33.5
  4428.9    33.9  4791.3   31.46  4791.4   31.46  4828.1   31.13  4830.6    31.1
  4863.4   30.75    4865   30.73  4899.4   30.78  4909.3   30.78  4926.3   30.77
    4927   30.77  4977.2   31.31  4979.3   31.33  4983.3   31.09 4983.59   31.07
  4983.7   31.06 4983.81   31.06  4984.6   31.01 4986.71   29.78  4986.8   29.73
  4986.9   29.67    4996   24.36    4997   23.99  5000.3   24.01  5000.4   24.02
    5004   24.36  5016.4   29.67 5016.49   29.71  5016.6   29.76 5019.19   30.87
  5019.3   30.92 5019.41   30.96  5019.8   31.13  5020.3   31.17  5030.6   32.01
  5044.8   31.93  5076.1   31.76  5094.1   31.66  5107.5   31.53  5134.2   31.27
  5141.2   31.33  5175.7   31.65  5176.1   31.65  5258.9      32  5708.9    32.2
  5728.9    31.9  5848.9    32.9  5988.9    35.8    6100   36.38  6123.7    36.5
  6193.7    35.9  6213.7    34.4  6223.7    33.2  6243.7    32.2  6313.7    32.8
  6333.7    32.4  6363.7      34  6383.7    33.8  6413.7    32.2  6793.7    32.7
  6823.7    34.3  6933.7    34.3  6983.7    35.2
BR U #Mann= 5
  1468.9     .99    3900      .1  4984.6     .04  5019.8      .1    6100     .99
BR U Banks=4984.6,5019.8
BR D #Sta/Elev= 78
  1468.9   36.32  1518.9   35.52  1558.9   32.82  1878.9   34.22  1958.9   33.22
  2248.9   33.92  2518.9   34.22  2948.9   34.42  3058.9   34.42  3448.9   33.92
  3668.9   33.52  3798.9   32.92    3900   33.87  3958.9   34.42  4138.9   33.42
  4428.9   33.82  4791.3   31.38  4791.4   31.38  4828.1   31.05  4830.6   31.02
  4863.4   30.67    4865   30.65  4899.4    30.7  4909.3    30.7  4926.3   30.69
    4927   30.69  4977.2   31.23  4979.3   31.25  4983.3   31.01 4983.59   30.99
  4983.7   30.98 4983.81   30.98  4984.6   30.93 4986.71    29.7  4986.8   29.65
  4986.9   29.59    4996   24.28    4997   23.91  5000.3   23.93  5000.4   23.94
    5004   24.28  5016.4   29.59 5016.49   29.63  5016.6   29.68 5019.19   30.79
  5019.3   30.84 5019.41   30.88  5019.8   31.05  5020.3   31.09  5030.6   31.93
  5044.8   31.85  5076.1   31.68  5094.1   31.58  5107.5   31.45  5134.2   31.19
  5141.2   31.25  5175.7   31.57  5176.1   31.57  5258.9   31.92  5708.9   32.12
  5728.9   31.82  5848.9   32.82  5988.9   35.72    6100    36.3  6123.7   36.42
  6193.7   35.82  6213.7   34.32  6223.7   33.12  6243.7   32.12  6313.7   32.72
  6333.7   32.32  6363.7   33.92  6383.7   33.72  6413.7   32.12  6793.7   32.62
  6823.7   34.22  6933.7   34.22  6983.7   35.12
BR D #Mann= 5
  1468.9     .99    3900      .1  4984.6     .04  5019.8      .1    6100     .99
BR D Banks=4984.6,5019.8
BC Design=,, 0 ,, 0 ,,,,,,
BC HTab HWMax=36.5
BC Use User HTab Curves=0
BC User HTab FreeFlow(D)= 0

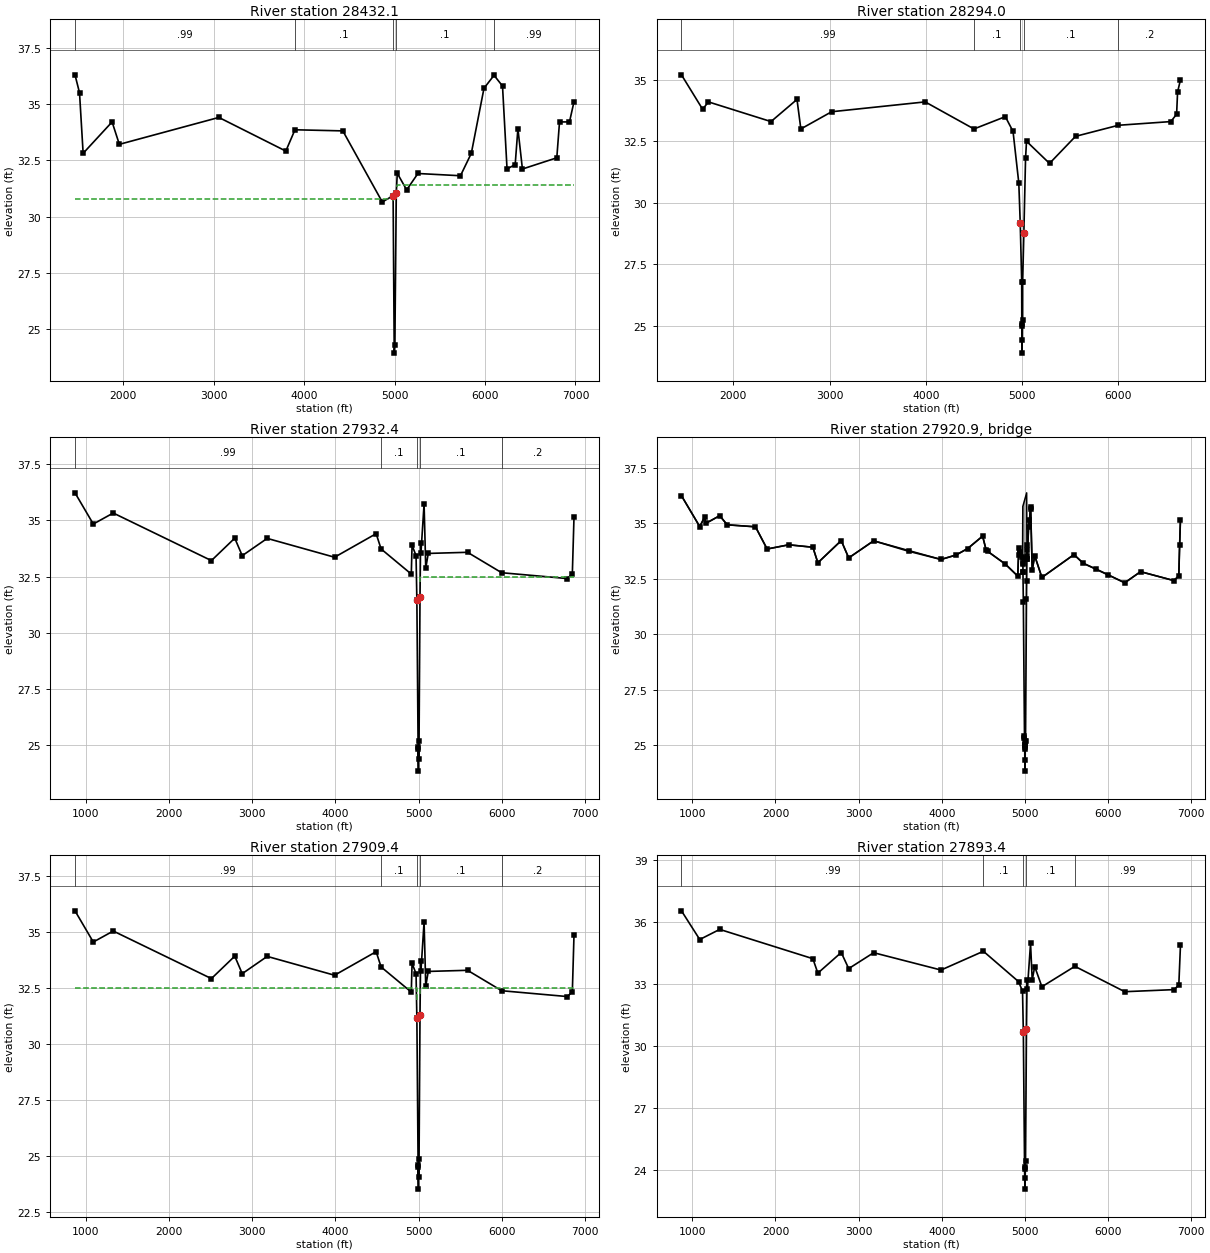
Type RM Length L Ch R = 1 ,28432.1 ,131.4,138.1,156
BEGIN DESCRIPTION:
Downstream Section of Bridge/Culvert/Weir
END DESCRIPTION:
XS GIS Cut Line= 6
      3166217.64     13797665.01      3167977.14     13800314.43
      3168273.72     13800327.75      3168355.37     13800340.62
      3169438.51     13800346.11      3170279.31     13800571.77
#Sta/Elev= 30
  1468.9   36.32  1518.9   35.52  1558.9   32.82  1878.9   34.22  1958.9   33.22
  3058.9   34.42  3798.9   32.92    3900   33.87  4428.9   33.82    4865   30.65
  4984.6   30.93    4997   23.91    5004   24.28  5019.8   31.05  5030.6   31.93
  5134.2   31.19  5258.9   31.92  5728.9   31.82  5848.9   32.82  5988.9   35.72
    6100    36.3  6193.7   35.82  6243.7   32.12  6333.7   32.32  6363.7   33.92
  6413.7   32.12  6793.7   32.62  6823.7   34.22  6933.7   34.22  6983.7   35.12
#Mann= 5 , 1 , 0
  1468.9     .99       0    3900      .1       0  4984.6     .04       0
  5019.8      .1       0    6100     .99       0
#XS Ineff= 2 , 0
       0    4985    30.8  5023.3       0    31.4
Permanent Ineff=
       F       F
Bank Sta=4984.6,5019.8
XS Rating Curve= 0 ,0
Exp/Cntr=0.5,0.3

Type RM Length L Ch R = 1 ,28294.0 ,154.8,361.6,322.4
BEGIN DESCRIPTION:
Cross Section 28294.0-Interpolated
END DESCRIPTION:
XS GIS Cut Line= 6
      3166138.34     13797750.69      3167260.56     13799503.49
      3167806.61     13800151.92      3167977.25     13800336.21
      3168147.89     13800404.47      3169872.21     13800983.54
#Sta/Elev= 30
  1461.9    35.2  1681.9    33.8  1741.9    34.1  2391.9    33.3  2661.9    34.2
  2701.9      33  3021.9    33.7  3993.2    34.1    4500      33  4825.8    33.5
  4905.8    32.9  4965.8    30.8 4980.44   29.19  4995.8    26.8 4996.84   25.06
 4999.44   23.89 4999.74   24.98 5002.04   24.41 5005.64   25.24  5005.8    26.8
 5018.14   28.77  5035.8    31.8  5045.8    32.5  5284.8    31.6  5554.8    32.7
    6000   33.15  6544.8    33.3  6604.8    33.6  6614.8    34.5  6644.8      35
#Mann= 5 , 1 , 0
  1461.9     .99       0    4500      .1       0 4980.44     .04       0
 5018.14      .1       0    6000      .2       0
#XS Ineff= 2 , 0
       0  3993.2    34.1               0
Permanent Ineff=
       F       F
Bank Sta=4980.44,5018.14
XS Rating Curve= 0 ,0
Exp/Cntr=0.5,0.3

Type RM Length L Ch R = 1 ,27932.4 ,23,23,23
BEGIN DESCRIPTION:
Upstream Section of Bridge/Culvert/Weir
END DESCRIPTION:
XS GIS Cut Line= 6
      3165444.36     13797193.12      3166579.97     13798742.44
      3167955.83     13800358.44      3167975.39     13800500.96
      3168488.53     13800623.78      3169569.77     13801308.72
#Sta/Elev= 30
   869.8   36.23  1089.8   34.84  1329.8   35.33  2509.8   33.21  2790.7   34.21
  2880.7   33.43  3180.7    34.2  3990.7   33.36  4490.7   34.41    4550   33.73
  4913.3   32.61 4922.54   33.89 4970.54   33.43 4980.44   31.44 4995.34   24.81
 4999.44   23.83 4999.74   24.92 5002.04   24.35 5006.64   25.17 5018.14    31.6
 5025.04   33.99 5028.94   33.53 5067.04   35.74  5087.1   32.87  5117.1   33.53
  5589.6   33.58    6000   32.67  6789.6   32.41  6849.6   32.62  6869.6   35.15
#Mann= 5 ,-1 , 0
   869.8     .99       0    4550      .1       0 4980.44     .04       0
 5018.14      .1       0    6000      .2       0
#XS Ineff= 2 , 0
       0    4975    32.5    5020       0    32.5
Permanent Ineff=
       F       F
Bank Sta=4980.44,5018.14
XS Rating Curve= 0 ,0
Exp/Cntr=0.5,0.3

Type RM Length L Ch R = 3 ,27920.9 ,,,
BEGIN DESCRIPTION:
36" Pipeline
END DESCRIPTION:
Bridge Culvert--1,0,-1,-1, 0
Deck Dist Width WeirC Skew NumUp NumDn MinLoCord MaxHiCord MaxSubmerge Is_Ogee
10,3,3,0, 46, 46, , , 0.95, 0, ,,,
   869.8  1089.8  1149.8  1159.8  1329.8  1419.8  1759.8  1899.8  2159.8  2449.8
  2509.8  2790.7  2880.7  3180.7  3990.7  4170.7  4310.7  4490.7  4534.2  4764.2
  4913.3 4922.44 4922.54 4970.54 4974.04 4974.64 4975.92 5020.44 5023.34 5025.04
 5028.94 5046.94 5048.94 5067.04 5068.94  5087.1  5117.1  5203.4  5589.6  5699.6
  6199.6  6389.6  6789.6  6849.6  6859.6  6869.6
   36.23   34.84   35.28   34.98   35.33   34.92   34.83   33.83   34.02   33.91
   33.21   34.21   33.43    34.2   33.36   33.56   33.85   34.41   33.77   33.15
   32.61   33.56   33.89   33.44   35.75   35.76   35.77   36.36   34.25      34
   33.53   35.13   34.84   35.74   35.61   32.87   33.53   32.55   33.58   33.19
   32.31   32.81   32.41   32.62   34.02   35.15
   36.23   34.84   35.28   34.98   35.33   34.92   34.83   33.83   34.02   33.91
   33.21   34.21   33.43    34.2   33.36   33.56   33.85   34.41   33.77   33.15
   32.61   33.56   33.89   33.43    33.2   33.16   32.78   33.36    33.4   33.99
   33.53   35.13   34.84   35.74   35.61   32.87   33.53   32.55   33.58   33.19
   32.31   32.81   32.41   32.62   34.02   35.15
   869.8  1089.8  1149.8  1159.8  1329.8  1419.8  1759.8  1899.8  2159.8  2449.8
  2509.8  2790.7  2880.7  3180.7  3990.7  4170.7  4310.7  4490.7  4534.2  4764.2
  4913.3 4922.44 4922.54 4970.54 4974.04 4974.64 4975.92 5020.44 5023.34 5025.04
 5028.94 5046.94 5048.94 5067.04 5068.94  5087.1  5117.1  5203.4  5589.6  5699.6
  6199.6  6389.6  6789.6  6849.6  6859.6  6869.6
   36.23   34.84   35.28   34.98   35.33   34.92   34.83   33.83   34.02   33.91
   33.21   34.21   33.43    34.2   33.36   33.56   33.85   34.41   33.77   33.15
   32.61   33.56   33.89   33.44   35.75   35.76   35.77   36.36   34.25      34
   33.53   35.13   34.84   35.74   35.61   32.87   33.53   32.55   33.58   33.19
   32.31   32.81   32.41   32.62   34.02   35.15
   36.23   34.84   35.28   34.98   35.33   34.92   34.83   33.83   34.02   33.91
   33.21   34.21   33.43    34.2   33.36   33.56   33.85   34.41   33.77   33.15
   32.61   33.56   33.89   33.43    33.2   33.16   32.78   33.36    33.4   33.99
   33.53   35.13   34.84   35.74   35.61   32.87   33.53   32.55   33.58   33.19
   32.31   32.81   32.41   32.62   34.02   35.15
BR Coef= 1 , 1 , 0 ,1.25, 0 ,,,0.8,-1,2,0,
WSPro=,,,, 1 ,,,, 0 ,,,, 0 ,,,,-1 ,-1 ,-1 , 0 , 0 , 0 , 0 , 0
BR U #Sta/Elev= 68
   869.8   36.23  1089.8   34.84  1149.8   35.28  1159.8   34.98  1329.8   35.33
  1419.8   34.92  1759.8   34.83  1899.8   33.83  2159.8   34.02  2449.8   33.91
  2509.8   33.21  2790.7   34.21  2880.7   33.43  3180.7    34.2  3600.7   33.73
  3990.7   33.36  4170.7   33.56  4310.7   33.85  4490.7   34.41  4534.2   33.77
    4550   33.73  4764.2   33.15  4913.3   32.61 4922.44   33.56 4922.54   33.89
 4945.54   33.67 4946.04   33.69 4968.74   33.45 4970.54   33.43 4974.04    33.2
 4974.64   33.16 4975.83   32.81 4975.92   32.78 4980.44   31.44 4994.24    25.4
 4994.34   25.31 4995.34   24.81 4996.84      25 4999.44   23.83 4999.74   24.92
 5002.04   24.35 5004.14   25.01 5005.64   25.18 5006.64   25.17 5018.14    31.6
 5020.44    32.4 5023.23   33.36 5023.34    33.4 5025.04   33.99 5026.64    33.8
 5028.94   33.53 5046.94   35.13 5048.94   34.84 5067.04   35.74 5068.94   35.61
  5087.1   32.87  5117.1   33.53  5203.4   32.55  5589.6   33.58  5699.6   33.19
  5859.6   32.92    6000   32.67  6199.6   32.31  6389.6   32.81  6789.6   32.41
  6849.6   32.62  6859.6   34.02  6869.6   35.15
BR U #Mann= 5
   869.8     .99    4550      .1 4980.44     .04 5018.14      .1    6000      .2
BR U Banks=4980.44,5018.14
BR D #Sta/Elev= 68
   869.8   36.23  1089.8   34.84  1149.8   35.28  1159.8   34.98  1329.8   35.33
  1419.8   34.92  1759.8   34.83  1899.8   33.83  2159.8   34.02  2449.8   33.91
  2509.8   33.21  2790.7   34.21  2880.7   33.43  3180.7    34.2  3600.7   33.73
  3990.7   33.36  4170.7   33.56  4310.7   33.85  4490.7   34.41  4534.2   33.77
    4550   33.73  4764.2   33.15  4913.3   32.61 4922.44   33.56 4922.54   33.89
 4945.54   33.67 4946.04   33.69 4968.74   33.45 4970.54   33.43 4974.04    33.2
 4974.64   33.16 4975.83   32.81 4975.92   32.78 4980.44   31.44 4994.24    25.4
 4994.34   25.31 4995.34   24.81 4996.84      25 4999.44   23.83 4999.74   24.92
 5002.04   24.35 5004.14   25.01 5005.64   25.18 5006.64   25.17 5018.14    31.6
 5020.44    32.4 5023.23   33.36 5023.34    33.4 5025.04   33.99 5026.64    33.8
 5028.94   33.53 5046.94   35.13 5048.94   34.84 5067.04   35.74 5068.94   35.61
  5087.1   32.87  5117.1   33.53  5203.4   32.55  5589.6   33.58  5699.6   33.19
  5859.6   32.92    6000   32.67  6199.6   32.31  6389.6   32.81  6789.6   32.41
  6849.6   32.62  6859.6   34.02  6869.6   35.15
BR D #Mann= 5
   869.8     .99    4550      .1 4980.44     .04 5018.14      .1    6000      .2
BR D Banks=4980.44,5018.14
BC Design=,, 0 ,, 0 ,,,,,,
BC HTab HWMax=36.23
BC Use User HTab Curves=0
BC User HTab FreeFlow(D)= 0

Type RM Length L Ch R = 1 ,27909.4 ,16,16,16
BEGIN DESCRIPTION:
Downstream Section of Bridge/Culvert/Weir
END DESCRIPTION:
XS GIS Cut Line= 6
      3165421.36     13797193.12      3166556.97     13798742.44
      3167932.83     13800358.44      3167952.39     13800500.96
      3168465.53     13800623.78      3169546.77     13801308.72
#Sta/Elev= 30
   869.8   35.93  1089.8   34.54  1329.8   35.03  2509.8   32.91  2790.7   33.91
  2880.7   33.13  3180.7    33.9  3990.7   33.06  4490.7   34.11    4550   33.43
  4913.3   32.31 4922.54   33.59 4970.54   33.13 4980.44   31.14 4995.34   24.51
 4999.44   23.53 4999.74   24.62 5002.04   24.05 5006.64   24.87 5018.14    31.3
 5025.04   33.69 5028.94   33.23 5067.04   35.44  5087.1   32.57  5117.1   33.23
  5589.6   33.28    6000   32.37  6789.6   32.11  6849.6   32.32  6869.6   34.85
#Mann= 5 , 1 , 0
   869.8     .99       0    4550      .1       0 4980.44     .04       0
 5018.14      .1       0    6000      .2       0
#XS Ineff= 2 , 0
       0  4976.9    32.5 5020.75       0    32.5
Permanent Ineff=
       F       F
Bank Sta=4980.44,5018.14
XS Rating Curve= 0 ,0
Exp/Cntr=0.5,0.3

Type RM Length L Ch R = 1 ,27893.4 ,23,23,23
BEGIN DESCRIPTION:
Upstream Section of Bridge/Culvert/Weir
END DESCRIPTION:
XS GIS Cut Line= 6
      3165328.88     13797248.02      3166401.79     13798684.33
      3167906.08     13800374.63      3167939.22     13800487.04
      3168477.42     13800642.72      3169535.78     13801317.04
#Sta/Elev= 30
   869.8   36.54  1089.8   35.15  1329.8   35.64  2449.8   34.22  2509.8   33.52
  2790.7   34.52  2880.7   33.74  3180.7   34.51  3990.7   33.67    4500   34.58
 4922.54   33.11 4970.54   32.65 4980.44   30.66 4995.34   24.03 4999.44   23.05
 4999.74   24.14 5002.04   23.57 5006.64   24.39 5018.14   30.82 5025.04   33.21
 5028.94   32.75 5067.04   34.96  5087.1   33.18  5117.1   33.84  5203.4   32.86
    5600   33.85  6199.6   32.62  6789.6   32.72  6849.6   32.93  6869.6   34.86
#Mann= 5 ,-1 , 0
   869.8     .99       0    4500      .1       0 4980.44     .04       0
 5018.14      .1       0    5600     .99       0
#XS Ineff= 2 , 0
       0 4983.57      29 5015.54       0      29
Permanent Ineff=
       F       F
Bank Sta=4980.44,5018.14
XS Rating Curve= 0 ,0
Exp/Cntr=0.5,0.3