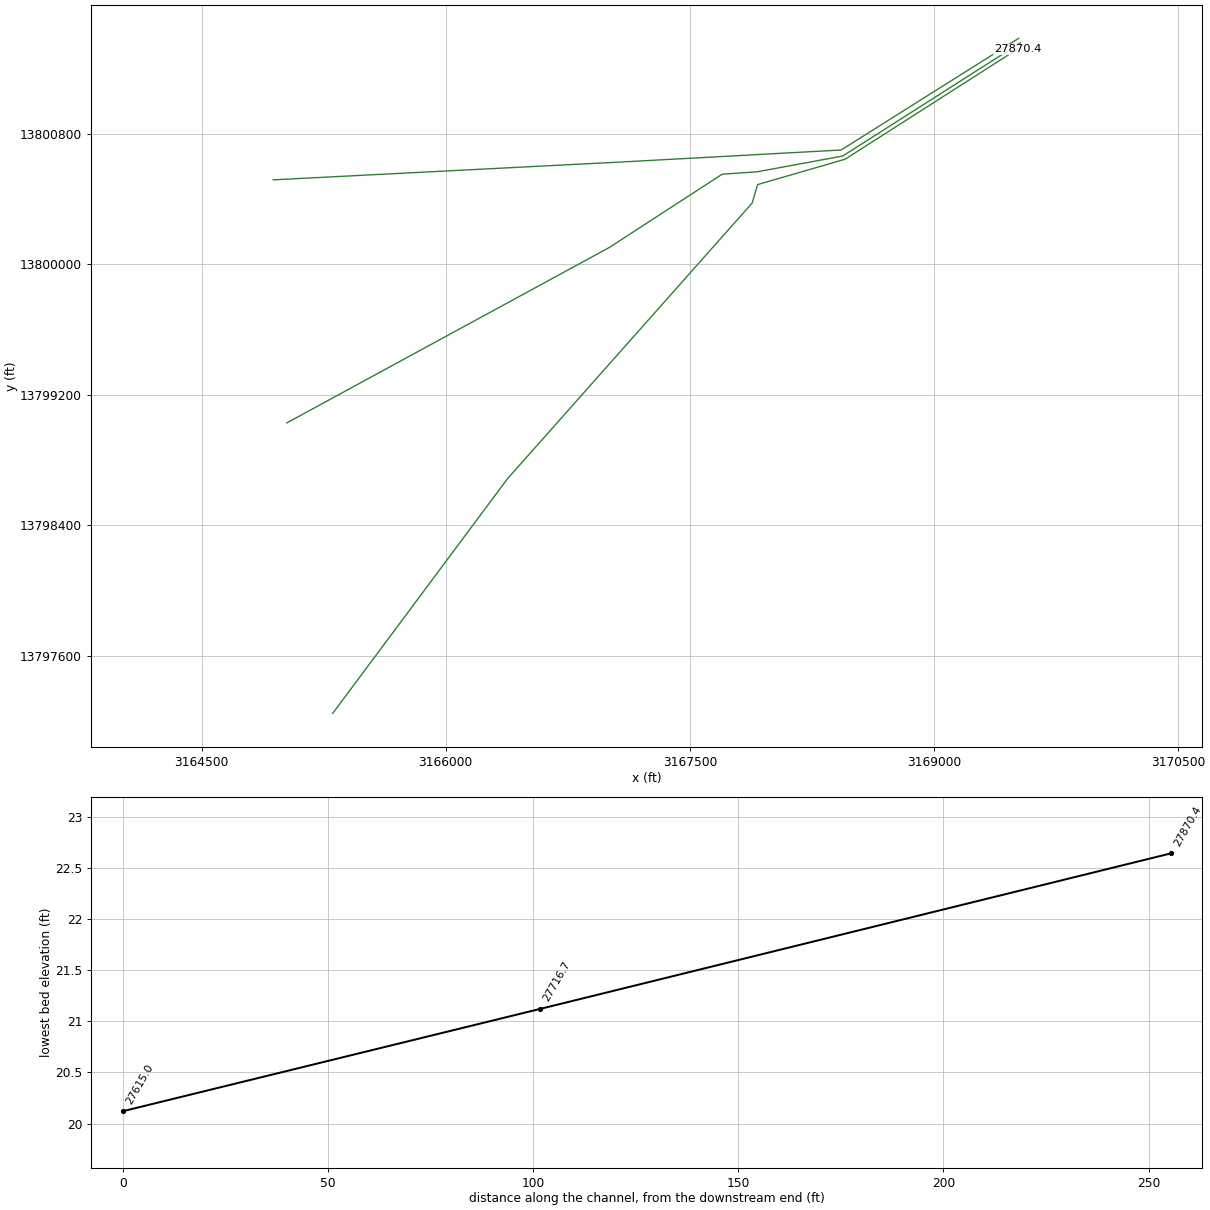
HEC-RAS study C106-00-00.PRJ: C106-00-00 2015

--- C106-00-00.g01 (geometry) --- (continued)

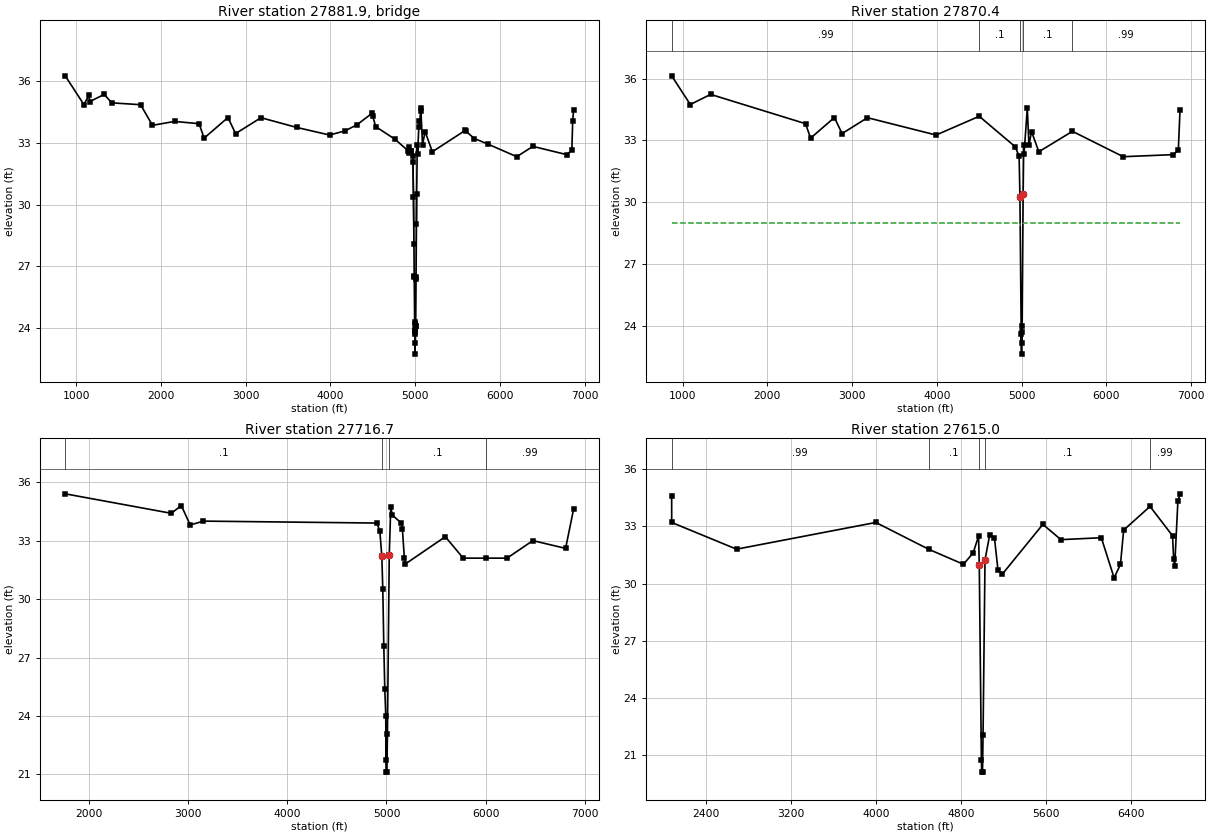
Type RM Length L Ch R = 3 ,27881.9 ,,,
BEGIN DESCRIPTION:
30" Pipeline
END DESCRIPTION:
Bridge Culvert--1,0,-1,-1, 0
Deck Dist Width WeirC Skew NumUp NumDn MinLoCord MaxHiCord MaxSubmerge Is_Ogee
10,3,3,0, 20, 20, , , 0.95, 0, ,,,
 4970.54 4974.64 4980.44  4983.6 4989.17 4989.26 4994.24 4994.34 4995.34 4996.84
 4999.44 4999.74 5002.04 5004.14 5005.64 5006.64 5010.79  5010.9 5015.54 5018.14
   32.35   32.08   30.36   28.98   28.98   28.98   28.99   28.99   28.99   28.99
   28.99   28.99   28.99   28.99   28.99   28.99      29      29   29.07   30.52
   32.35   32.08   30.36   28.08   26.54    26.5    26.5    26.5    26.5    26.5
    26.5    26.5    26.5    26.5    26.5    26.5   26.51   26.47   29.07   30.52
 4970.54 4974.64 4980.44  4983.6 4989.17 4989.26 4994.24 4994.34 4995.34 4996.84
 4999.44 4999.74 5002.04 5004.14 5005.64 5006.64 5010.79  5010.9 5015.54 5018.14
   32.35   32.08   30.36   28.98   28.98   28.98   28.99   28.99   28.99   28.99
   28.99   28.99   28.99   28.99   28.99   28.99      29      29   29.07   30.52
   32.35   32.08   30.36   28.08   26.54    26.5    26.5    26.5    26.5    26.5
    26.5    26.5    26.5    26.5    26.5    26.5   26.51   26.47   29.07   30.52
BR Coef= 1 , 1 , 0 ,1.25, 0 ,,,0.8,0,2,0,
WSPro=,,,, 1 ,,,, 0 ,,,, 0 ,,,,-1 ,-1 ,-1 , 0 , 0 , 0 , 0 , 0
BR U #Sta/Elev= 66
   869.8   36.24  1089.8   34.85  1149.8   35.29  1159.8   34.99  1329.8   35.34
  1419.8   34.93  1759.8   34.84  1899.8   33.84  2159.8   34.03  2449.8   33.92
  2509.8   33.22  2790.7   34.22  2880.7   33.44  3180.7   34.21  3600.7   33.74
  3990.7   33.37  4170.7   33.57  4310.7   33.86  4490.7   34.42    4500   34.28
  4534.2   33.78  4764.2   33.16  4913.3   32.62 4922.44   32.48 4922.54   32.81
 4945.54   32.59 4946.04   32.61 4970.54   32.35 4974.64   32.08 4980.44   30.36
 4985.64   28.08 4989.17   26.54 4989.26    26.5 4994.24   24.32 4994.34   24.23
 4995.34   23.73 4996.84   23.92 4999.44   22.75 4999.74   23.84 5002.04   23.27
 5004.14   23.93 5005.64    24.1 5006.64   24.09 5010.79   26.41  5010.9   26.47
 5015.54   29.07 5018.14   30.52 5025.04   32.91 5028.94   32.45 5046.94   34.05
 5048.94   33.76 5067.04   34.66 5068.94   34.53  5087.1   32.88  5117.1   33.54
  5203.4   32.56  5589.6   33.59    5600   33.55  5699.6    33.2  5859.6   32.93
  6199.6   32.32  6389.6   32.82  6789.6   32.42  6849.6   32.63  6859.6   34.03
  6869.6   34.56
BR U #Mann= 5
   869.8     .99    4500      .1 4980.44     .04 5018.14      .1    5600     .99
BR U Banks=4980.44,5018.14
BR D #Sta/Elev= 66
   869.8   36.23  1089.8   34.84  1149.8   35.28  1159.8   34.98  1329.8   35.33
  1419.8   34.92  1759.8   34.83  1899.8   33.83  2159.8   34.02  2449.8   33.91
  2509.8   33.21  2790.7   34.21  2880.7   33.43  3180.7    34.2  3600.7   33.73
  3990.7   33.36  4170.7   33.56  4310.7   33.85  4490.7   34.41    4500   34.27
  4534.2   33.77  4764.2   33.15  4913.3   32.61 4922.44   32.47 4922.54    32.8
 4945.54   32.58 4946.04    32.6 4970.54   32.34 4974.64   32.07 4980.44   30.35
 4985.64   28.07 4989.17   26.53 4989.26   26.49 4994.24   24.31 4994.34   24.22
 4995.34   23.72 4996.84   23.91 4999.44   22.74 4999.74   23.83 5002.04   23.26
 5004.14   23.92 5005.64   24.09 5006.64   24.08 5010.79    26.4  5010.9   26.46
 5015.54   29.06 5018.14   30.51 5025.04    32.9 5028.94   32.44 5046.94   34.04
 5048.94   33.75 5067.04   34.65 5068.94   34.52  5087.1   32.87  5117.1   33.53
  5203.4   32.55  5589.6   33.58    5600   33.54  5699.6   33.19  5859.6   32.92
  6199.6   32.31  6389.6   32.81  6789.6   32.41  6849.6   32.62  6859.6   34.02
  6869.6   34.55
BR D #Mann= 5
   869.8     .99    4500      .1 4980.44     .04 5018.14      .1    5600     .99
BR D Banks=4980.44,5018.14
BC Design=,, 0 ,, 0 ,,,,,,
BC HTab HWMax=36.54
BC Use User HTab Curves=0
BC User HTab FreeFlow(D)= 0

Type RM Length L Ch R = 1 ,27870.4 ,188.5,153.7,76.3
BEGIN DESCRIPTION:
Downstream Section of Bridge/Culvert/Weir
END DESCRIPTION:
XS GIS Cut Line= 6
      3165305.88     13797248.02      3166378.79     13798684.33
      3167883.08     13800374.63      3167916.22     13800487.04
      3168454.42     13800642.72      3169512.78     13801317.04
#Sta/Elev= 30
   869.8   36.13  1089.8   34.74  1329.8   35.23  2449.8   33.81  2509.8   33.11
  2790.7   34.11  2880.7   33.33  3180.7    34.1  3990.7   33.26    4500   34.17
 4922.54    32.7 4970.54   32.24 4980.44   30.25 4995.34   23.62 4999.44   22.64
 4999.74   23.73 5002.04   23.16 5006.64   23.98 5018.14   30.41 5025.04    32.8
 5028.94   32.34 5067.04   34.55  5087.1   32.77  5117.1   33.43  5203.4   32.45
    5600   33.44  6199.6   32.21  6789.6   32.31  6849.6   32.52  6869.6   34.45
#Mann= 5 ,-1 , 0
   869.8     .99       0    4500      .1       0 4980.44     .04       0
 5018.14      .1       0    5600     .99       0
#XS Ineff= 2 , 0
       0 4983.57      29 5015.54       0      29
Permanent Ineff=
       F       F
Bank Sta=4980.44,5018.14
XS Rating Curve= 0 ,0
Exp/Cntr=0.5,0.3

Type RM Length L Ch R = 1 ,27716.7 ,94.3,101.7,20.1
BEGIN DESCRIPTION:
Cross Section 27716.7-Interpolated
END DESCRIPTION:
XS GIS Cut Line= 6
       3165022.9     13799026.76      3167005.73     13800102.13
      3167698.53     13800550.66      3167915.38     13800565.72
      3168439.41     13800662.09      3169530.15     13801354.97
#Sta/Elev= 30
  1761.7    35.4  2831.7    34.4  2931.7    34.8  3021.7    33.8  3153.9      34
  4902.8    33.9  4932.8    33.5  4952.8    32.2  4962.8    30.5  4972.8    27.6
  4982.8    25.4  4992.8      24  4993.6   21.76  4996.6   21.12  5004.2   21.12
  5009.3   23.09  5027.8   32.25  5042.8    34.7  5060.2    34.3  5150.2    33.9
  5160.2    33.6  5180.2    32.1  5190.2    31.8    5593    33.2    5773    32.1
    6000    32.1  6215.2    32.1  6475.2      33  6805.2    32.6  6885.2    34.6
#Mann= 4 , 1 , 0
  1761.7      .1       0  4952.8     .04       0  5027.8      .1       0
    6000     .99       0
Bank Sta=4952.8,5027.8
XS Rating Curve= 0 ,0
Exp/Cntr=0.5,0.3

Type RM Length L Ch R = 1 ,27615.0 ,53,53,53
BEGIN DESCRIPTION:
Upstream Section of Bridge/Culvert/Weir
END DESCRIPTION:
XS GIS Cut Line= 6
      3164940.36     13800516.12      3167091.66     13800626.09
      3167804.46     13800664.83      3167907.85     13800670.65
      3168429.45     13800698.79      3169519.83     13801382.93
#Sta/Elev= 30
  2080.6    34.6  2080.7    33.2  2690.7    31.8  4000.7    33.2    4500   31.79
  4824.2   31.01  4915.1   31.59    4967   32.48  4973.8   30.97  4993.6   20.76
  4996.6   20.12  5004.2   20.12  5009.3   22.09  5027.8   31.25  5071.2   32.53
  5116.7   32.38  5149.9    30.7  5191.7    30.5  5571.7    33.1  5741.7    32.3
  6121.7    32.4  6241.7    30.3  6301.7      31  6331.7    32.8    6580   34.04
  6791.7    32.5  6801.7    31.3  6811.7    30.9  6841.7    34.3  6861.7    34.7
#Mann= 5 ,-1 , 0
  2080.6     .99       0    4500      .1       0  4973.8    .015       0
  5027.8      .1       0    6580     .99       0
#XS Ineff= 2 , 0
       0  4974.7    30.4  5026.2       0    30.4
Permanent Ineff=
       F       F
Bank Sta=4973.8,5027.8
XS Rating Curve= 0 ,0
Exp/Cntr=0.5,0.3