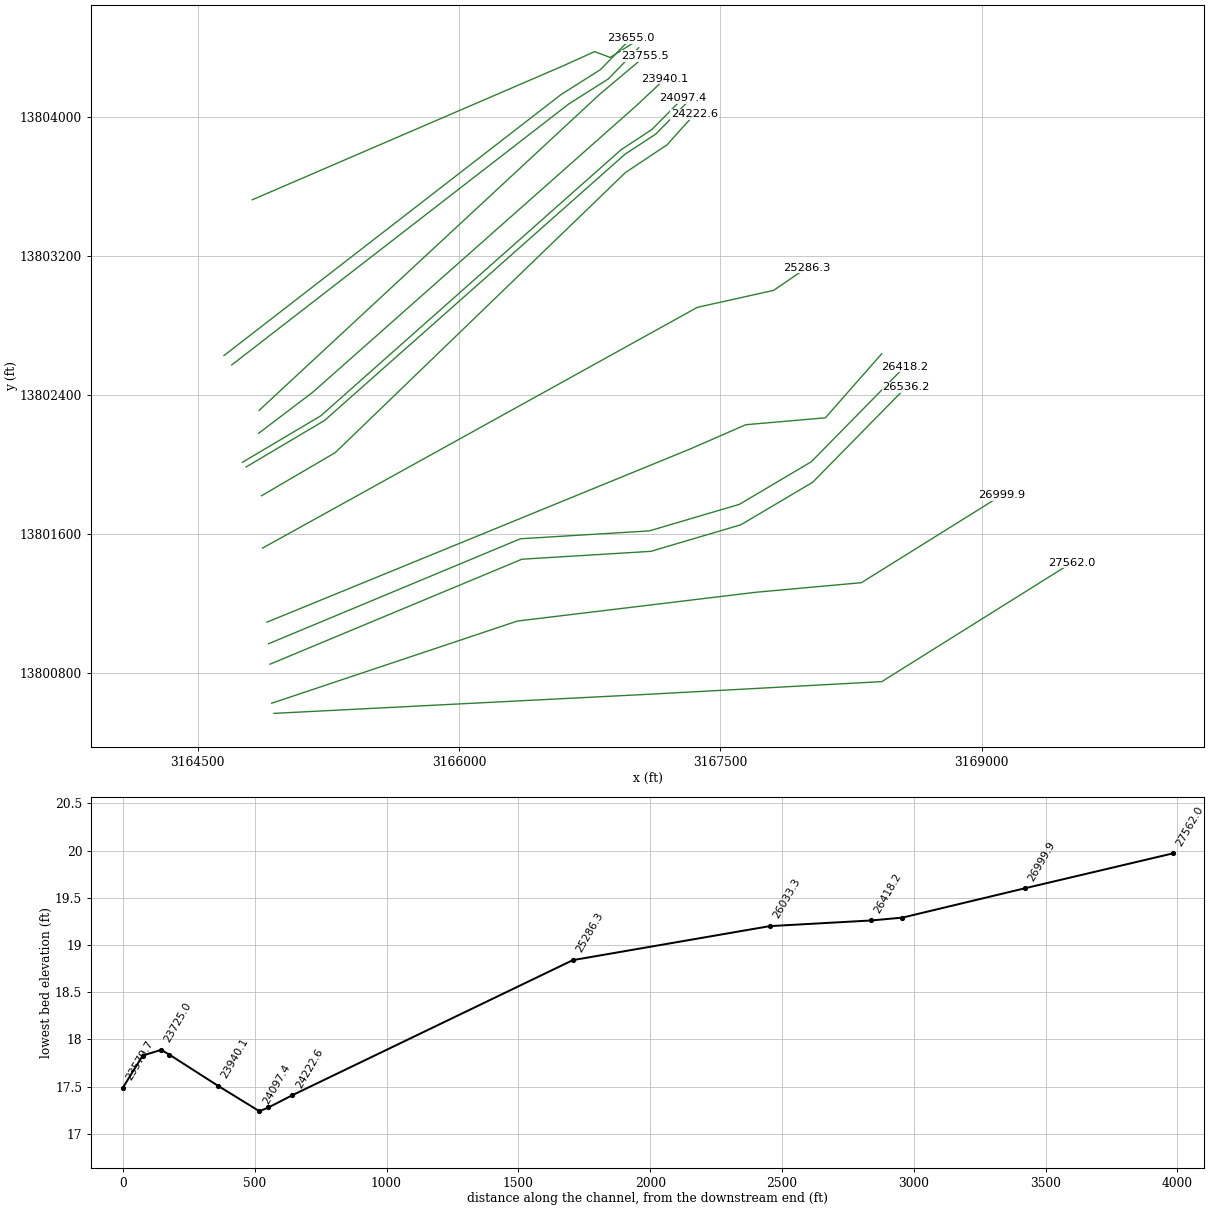
HEC-RAS study C106-00-00.PRJ: C106-00-00 2015

--- C106-00-00.g01 (geometry) --- (continued)

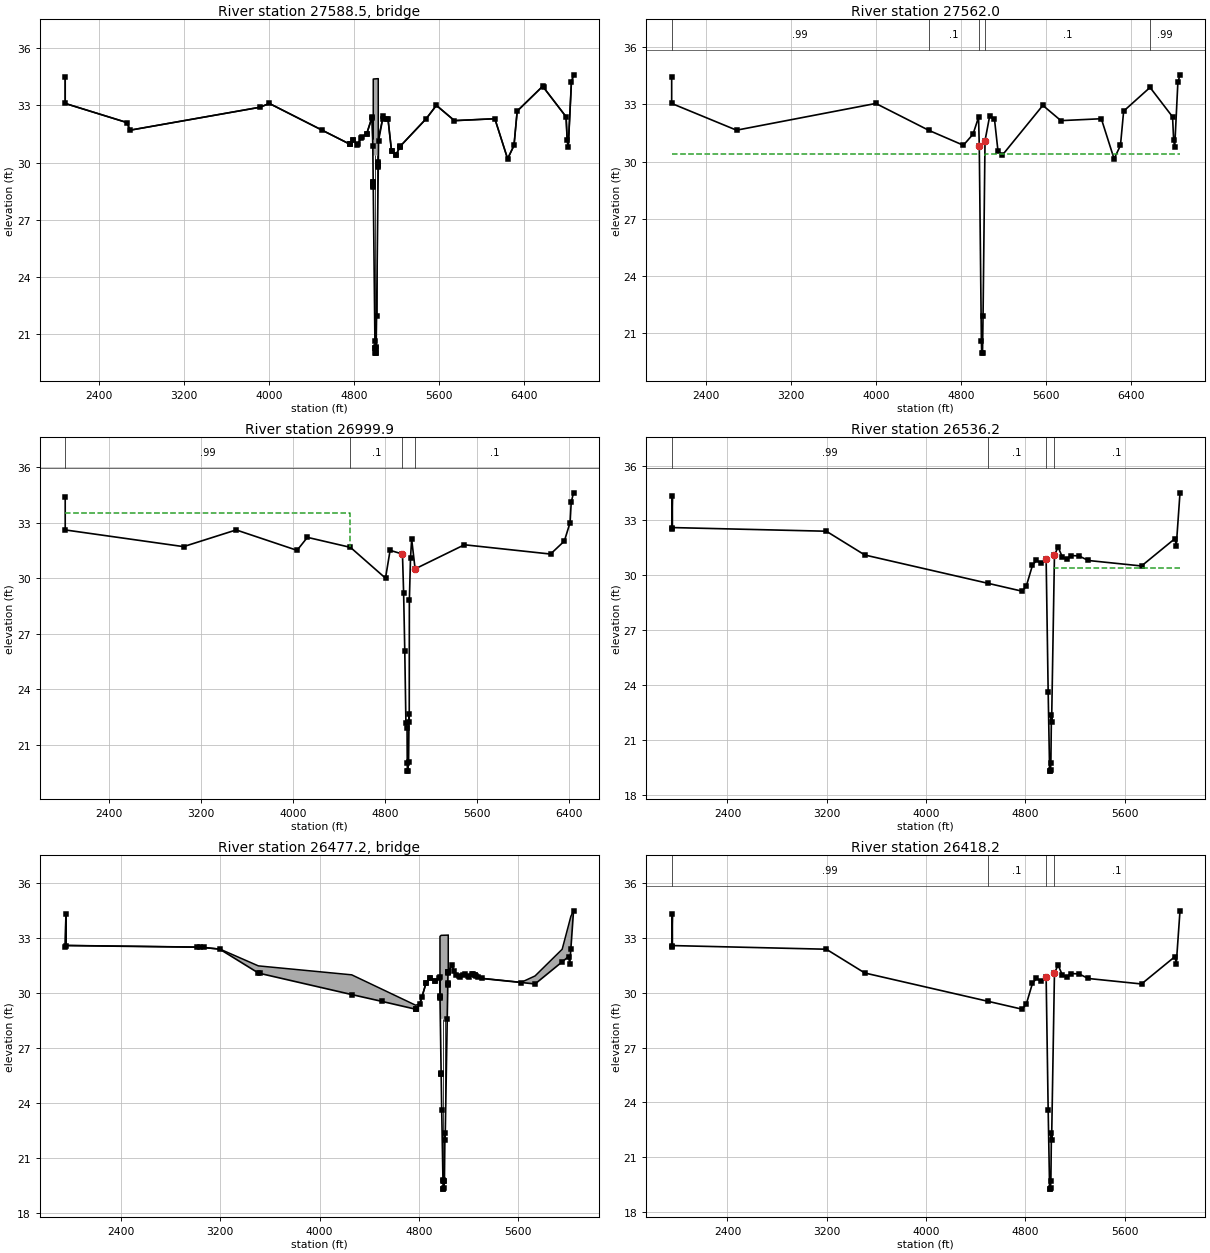
Type RM Length L Ch R = 3 ,27588.5 ,,,
BEGIN DESCRIPTION:
GILPIN STREET
Structure ID: C06-20
END DESCRIPTION:
Node Name=GILPIN STREET
Bridge Culvert--1,0,-1,-1, 0
Deck Dist Width WeirC Skew NumUp NumDn MinLoCord MaxHiCord MaxSubmerge Is_Ogee
10,33,2.6,0, 40, 40, , , 0.95, 0, 1,1,,
  2080.6  2080.7  2660.7  2690.7  3910.7  4000.7    4760  4791.4  4824.2  4869.4
  4915.1    4967  4973.8 4977.51  4977.6 4977.79  4977.9  5025.1 5025.21 5025.29
  5025.4  5027.8  5071.2  5116.7  5149.9  5191.7  5231.9  5475.9  5571.7  5741.7
  6121.7  6241.7  6301.7  6331.7  6571.7  6791.7  6801.7  6811.7  6841.7  6861.7
    34.5    33.1    32.1    31.7    32.9    33.1   30.96   31.22   30.92   31.34
    31.5   32.39   31.22   31.28   31.28   31.28   34.38    34.4    31.3    31.3
    31.3   31.29   32.44   32.29   30.61   30.41   30.86    32.3      33    32.2
    32.3    30.2    30.9    32.7      34    32.4    31.2    30.8    34.2    34.6
    34.5    33.1    32.1    31.7    32.9    33.1   30.96   31.21   30.91   31.33
   31.49   32.38   30.87   28.96   30.37   30.37   30.37   30.39   30.39   30.39
   29.96   31.15   32.43   32.28    30.6    30.4   30.86    32.3      33    32.2
    32.3    30.2    30.9    32.7      34    32.4    31.2    30.8    34.2    34.6
  2080.6  2080.7  2660.7  2690.7  3910.7  4000.7    4760  4791.4  4824.2  4869.4
  4915.1    4967  4973.8 4977.51  4977.6 4977.79  4977.9  5025.1 5025.21 5025.29
  5025.4  5027.8  5071.2  5116.7  5149.9  5191.7  5231.9  5475.9  5571.7  5741.7
  6121.7  6241.7  6301.7  6331.7  6571.7  6791.7  6801.7  6811.7  6841.7  6861.7
    34.5    33.1    32.1    31.7    32.9    33.1   30.96   31.22   30.92   31.34
    31.5   32.39   31.22   31.28   31.28   31.28   34.38    34.4    31.3    31.3
    31.3   31.29   32.44   32.29   30.61   30.41   30.86    32.3      33    32.2
    32.3    30.2    30.9    32.7      34    32.4    31.2    30.8    34.2    34.6
   34.46   33.06   32.06   31.66   32.86   33.06   30.92   31.17   30.87   31.29
   31.45   32.34   30.83   28.92   30.33   30.33   30.33   30.35   30.35   30.35
   29.92   31.11   32.39   32.24   30.56   30.36   30.82   32.26   32.96   32.16
   32.26   30.16   30.86   32.66   33.96   32.36   31.16   30.76   34.16   34.56
Pier Skew, UpSta & Num, DnSta & Num=  ,4993.6, 2 ,4993.6, 2 , 0 , 0 , 0 ,,
     1.4     1.4
   19.47   31.38
     1.4     1.4
   19.43   31.34
Pier Skew, UpSta & Num, DnSta & Num=  ,5009.3, 2 ,5009.3, 2 , 0 , 0 , 0 ,,
     1.4     1.4
   20.73   31.38
     1.4     1.4
   20.69   31.34
Abutment Skew #Up #Dn= , 2 , 2
  4977.4    4995
   30.37   20.27
  4977.4    4995
   30.33   20.23
Abutment Skew #Up #Dn= , 2 , 2
  5004.9 5025.49
   20.34   30.39
  5004.9 5025.49
    20.3   30.35
BR Coef= 1 , 1 , 0 ,1.25, 0 ,,,0.8,0,2,0,
WSPro=,,,, 1 ,,,, 0 ,,,, 0 ,,,,-1 ,-1 ,-1 , 0 , 0 , 0 , 0 , 0
BR U #Sta/Elev= 68
  2080.6    34.5  2080.7    33.1  2660.7    32.1  2690.7    31.7  3910.7    32.9
  4000.7    33.1    4500   31.69    4760   30.96  4760.1   30.96  4760.5   30.96
  4789.8    31.2  4791.4   31.21  4824.2   30.91    4830   30.96  4864.5   31.28
  4869.4   31.33  4915.1   31.49  4915.8    31.5    4967   32.38  4967.2   32.34
  4973.8   30.87  4977.4   29.01 4977.51   28.96  4977.6   28.91 4977.79   28.81
  4977.9   28.76 4978.01    28.7  4993.6   20.66  4994.9    20.3    4995   20.27
  4996.6   20.02  4999.8   20.02  5004.2   20.02  5004.8    20.3  5004.9   20.34
  5009.3   21.99 5024.99   29.76  5025.1   29.81 5025.21   29.87 5025.29   29.91
  5025.4   29.96  5025.5   30.01  5027.8   31.15  5067.3   32.31  5071.2   32.43
  5109.7    32.3  5116.7   32.28  5149.9    30.6  5152.1   30.59  5191.7    30.4
  5192.3   30.41  5231.7   30.84  5231.8   30.84  5231.9   30.86  5475.9    32.3
  5571.7      33  5741.7    32.2  6121.7    32.3  6241.7    30.2  6301.7    30.9
  6331.7    32.7  6571.7      34    6580   33.94  6791.7    32.4  6801.7    31.2
  6811.7    30.8  6841.7    34.2  6861.7    34.6
BR U #Mann= 5
  2080.6     .99    4500      .1  4973.8    .015  5027.8      .1    6580     .99
BR U Banks=4973.8,5027.8
BR D #Sta/Elev= 68
  2080.6   34.46  2080.7   33.06  2660.7   32.06  2690.7   31.66  3910.7   32.86
  4000.7   33.06    4500   31.65    4760   30.92  4760.1   30.92  4760.5   30.92
  4789.8   31.16  4791.4   31.17  4824.2   30.87    4830   30.92  4864.5   31.24
  4869.4   31.29  4915.1   31.45  4915.8   31.46    4967   32.34  4967.2    32.3
  4973.8   30.83  4977.4   28.97 4977.51   28.92  4977.6   28.87 4977.79   28.77
  4977.9   28.72 4978.01   28.66  4993.6   20.62  4994.9   20.26    4995   20.23
  4996.6   19.98  4999.8   19.98  5004.2   19.98  5004.8   20.26  5004.9    20.3
  5009.3   21.95 5024.99   29.72  5025.1   29.77 5025.21   29.83 5025.29   29.87
  5025.4   29.92  5025.5   29.97  5027.8   31.11  5067.3   32.27  5071.2   32.39
  5109.7   32.26  5116.7   32.24  5149.9   30.56  5152.1   30.55  5191.7   30.36
  5192.3   30.37  5231.7    30.8  5231.8    30.8  5231.9   30.82  5475.9   32.26
  5571.7   32.96  5741.7   32.16  6121.7   32.26  6241.7   30.16  6301.7   30.86
  6331.7   32.66  6571.7   33.96    6580    33.9  6791.7   32.36  6801.7   31.16
  6811.7   30.76  6841.7   34.16  6861.7   34.56
BR D #Mann= 5
  2080.6     .99    4500      .1  4973.8    .015  5027.8      .1    6580     .99
BR D Banks=4973.8,5027.8
BC Design=,, 0 ,, 0 ,,,,,,
BC HTab HWMax=34.7
BC Use User HTab Curves=0
BC User HTab FreeFlow(D)= 0

Type RM Length L Ch R = 1 ,27562.0 ,532.9,562.1,567.4
BEGIN DESCRIPTION:
Downstream Section of Bridge/Culvert/Weir
END DESCRIPTION:
XS GIS Cut Line= 6
      3164937.66     13800569.05      3167088.96     13800679.03
      3167801.76     13800717.77      3167905.15     13800723.59
      3168426.75     13800751.73      3169517.12     13801435.86
#Sta/Elev= 30
  2080.6   34.45  2080.7   33.05  2690.7   31.65  4000.7   33.05    4500   31.64
  4824.2   30.86  4915.1   31.44    4967   32.33  4973.8   30.82  4993.6   20.61
  4996.6   19.97  5004.2   19.97  5009.3   21.94  5027.8    31.1  5071.2   32.38
  5116.7   32.23  5149.9   30.55  5191.7   30.35  5571.7   32.95  5741.7   32.15
  6121.7   32.25  6241.7   30.15  6301.7   30.85  6331.7   32.65    6580   33.89
  6791.7   32.35  6801.7   31.15  6811.7   30.75  6841.7   34.15  6861.7   34.55
#Mann= 5 ,-1 , 0
  2080.6     .99       0    4500      .1       0  4973.8    .015       0
  5027.8      .1       0    6580     .99       0
#XS Ineff= 2 , 0
       0  4974.7    30.4  5026.2       0    30.4
Permanent Ineff=
       F       F
Bank Sta=4973.8,5027.8
XS Rating Curve= 0 ,0
Exp/Cntr=0.5,0.3

Type RM Length L Ch R = 1 ,26999.9 ,199.7,463.7,661.6
BEGIN DESCRIPTION:
Cross Section 26999.9-Interpolated
END DESCRIPTION:
XS GIS Cut Line= 5
       3164924.2     13800627.36      3166335.35     13801100.46
      3167703.08     13801265.91      3168309.73     13801321.06
      3169115.31     13801824.51
#Sta/Elev= 30
  2016.6    34.4  2016.7    32.6  3046.7    31.7    3505    32.6    4035    31.5
    4125    32.2    4500   31.66    4805      30    4845    31.5  4952.7    31.3
  4962.7    29.2  4972.7    26.1  4982.7    22.2  4992.7    21.9 4994.18   20.05
 4995.48   19.62 4998.28    19.6 5005.78   20.07 5009.98   22.67 5011.58   22.26
  5012.7    28.8  5022.7    31.1  5032.7    32.1  5062.7    30.5  5491.9    31.8
  6241.9    31.3  6361.9      32  6411.9      33  6421.9    34.1  6441.9    34.6
#Mann= 4 ,-1 , 0
  2016.6     .99       0    4500      .1       0  4952.7    .015       0
  5062.7      .1       0
#XS Ineff= 2 , 0
       0    4500    33.5               0
Permanent Ineff=
       F       F
Bank Sta=4952.7,5062.7
XS Rating Curve= 0 ,0
Exp/Cntr=0.5,0.3

Type RM Length L Ch R = 1 ,26536.2 ,5118,118,118
BEGIN DESCRIPTION:
Upstream Section of Bridge/Culvert/Weir
END DESCRIPTION:
XS GIS Cut Line= 6
      3164914.91      13800852.1      3166360.72     13801456.16
      3167100.93     13801501.46      3167618.17     13801654.43
      3168030.53     13801899.25      3168566.15     13802445.71
#Sta/Elev= 30
  1950.4   32.51  1956.1   34.31  1956.2   32.61  3196.5   32.41  3506.5   31.11
    4500   29.56    4774   29.13  4807.3    29.4  4857.6   30.55  4889.6   30.81
  4929.8   30.66  4967.5    30.9  4983.9   23.62  4995.5   19.31  4998.3   19.29
  5002.7   19.34  5005.8   19.76    5010   22.36  5011.6   21.95  5034.6   31.11
    5064   31.54  5098.2      31  5132.3   30.89  5168.9   31.08  5232.7   31.06
  5306.3   30.81  5736.1   30.51  6006.1   32.01  6016.1   31.61  6046.1   34.51
#Mann= 4 ,-1 , 0
  1950.4     .99       0    4500      .1       0  4967.5    .015       0
  5034.6      .1       0
#XS Ineff= 2 , 0
       0    4971    29.3  5032.7       0    30.4
Permanent Ineff=
       F       F
Bank Sta=4967.5,5034.6
XS Rating Curve= 0 ,0
Exp/Cntr=0.5,0.3

Type RM Length L Ch R = 3 ,26477.2 ,,,
BEGIN DESCRIPTION:
EDGEBROOK DRIVE
Structure ID: C06-19
END DESCRIPTION:
Node Name=EDGEBROOK DRIVE
Bridge Culvert--1,0,-1,-1, 0
Deck Dist Width WeirC Skew NumUp NumDn MinLoCord MaxHiCord MaxSubmerge Is_Ogee
10,98,2.6,0, 36, 36, , , 0.95, 0, 1,1,,
  1950.4  1956.1  1956.2  3010.4  3196.5  3506.5  4258.9  4773.3  4807.3  4857.6
  4889.6  4929.8  4964.1  4967.5 4969.89    4970 4979.41  4979.5  5028.4  5034.6
  5036.7 5036.81    5064  5098.2  5132.3  5168.9  5201.7  5232.7  5306.3  5624.6
  5736.1  5954.6  6006.1  6016.1  6024.6  6046.1
    32.5   34.31   32.61   32.52   32.41   31.49      31   29.34    29.4   30.55
   30.81   30.66   30.82    30.9    29.9    33.1   33.16   33.16   33.17   33.17
   33.18   31.14   31.54      31   30.89   31.08   30.88   31.06   30.81   30.59
   30.94    32.4   33.72   33.98    34.2    34.5
    32.5    34.3    32.6   32.51    32.4    31.1   29.92   29.12   29.39   30.54
    30.8   30.65   30.81   30.89   29.83   29.78    25.6   28.59    28.6    31.1
   31.13   31.13   31.53   30.99   30.88   31.07   30.87   31.05    30.8   30.58
    30.5   31.71      32    31.6   32.42    34.5
  1950.4  1956.1  1956.2  3010.4  3196.5  3506.5  4258.9  4773.3  4807.3  4857.6
  4889.6  4929.8  4964.1  4967.5 4969.89    4970 4979.41  4979.5  5028.4  5034.6
  5036.7 5036.81    5064  5098.2  5132.3  5168.9  5201.7  5232.7  5306.3  5624.6
  5736.1  5954.6  6006.1  6016.1  6024.6  6046.1
    32.5   34.31   32.61   32.52   32.41   31.49      31   29.34    29.4   30.55
   30.81   30.66   30.82    30.9    29.9    33.1   33.16   33.16   33.17   33.17
   33.18   31.14   31.54      31   30.89   31.08   30.88   31.06   30.81   30.59
   30.94    32.4   33.72   33.98    34.2    34.5
   32.48   34.28   32.58   32.49   32.38   31.08    29.9    29.1   29.37   30.52
   30.78   30.63   30.79   30.87   29.81   29.76   25.58   28.57   28.58   31.08
   31.11   31.11   31.51   30.97   30.86   31.05   30.85   31.03   30.78   30.56
   30.48   31.69   31.98   31.58    32.4   34.48
Pier Skew, UpSta & Num, DnSta & Num=  ,4994.2, 2 ,4994.2, 2 , 0 , 0 , 0 ,,
     1.3     1.3
   18.52   29.59
     1.3     1.3
    18.5   29.57
Pier Skew, UpSta & Num, DnSta & Num=  ,5011.6, 2 ,5011.6, 2 , 0 , 0 , 0 ,,
     1.3     1.3
   21.11    29.6
     1.3     1.3
   21.09   29.58
Abutment Skew #Up #Dn= , 2 , 2
  4979.3  4994.2
   28.59   19.73
  4979.3  4994.2
   28.57   19.71
Abutment Skew #Up #Dn= , 2 , 2
  5005.8 5033.19
   19.75   30.45
  5005.8 5033.19
   19.73   30.43
BR Coef= 1 , 1 , 0 ,1.25, 0 ,,,0.8,0,2,0,
WSPro=,,,, 1 ,,,, 0 ,,,, 0 ,,,,-1 ,-1 ,-1 , 0 , 0 , 0 , 0 , 0
BR U #Sta/Elev= 71
  1950.4    32.5  1956.1    34.3  1956.2    32.6  3010.4   32.51  3040.4    32.5
  3066.2    32.5  3196.5    32.4  3506.5    31.1  3517.3   31.08  4258.9   29.92
    4500   29.55  4773.3   29.12  4773.9   29.12    4774   29.12  4807.3   29.39
  4824.8   29.79  4857.6   30.54    4859   30.55  4889.6    30.8    4890    30.8
    4929   30.65  4929.8   30.65  4964.1   30.81  4967.5   30.89 4969.89   29.83
    4970   29.78 4970.11   29.73  4979.3   25.65 4979.41    25.6  4979.5   25.56
  4983.9   23.61  4994.1   19.77  4994.2   19.73  4995.5    19.3  4998.3   19.28
  5002.7   19.33  5005.7   19.74  5005.8   19.75    5010   22.35  5011.6   21.94
  5028.4    28.6 5032.99   30.45  5033.1    30.5  5033.2   30.54  5034.6    31.1
 5036.59   31.13  5036.7   31.13 5036.81   31.13    5064   31.53    5085    31.2
  5098.2   30.99  5120.3   30.92  5132.3   30.88  5157.5   31.01  5168.9   31.07
  5192.4   30.93  5201.7   30.87  5230.1   31.03  5232.7   31.05  5252.8   30.99
  5252.9   30.99  5262.4   30.96  5279.8   30.89  5306.3    30.8  5624.6   30.58
  5736.1    30.5  5954.6   31.71  6006.1      32  6016.1    31.6  6024.6   32.42
  6046.1    34.5
BR U #Mann= 4
  1950.4     .99    4500      .1  4967.5    .015  5034.6      .1
BR U Banks=4967.5,5034.6
BR D #Sta/Elev= 71
  1950.4   32.48  1956.1   34.28  1956.2   32.58  3010.4   32.49  3040.4   32.48
  3066.2   32.48  3196.5   32.38  3506.5   31.08  3517.3   31.06  4258.9    29.9
    4500   29.53  4773.3    29.1  4773.9    29.1    4774    29.1  4807.3   29.37
  4824.8   29.77  4857.6   30.52    4859   30.53  4889.6   30.78    4890   30.78
    4929   30.63  4929.8   30.63  4964.1   30.79  4967.5   30.87 4969.89   29.81
    4970   29.76 4970.11   29.71  4979.3   25.63 4979.41   25.58  4979.5   25.54
  4983.9   23.59  4994.1   19.75  4994.2   19.71  4995.5   19.28  4998.3   19.26
  5002.7   19.31  5005.7   19.72  5005.8   19.73    5010   22.33  5011.6   21.92
  5028.4   28.58 5032.99   30.43  5033.1   30.48  5033.2   30.52  5034.6   31.08
 5036.59   31.11  5036.7   31.11 5036.81   31.11    5064   31.51    5085   31.18
  5098.2   30.97  5120.3    30.9  5132.3   30.86  5157.5   30.99  5168.9   31.05
  5192.4   30.91  5201.7   30.85  5230.1   31.01  5232.7   31.03  5252.8   30.97
  5252.9   30.97  5262.4   30.94  5279.8   30.87  5306.3   30.78  5624.6   30.56
  5736.1   30.48  5954.6   31.69  6006.1   31.98  6016.1   31.58  6024.6    32.4
  6046.1   34.48
BR D #Mann= 4
  1950.4     .99    4500      .1  4967.5    .015  5034.6      .1
BR D Banks=4967.5,5034.6
BC Design=,, 0 ,, 0 ,,,,,,
BC HTab HWMax=34.51
BC Use User HTab Curves=0
BC User HTab FreeFlow(D)= 0

Type RM Length L Ch R = 1 ,26418.2 ,420.4,384.9,348.8
BEGIN DESCRIPTION:
Downstream Section of Bridge/Culvert/Weir
END DESCRIPTION:
XS GIS Cut Line= 6
      3164906.57      13800969.8      3166352.38     13801573.86
      3167092.59     13801619.16      3167609.83     13801772.13
      3168022.19     13802016.95       3168557.8     13802563.42
#Sta/Elev= 30
  1950.4   32.48  1956.1   34.28  1956.2   32.58  3196.5   32.38  3506.5   31.08
    4500   29.53    4774    29.1  4807.3   29.37  4857.6   30.52  4889.6   30.78
  4929.8   30.63  4967.5   30.87  4983.9   23.59  4995.5   19.28  4998.3   19.26
  5002.7   19.31  5005.8   19.73    5010   22.33  5011.6   21.92  5034.6   31.08
    5064   31.51  5098.2   30.97  5132.3   30.86  5168.9   31.05  5232.7   31.03
  5306.3   30.78  5736.1   30.48  6006.1   31.98  6016.1   31.58  6046.1   34.48
#Mann= 4 ,-1 , 0
  1950.4     .99       0    4500      .1       0  4967.5    .015       0
  5034.6      .1       0
#XS Ineff= 2 , 0
       0    4971    29.1  5032.7       0    30.2
Permanent Ineff=
       F       F
Bank Sta=4967.5,5034.6
XS Rating Curve= 0 ,0
Exp/Cntr=0.5,0.3

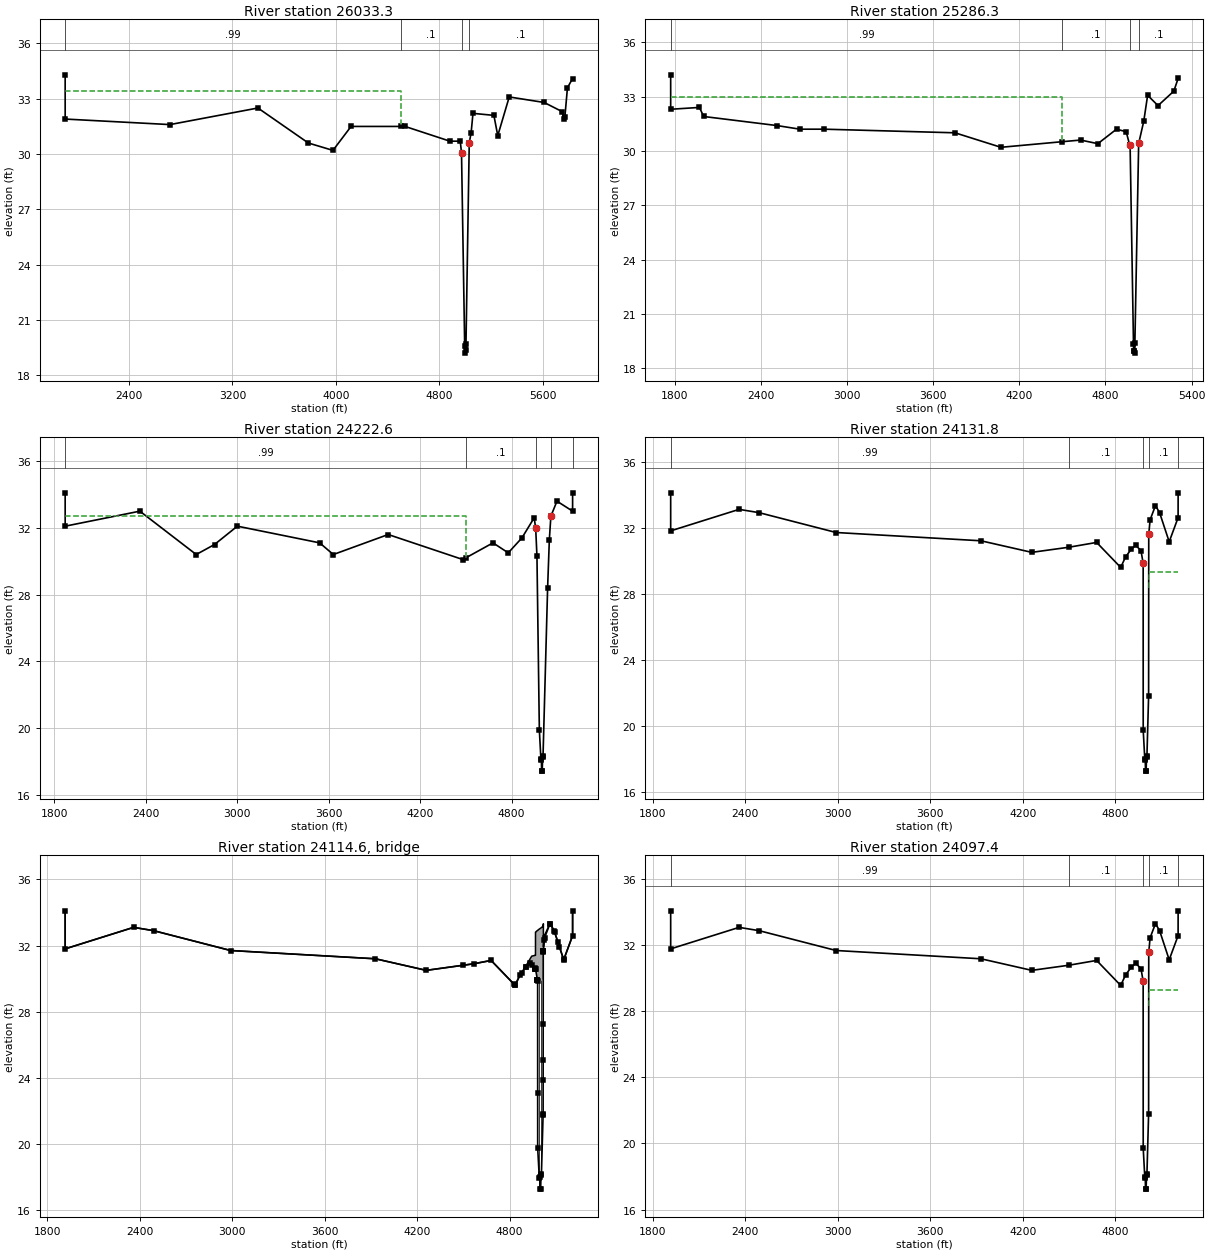
Type RM Length L Ch R = 1 ,26033.3 ,684.5,747,787.2
BEGIN DESCRIPTION:
Cross Section 26033.3
END DESCRIPTION:
XS GIS Cut Line= 5
      3164897.59     13801094.09      3167328.27     13802091.13
      3167646.08     13802230.17      3168102.94      13802269.9
      3168426.16     13802638.19
#Sta/Elev= 28
  1906.5    34.3  1906.6    31.9  2716.6    31.6  3396.6    32.5  3786.6    30.6
  3976.6    30.2  4116.6    31.5    4500    31.5  4533.8    31.5  4880.7    30.7
  4960.7    30.7  4970.4   30.07    4995   19.59  4999.4    19.2  5004.6   19.37
    5005   19.72  5030.3   30.62  5044.9   31.16    5059   32.21  5220.7    32.1
  5250.7      31  5339.3    33.1  5609.3    32.8  5749.3    32.3  5759.3    31.9
  5769.3      32  5789.3    33.6  5829.3    34.1
#Mann= 4 ,-1 , 0
  1906.5     .99       0    4500      .1       0  4970.4    .015       0
  5030.3      .1       0
#XS Ineff= 2 , 0
       0    4500    33.4               0
Permanent Ineff=
       F       F
Bank Sta=4970.4,5030.3
XS Rating Curve= 0 ,0
Exp/Cntr=0.3,0.1

Type RM Length L Ch R = 1 ,25286.3 ,691.3,1063.7,1087.6
BEGIN DESCRIPTION:
Cross Section 25286.3
END DESCRIPTION:
XS GIS Cut Line= 4
      3164871.93     13801520.14        3167368.     13802905.52
      3167806.28     13803003.29      3167995.72     13803133.72
#Sta/Elev= 27
    1772    34.2  1772.1    32.3  1972.1    32.4  2002.1    31.9  2512.1    31.4
  2672.1    31.2  2842.1    31.2  3752.1      31  4072.1    30.2    4500   30.51
  4626.9    30.6  4746.9    30.4  4876.9    31.2  4944.1   31.06  4968.8   30.32
  4971.4   30.35  4995.1   19.33  4995.2   18.98  4999.9   18.93  5004.7   18.84
  5004.8    19.4  5031.1   30.41  5066.8   31.65  5093.5   33.07  5165.9    32.5
  5275.9    33.3  5305.9      34
#Mann= 4 ,-1 , 0
    1772     .99       0    4500      .1       0  4971.4    .015       0
  5031.1      .1       0
#XS Ineff= 2 , 0
       0    4500      33               0
Permanent Ineff=
       F       F
Bank Sta=4971.4,5031.1
XS Rating Curve= 0 ,0
Exp/Cntr=0.3,0.1

Type RM Length L Ch R = 1 ,24222.6 ,110.6,90.8,87.5
BEGIN DESCRIPTION:
Cross Section 24222.6-Interpolated
END DESCRIPTION:
XS GIS Cut Line= 6
      3164866.35     13801821.54      3165289.15     13802069.38
      3166955.15     13803681.14      3167194.92     13803841.31
      3167248.79     13803902.36      3167351.14     13804015.48
#Sta/Elev= 30
  1870.4    34.1  1870.5    32.1  2360.6      33  2730.6    30.4  2850.6      31
  3000.6    32.1  3540.6    31.1  3630.6    30.4  3990.6    31.6  4480.6    30.1
    4500    30.2  4678.6    31.1  4778.6    30.5  4868.6    31.4  4948.6    32.6
  4958.6      32    4967    30.3  4982.7   19.89  4993.3   18.07  4995.8   18.16
  4997.7   17.44  5001.5   17.41  5004.3   18.27  5006.9   18.32    5037    28.4
  5048.4    31.3  5058.4    32.7  5098.4    33.6    5201      33  5201.1    34.1
#Mann= 5 ,-1 , 0
  1870.4     .99       0    4500      .1       0  4958.6    .015       0
  5058.4      .1       0    5201      .2       0
#XS Ineff= 2 , 0
       0    4500    32.7               0
Permanent Ineff=
       F       F
Bank Sta=4958.6,5058.4
XS Rating Curve= 0 ,0
Exp/Cntr=0.5,0.3

Type RM Length L Ch R = 1 ,24131.8 ,34.4,34.4,34.4
BEGIN DESCRIPTION:
Upstream Section of Bridge/Culvert/Weir
END DESCRIPTION:
XS GIS Cut Line= 5
      3164777.99     13801987.13      3165228.12     13802254.81
      3166952.22     13803786.13      3167128.76     13803902.31
       3167306.9     13804082.65
#Sta/Elev= 30
  1914.9   34.11    1915   31.81  2359.2   33.11  2489.2   32.91  2989.2   31.71
  3929.2   31.21  4259.2   30.51    4500   30.82  4680.3   31.11  4836.5    29.6
  4868.7   30.24  4905.7   30.71  4934.2   30.93  4968.1   30.62  4982.4   29.85
  4982.7   19.76  4993.3   17.94  4995.8   18.03  4997.7   17.31  5001.5   17.28
  5004.3   18.14  5006.9   18.19  5017.8   21.83  5018.7    31.6  5027.5   32.48
  5062.5   33.34  5089.5    32.9  5151.4   31.15  5209.3   32.61  5209.4   34.11
#Mann= 5 ,-1 , 0
  1914.9     .99       0    4500      .1       0  4982.4    .015       0
  5018.7      .1       0  5209.3      .2       0
#XS Ineff= 2 , 0
       0  4982.4    29.6  5018.4       0    29.3
Permanent Ineff=
       F       F
Bank Sta=4982.4,5018.7
XS Rating Curve= 0 ,0
Exp/Cntr=0.5,0.3

Type RM Length L Ch R = 3 ,24114.6 ,,,
BEGIN DESCRIPTION:
LAVAUN ROAD
Structure ID: C06-18
END DESCRIPTION:
Node Name=LAVAUN ROAD
Bridge Culvert--1,0,-1,-1, 0
Deck Dist Width WeirC Skew NumUp NumDn MinLoCord MaxHiCord MaxSubmerge Is_Ogee
10,14.4,2.6,0, 57, 57, , , 0.95, 0, 1,1,,
  1914.9    1915  2359.2  2489.2  2989.2  3929.2  4259.2    4500  4569.2  4680.3
  4826.7  4836.4  4836.5  4868.7  4878.2  4905.7  4905.8  4934.2  4943.9  4967.4
  4968.1 4968.29  4968.4 4968.51 4980.81  4980.9  4981.1  4982.4  4982.6  4982.7
  4993.3  4995.8  4997.7  5001.5  5004.3  5006.9  5017.6  5017.8 5017.99  5018.1
  5018.3  5018.7 5019.49  5019.6 5019.71  5026.4  5027.5  5062.1  5062.5  5089.5
  5092.3    5113  5124.1  5150.8  5151.4  5209.3  5209.4
    34.1    31.8    33.1    32.9    31.7    31.2    30.5   30.81    30.9    31.1
   29.69   29.63   29.63   30.24   30.36   30.76   30.76   31.21   31.36   31.41
   31.41   31.41   32.81   32.81   32.91   32.91   32.91   32.92   32.92   32.92
      33   33.01   33.03   33.05   33.07   33.09   33.17   33.17   33.17   33.17
   33.17   33.22   33.32   33.32   31.92    32.6   32.62   33.33   33.34    32.9
   32.82   32.24   31.92   31.17   31.14    32.6    34.1
    34.1    31.8    33.1    32.9    31.7    31.2    30.5   30.81    30.9    31.1
   29.68   29.59   29.59   30.23   30.35    30.7    30.7   30.92   30.83   30.62
   30.61    30.6   30.59   30.59   29.93   29.92   29.91   29.84   29.73   29.73
   29.81   29.82   29.84   29.86   29.88    29.9   29.98   29.98   29.98   25.08
   27.25   31.59   31.67   31.68   31.69   32.36   32.47   33.32   33.33   32.89
   32.81   32.23   31.91   31.16   31.14    32.6    34.1
  1914.9    1915  2359.2  2489.2  2989.2  3929.2  4259.2    4500  4569.2  4680.3
  4826.7  4836.4  4836.5  4868.7  4878.2  4905.7  4905.8  4934.2  4943.9  4967.4
  4968.1 4968.29  4968.4 4968.51 4980.81  4980.9  4981.1  4982.4  4982.6  4982.7
  4993.3  4995.8  4997.7  5001.5  5004.3  5006.9  5017.6  5017.8 5017.99  5018.1
  5018.3  5018.7 5019.49  5019.6 5019.71  5026.4  5027.5  5062.1  5062.5  5089.5
  5092.3    5113  5124.1  5150.8  5151.4  5209.3  5209.4
    34.1    31.8    33.1    32.9    31.7    31.2    30.5   30.81    30.9    31.1
   29.69   29.63   29.63   30.24   30.36   30.76   30.76   31.21   31.36   31.41
   31.41   31.41   32.81   32.81   32.91   32.91   32.91   32.92   32.92   32.92
      33   33.01   33.03   33.05   33.07   33.09   33.17   33.17   33.17   33.17
   33.17   33.22   33.32   33.32   31.92    32.6   32.62   33.33   33.34    32.9
   32.82   32.24   31.92   31.17   31.14    32.6    34.1
   34.05   31.75   33.05   32.85   31.65   31.15   30.45   30.76   30.85   31.05
   29.63   29.54   29.54   30.18    30.3   30.65   30.65   30.87   30.78   30.57
   30.56   30.55   30.54   30.54   29.88   29.87   29.86   29.79   29.68   29.68
   29.76   29.77   29.79   29.81   29.83   29.85   29.93   29.93   29.93   25.03
    27.2   31.54   31.62   31.63   31.64   32.31   32.42   33.27   33.28   32.84
   32.76   32.18   31.86   31.11   31.09   32.55   34.05
Pier Skew, UpSta & Num, DnSta & Num=  ,4993.2, 2 ,4993.2, 2 , 0 , 0 , 0 ,,
       1       1
   16.94   30.81
       1       1
   16.89   30.76
Pier Skew, UpSta & Num, DnSta & Num=  ,5006.8, 2 ,5006.8, 2 , 0 , 0 , 0 ,,
       1       1
   17.17    30.9
       1       1
   17.12   30.85
Abutment Skew #Up #Dn= , 2 , 2
  4980.7  4982.6
   29.92   23.11
  4980.7  4982.6
   29.87   23.06
BR Coef= 1 , 1 , 0 ,1.25, 0 ,,,0.8,0,2,0,
WSPro=,,,, 1 ,,,, 0 ,,,, 0 ,,,,-1 ,-1 ,-1 , 0 , 0 , 0 , 0 , 0
BR U #Sta/Elev= 57
  1914.9    34.1    1915    31.8  2359.2    33.1  2489.2    32.9  2989.2    31.7
  3929.2    31.2  4259.2    30.5    4500   30.81  4569.2    30.9  4680.3    31.1
  4826.7   29.68  4836.4   29.59  4836.5   29.59  4868.7   30.23  4878.2   30.35
  4905.7    30.7  4905.8    30.7  4934.2   30.92  4943.9   30.83  4967.4   30.62
  4968.1   30.61 4968.29    30.6  4968.4   30.59 4968.51   30.59 4980.81   29.93
  4980.9   29.92  4981.1   29.91  4982.4   29.84  4982.6   23.11  4982.7   19.75
  4993.3   17.93  4995.8   18.02  4997.7    17.3  5001.5   17.27  5004.3   18.13
  5006.9   18.18  5017.6   21.75  5017.8   21.82 5017.99   23.88  5018.1   25.08
  5018.3   27.25  5018.7   31.59 5019.49   31.67  5019.6   31.68 5019.71   31.69
  5026.4   32.36  5027.5   32.47  5062.1   33.32  5062.5   33.33  5089.5   32.89
  5092.3   32.81    5113   32.23  5124.1   31.91  5150.8   31.16  5151.4   31.14
  5209.3    32.6  5209.4    34.1
BR U #Mann= 5
  1914.9     .99    4500      .1  4982.4    .015  5018.7      .1  5209.3      .2
BR U Banks=4982.4,5018.7
BR D #Sta/Elev= 57
  1914.9   34.05    1915   31.75  2359.2   33.05  2489.2   32.85  2989.2   31.65
  3929.2   31.15  4259.2   30.45    4500   30.76  4569.2   30.85  4680.3   31.05
  4826.7   29.63  4836.4   29.54  4836.5   29.54  4868.7   30.18  4878.2    30.3
  4905.7   30.65  4905.8   30.65  4934.2   30.87  4943.9   30.78  4967.4   30.57
  4968.1   30.56 4968.29   30.55  4968.4   30.54 4968.51   30.54 4980.81   29.88
  4980.9   29.87  4981.1   29.86  4982.4   29.79  4982.6   23.06  4982.7    19.7
  4993.3   17.88  4995.8   17.97  4997.7   17.25  5001.5   17.22  5004.3   18.08
  5006.9   18.13  5017.6    21.7  5017.8   21.77 5017.99   23.83  5018.1   25.03
  5018.3    27.2  5018.7   31.54 5019.49   31.62  5019.6   31.63 5019.71   31.64
  5026.4   32.31  5027.5   32.42  5062.1   33.27  5062.5   33.28  5089.5   32.84
  5092.3   32.76    5113   32.18  5124.1   31.86  5150.8   31.11  5151.4   31.09
  5209.3   32.55  5209.4   34.05
BR D #Mann= 5
  1914.9     .99    4500      .1  4982.4    .015  5018.7      .1  5209.3      .2
BR D Banks=4982.4,5018.7
BC Design=,, 0 ,, 0 ,,,,,,
BC HTab HWMax=34.11
BC Use User HTab Curves=0
BC User HTab FreeFlow(D)= 0

Type RM Length L Ch R = 1 ,24097.4 ,155.2,157.3,158.5
BEGIN DESCRIPTION:
Downstream Section of Bridge/Culvert/Weir
END DESCRIPTION:
XS GIS Cut Line= 5
      3164755.82     13802013.44      3165205.96     13802281.11
      3166930.06     13803812.43       3167106.6     13803928.61
      3167284.74     13804108.96
#Sta/Elev= 30
  1914.9   34.07    1915   31.77  2359.2   33.07  2489.2   32.87  2989.2   31.67
  3929.2   31.17  4259.2   30.47    4500   30.78  4680.3   31.07  4836.5   29.56
  4868.7    30.2  4905.7   30.67  4934.2   30.89  4968.1   30.58  4982.4   29.81
  4982.7   19.72  4993.3    17.9  4995.8   17.99  4997.7   17.27  5001.5   17.24
  5004.3    18.1  5006.9   18.15  5017.8   21.79  5018.7   31.56  5027.5   32.44
  5062.5    33.3  5089.5   32.86  5151.4   31.11  5209.3   32.57  5209.4   34.07
#Mann= 5 ,-1 , 0
  1914.9     .99       0    4500      .1       0  4982.4    .015       0
  5018.7      .1       0  5209.3      .2       0
#XS Ineff= 2 , 0
       0  4982.4    29.6  5018.4       0    29.3
Permanent Ineff=
       F       F
Bank Sta=4982.4,5018.7
XS Rating Curve= 0 ,0
Exp/Cntr=0.5,0.3

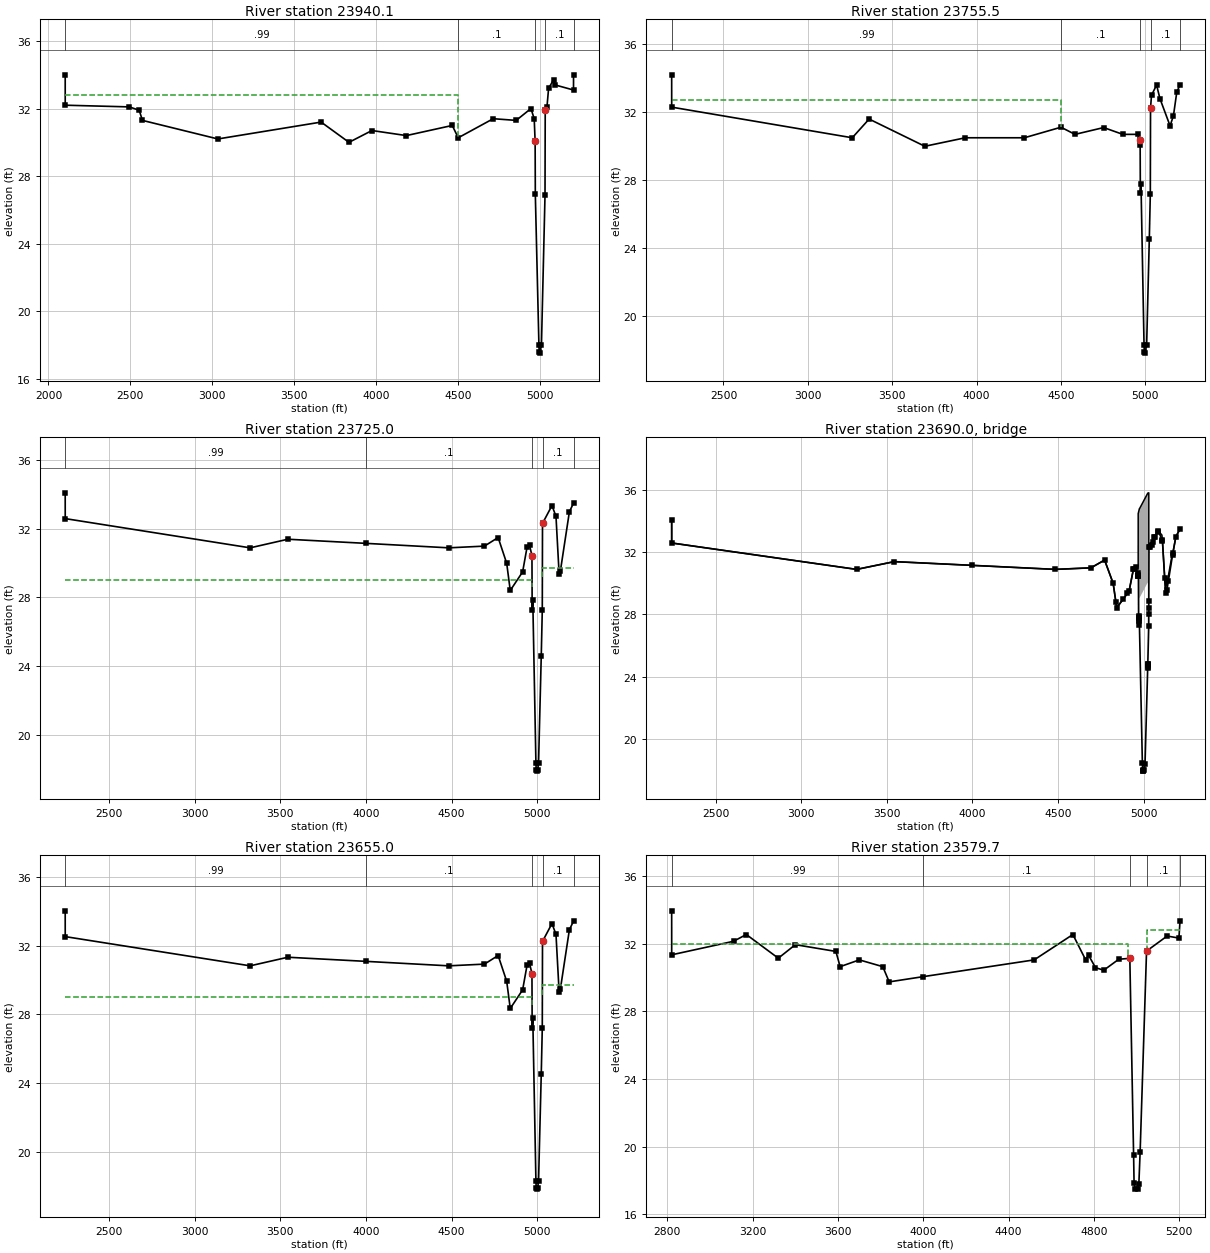
Type RM Length L Ch R = 1 ,23940.1 ,182.8,184.6,183
BEGIN DESCRIPTION:
Cross Section 23940.1-Interpolated
END DESCRIPTION:
XS GIS Cut Line= 4
      3164849.42     13802180.81      3165160.85     13802417.62
       3167013.9     13804062.48      3167183.09     13804221.28
#Sta/Elev= 30
  2102.3      34  2102.4    32.2  2493.6    32.1  2553.6    31.9  2573.6    31.3
  3033.6    30.2  3663.6    31.2  3833.6      30  3973.6    30.7  4183.6    30.4
  4463.6      31    4500   30.27  4713.6    31.4  4853.6    31.3  4943.6      32
  4963.6    31.4  4969.2   30.05  4970.4   26.91  4992.3   18.01  4994.1   17.56
    4998   17.51  5007.7   17.98  5029.5   26.86  5030.8   31.92  5041.4    32.1
  5051.4    33.2  5081.4    33.7  5091.4    33.4  5203.4    33.1  5203.5      34
#Mann= 5 ,-1 , 0
  2102.3     .99       0    4500      .1       0  4969.2    .015       0
  5030.8      .1       0  5203.4      .2       0
#XS Ineff= 2 , 0
       0    4500    32.8               0
Permanent Ineff=
       F       F
Bank Sta=4969.2,5030.8
XS Rating Curve= 0 ,0
Exp/Cntr=0.3,0.1

Type RM Length L Ch R = 1 ,23755.5 ,62.3,30.5,28.1
BEGIN DESCRIPTION:
Cross Section 23755.5-Interpolated
END DESCRIPTION:
XS GIS Cut Line= 3
      3164852.32     13802312.75      3166809.64     13804133.73
      3167068.81     13804351.88
#Sta/Elev= 30
  2193.1    34.2  2193.2    32.3  3263.2    30.5  3363.2    31.6  3693.2      30
  3933.2    30.5  4283.2    30.5    4500   31.12  4583.2    30.7  4753.2    31.1
  4866.6    30.7  4956.6    30.7  4966.6    30.1  4969.2   30.38  4970.4   27.24
  4974.2   27.81  4992.3   18.34  4994.1   17.89    4998   17.84  5007.7   18.31
  5023.5   24.54  5029.5   27.19  5030.8   32.25  5036.6      33  5066.6    33.6
  5086.6    32.8  5146.6    31.2  5166.6    31.8  5186.6    33.2  5205.4    33.6
#Mann= 5 ,-1 , 0
  2193.1     .99       0    4500      .1       0  4969.2    .015       0
  5030.8      .1       0  5205.4      .2       0
#XS Ineff= 2 , 0
       0    4500    32.7               0
Permanent Ineff=
       F       F
Bank Sta=4969.2,5030.8
XS Rating Curve= 0 ,0
Exp/Cntr=0.5,0.3

Type RM Length L Ch R = 1 ,23725.0 ,70,70,70
BEGIN DESCRIPTION:
Upstream Section of Bridge/Culvert/Weir
END DESCRIPTION:
XS GIS Cut Line= 4
      3164695.23     13802574.23      3166630.12     13804076.06
      3166856.01     13804219.35      3167031.66     13804399.56
#Sta/Elev= 30
  2243.5   34.08  2243.6   32.58  3323.6   30.88  3543.6   31.38    4000   31.14
  4483.6   30.88  4691.7   30.98  4771.7   31.48  4821.7   29.98  4842.5    28.4
  4914.7   29.48  4940.4   30.91  4954.9   31.03  4969.2   30.43  4970.4   27.29
    4974   27.86  4992.3   18.39  4994.1   17.94    4998   17.89  5002.5   17.96
  5007.7   18.36  5023.5   24.59  5029.5   27.24  5030.8    32.3  5086.1   33.34
  5109.5   32.71  5127.8   29.37  5135.5   29.55  5187.8   32.98    5212   33.48
#Mann= 5 ,-1 , 0
  2243.5     .99       0    4000      .1       0  4969.2    .015       0
  5030.8      .1       0    5212      .2       0
#XS Ineff= 2 , 0
       0  4969.9      29    5030       0    29.7
Permanent Ineff=
       F       F
Bank Sta=4969.2,5030.8
XS Rating Curve= 0 ,0
Exp/Cntr=0.5,0.3

Type RM Length L Ch R = 3 ,23690.0 ,,,
BEGIN DESCRIPTION:
DRIVEWAY
Structure ID: C06-16
END DESCRIPTION:
Node Name=DRIVEWAY
Bridge Culvert--1,0,-1,-1, 0
Deck Dist Width WeirC Skew NumUp NumDn MinLoCord MaxHiCord MaxSubmerge Is_Ogee
10,50,2.6,0, 39, 39, , , 0.95, 0, 1,1,,
  2243.5  2243.6  3323.6  3543.6  4483.6  4691.7  4771.7  4821.7  4842.5  4914.7
  4940.4  4954.9  4964.4 4967.79  4967.9  4969.2  4970.4    4974 4974.11  4974.2
 5023.79  5023.9  5029.5  5029.8 5029.91  5030.8  5046.8    5063  5086.1  5106.5
  5109.5  5122.6  5127.8  5135.5  5144.4  5168.4    5170  5187.8    5212
    34.1    32.6    30.9    31.4    30.9      31    31.5      30   28.43   29.51
   30.94   31.06   30.95    31.1    34.5   34.55   34.61   34.77   34.77   34.78
   35.81   35.81   35.83   35.83   32.43   32.43   32.68   33.03   33.37   33.11
   32.74   30.35   29.68   30.06    30.5      32   31.93      33    33.5
    34.1    32.6    30.9    31.4    30.9      31    31.5      30   28.42    29.5
   30.93   31.05   30.65   30.51    30.5   30.45   27.31   27.88   27.82   29.03
   30.06   24.79   27.26   28.43   28.86   32.32    32.5   33.01   33.36   32.81
   32.73   30.34   29.39   29.57   30.18   31.82   31.93      33    33.5
  2243.5  2243.6  3323.6  3543.6  4483.6  4691.7  4771.7  4821.7  4842.5  4914.7
  4940.4  4954.9  4964.4 4967.79  4967.9  4969.2  4970.4    4974 4974.11  4974.2
 5023.79  5023.9  5029.5  5029.8 5029.91  5030.8  5046.8    5063  5086.1  5106.5
  5109.5  5122.6  5127.8  5135.5  5144.4  5168.4    5170  5187.8    5212
    34.1    32.6    30.9    31.4    30.9      31    31.5      30   28.43   29.51
   30.94   31.06   30.95    31.1    34.5   34.55   34.61   34.77   34.77   34.78
   35.81   35.81   35.83   35.83   32.43   32.43   32.68   33.03   33.37   33.11
   32.74   30.35   29.68   30.06    30.5      32   31.93      33    33.5
   34.06   32.56   30.86   31.36   30.86   30.96   31.46   29.96   28.38   29.46
   30.89   31.01   30.61   30.47   30.46   30.41   27.27   27.84   27.78   28.99
   30.02   24.75   27.22   28.39   28.82   32.28   32.46   32.97   33.32   32.77
   32.69    30.3   29.35   29.53   30.14   31.78   31.89   32.96   33.46
BR Coef= 1 , 1 , 0 ,1.25, 0 ,,,0.8,0,2,0,
WSPro=,,,, 1 ,,,, 0 ,,,, 0 ,,,,-1 ,-1 ,-1 , 0 , 0 , 0 , 0 , 0
BR U #Sta/Elev= 61
  2243.5    34.1  2243.6    32.6  3323.6    30.9  3543.6    31.4    4000   31.16
  4483.6    30.9  4691.7      31  4771.7    31.5  4821.7      30  4837.2   28.82
  4842.5   28.42  4879.3   28.97  4904.6   29.35  4914.7    29.5  4940.4   30.93
  4941.4   30.94  4954.9   31.05  4964.4   30.65 4967.79   30.51  4967.9    30.5
 4968.01    30.5  4969.2   30.45  4970.4   27.31    4974   27.88 4974.11   27.82
  4974.2   27.78  4974.5   27.62  4974.6   27.57  4992.3   18.41  4994.1   17.96
  4996.7   17.93    4998   17.91  5002.5   17.98  5007.7   18.38  5023.4   24.57
  5023.5   24.61 5023.79   24.74  5023.9   24.79    5024   24.83  5029.5   27.26
 5029.69      28  5029.8   28.43 5029.91   28.86  5030.8   32.32  5034.1   32.36
  5046.8    32.5  5051.5   32.65    5063   33.01  5063.2   33.01  5084.1   33.33
  5086.1   33.36  5106.5   32.81  5109.5   32.73  5122.6   30.34  5127.8   29.39
  5135.5   29.57  5144.4   30.18  5168.4   31.82    5170   31.93  5187.8      33
    5212    33.5
BR U #Mann= 5
  2243.5     .99    4000      .1  4969.2    .015  5030.8      .1    5212      .2
BR U Banks=4969.2,5030.8
BR D #Sta/Elev= 61
  2243.5   34.06  2243.6   32.56  3323.6   30.86  3543.6   31.36    4000   31.12
  4483.6   30.86  4691.7   30.96  4771.7   31.46  4821.7   29.96  4837.2   28.78
  4842.5   28.38  4879.3   28.93  4904.6   29.31  4914.7   29.46  4940.4   30.89
  4941.4    30.9  4954.9   31.01  4964.4   30.61 4967.79   30.47  4967.9   30.46
 4968.01   30.46  4969.2   30.41  4970.4   27.27    4974   27.84 4974.11   27.78
  4974.2   27.74  4974.5   27.58  4974.6   27.53  4992.3   18.37  4994.1   17.92
  4996.7   17.89    4998   17.87  5002.5   17.94  5007.7   18.34  5023.4   24.53
  5023.5   24.57 5023.79    24.7  5023.9   24.75    5024   24.79  5029.5   27.22
 5029.69   27.96  5029.8   28.39 5029.91   28.82  5030.8   32.28  5034.1   32.32
  5046.8   32.46  5051.5   32.61    5063   32.97  5063.2   32.97  5084.1   33.29
  5086.1   33.32  5106.5   32.77  5109.5   32.69  5122.6    30.3  5127.8   29.35
  5135.5   29.53  5144.4   30.14  5168.4   31.78    5170   31.89  5187.8   32.96
    5212   33.46
BR D #Mann= 5
  2243.5     .99    4000      .1  4969.2    .015  5030.8      .1    5212      .2
BR D Banks=4969.2,5030.8
BC Design=,, 0 ,, 0 ,,,,,,
BC HTab HWMax=34.08
BC Use User HTab Curves=0
BC User HTab FreeFlow(D)= 0

Type RM Length L Ch R = 1 ,23655.0 ,181.7,75.3,65.8
BEGIN DESCRIPTION:
Downstream Section of Bridge/Culvert/Weir
END DESCRIPTION:
XS GIS Cut Line= 4
      3164650.69     13802628.23      3166585.58     13804130.06
      3166811.47     13804273.35      3166987.12     13804453.56
#Sta/Elev= 30
  2243.5   34.02  2243.6   32.52  3323.6   30.82  3543.6   31.32    4000   31.08
  4483.6   30.82  4691.7   30.92  4771.7   31.42  4821.7   29.92  4842.5   28.34
  4914.7   29.42  4940.4   30.85  4954.9   30.97  4969.2   30.37  4970.4   27.23
    4974    27.8  4992.3   18.33  4994.1   17.88    4998   17.83  5002.5    17.9
  5007.7    18.3  5023.5   24.53  5029.5   27.18  5030.8   32.24  5086.1   33.28
  5109.5   32.65  5127.8   29.31  5135.5   29.49  5187.8   32.92    5212   33.42
#Mann= 5 ,-1 , 0
  2243.5     .99       0    4000      .1       0  4969.2    .015       0
  5030.8      .1       0    5212      .2       0
#XS Ineff= 2 , 0
       0  4969.9      29    5030       0    29.7
Permanent Ineff=
       F       F
Bank Sta=4969.2,5030.8
XS Rating Curve= 0 ,0
Exp/Cntr=0.5,0.3

Type RM Length L Ch R = 1 ,23579.7 ,91,91,91
BEGIN DESCRIPTION:
Upstream Section of Bridge/Culvert/Weir
END DESCRIPTION:
XS GIS Cut Line= 5
      3164813.26     13803524.69      3166599.08     13804295.98
      3166778.39     13804377.09      3166867.82     13804343.56
      3166991.63     13804421.74
#Sta/Elev= 30
  2820.1   33.94  2820.2   31.34  3110.2   32.14  3170.2   32.54  3320.2   31.14
  3400.2   31.94  3590.2   31.54  3610.2   30.64  3700.2   31.04  3810.2   30.64
  3840.2   29.74    4000   30.05  4520.2   31.04  4701.7   32.54  4761.7   31.04
  4775.1   31.32  4807.8   30.58  4846.7   30.43  4917.2   31.08  4968.8   31.13
  4986.5   19.51  4988.7   17.85  4993.7    17.5  5006.9   17.49  5011.1   17.78
  5017.1   19.69  5047.2   31.56  5143.7   32.45  5199.1   32.33  5204.1   33.34
#Mann= 5 ,-1 , 0
  2820.1     .99       0    4000      .1       0  4968.8    .015       0
  5047.2      .1       0  5204.1      .2       0
#XS Ineff= 2 , 0
       0    4958      32    5050       0    32.8
Permanent Ineff=
       F       F
Bank Sta=4968.8,5047.2
XS Rating Curve= 0 ,0
Exp/Cntr=0.5,0.3