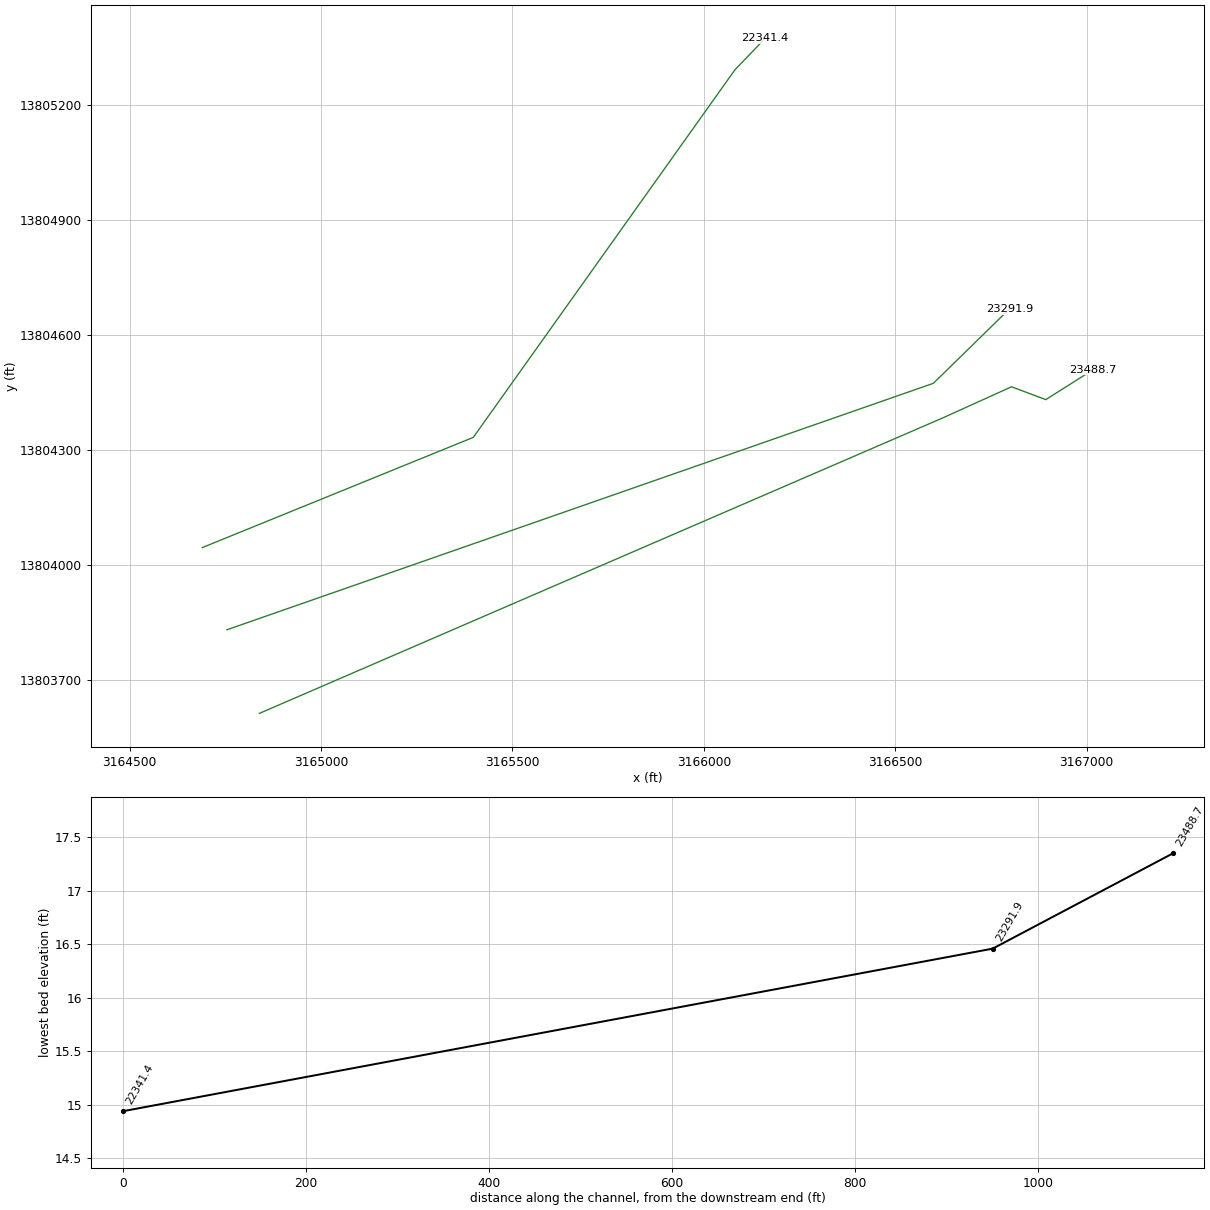
HEC-RAS study C106-00-00.PRJ: C106-00-00 2015

--- C106-00-00.g01 (geometry) --- (continued)

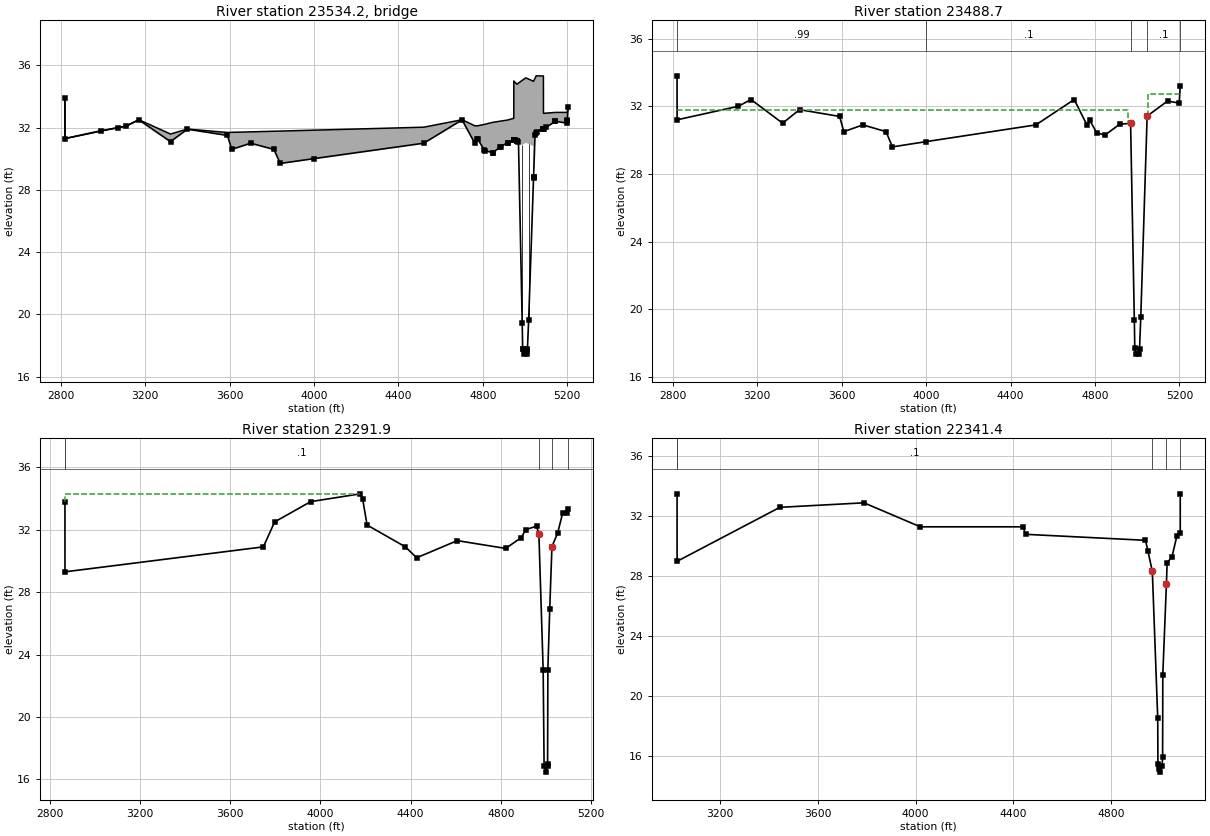
Type RM Length L Ch R = 3 ,23534.2 ,,,
BEGIN DESCRIPTION:
STATE HIGHWAY 3 (GALVESTON ROAD)
Structure ID: C06-15
END DESCRIPTION:
Node Name=STATE HIGHWAY 3
Bridge Culvert--1,0,-1,-1, 0
Deck Dist Width WeirC Skew NumUp NumDn MinLoCord MaxHiCord MaxSubmerge Is_Ogee
10,71,2.6,0, 33, 33, , , 0.95, 0, 1,1,,
  2820.1  2820.2  3110.2  3170.2  3320.2  3400.2  3590.2  3610.2  3700.2  3810.2
  3840.2  4520.2  4701.7  4761.7  4775.1  4807.8  4846.7  4917.2 4946.59  4946.7
  4961.1  4986.5  5003.5 5040.29  5040.4  5047.2  5052.9  5057.3  5087.1 5087.21
  5143.7  5199.1  5204.1
    33.9    31.3   32.11   32.51   31.59   31.91   31.69    31.7   31.73   31.77
   31.78   32.03   32.51   32.12   32.12   32.21   32.34   32.49    32.6      35
   34.79   35.04    35.2   34.98   34.99   35.17   35.33   35.33   35.32   32.92
   32.98   32.98    33.3
    33.9    31.3    32.1    32.5    31.1    31.9    31.5    30.6      31    30.6
    29.7      31    32.5      31   31.28   30.54   30.39   31.04    31.2    31.2
   31.14   30.87   31.03   30.81   28.84   31.52   31.65   31.75   31.94   31.94
   32.41   32.29    33.3
  2820.1  2820.2  3110.2  3170.2  3320.2  3400.2  3590.2  3610.2  3700.2  3810.2
  3840.2  4520.2  4701.7  4761.7  4775.1  4807.8  4846.7  4917.2 4946.59  4946.7
  4961.1  4986.5  5003.5 5040.29  5040.4  5047.2  5052.9  5057.3  5087.1 5087.21
  5143.7  5199.1  5204.1
    33.9    31.3   32.11   32.51   31.59   31.91   31.69    31.7   31.73   31.77
   31.78   32.03   32.51   32.12   32.12   32.21   32.34   32.49    32.6      35
   34.79   35.04    35.2   34.98   34.99   35.17   35.33   35.33   35.32   32.92
   32.98   32.98    33.3
   33.85   31.25   32.05   32.45   31.05   31.85   31.45   30.55   30.95   30.55
   29.65   30.95   32.45   30.95   31.23   30.49   30.34   30.99   31.15   31.15
   31.09   30.82   30.98   30.76   28.79   31.47    31.6    31.7   31.89   31.89
   32.36   32.24   33.25
Pier Skew, UpSta & Num, DnSta & Num=  ,4986.5, 2 ,4986.5, 2 , 0 , 0 , 0 ,,
     1.3     1.3
   17.98   31.88
     1.3     1.3
   17.93   31.83
Pier Skew, UpSta & Num, DnSta & Num=  ,5017.1, 2 ,5017.1, 2 , 0 , 0 , 0 ,,
     1.3     1.3
   18.44   31.95
     1.3     1.3
   18.39    31.9
Abutment Skew #Up #Dn= , 2 , 2
  4960.9  4988.8
   31.14    17.8
  4960.9  4988.8
   31.09   17.75
Abutment Skew #Up #Dn= , 2 , 2
  5011.2 5040.49
   17.77   30.81
  5011.2 5040.49
   17.72   30.76
BR Coef= 1 , 1 , 0 ,1.25, 0 ,,,0.8,-1,2,0,
WSPro=,,,, 1 ,,,, 0 ,,,, 0 ,,,,-1 ,-1 ,-1 , 0 , 0 , 0 , 0 , 0
BR U #Sta/Elev= 63
  2820.1    33.9  2820.2    31.3  2990.2    31.8    3072      32  3110.2    32.1
  3170.2    32.5  3320.2    31.1  3400.2    31.9  3590.2    31.5  3610.2    30.6
  3700.2      31  3810.2    30.6  3840.2    29.7    4000   30.01  4520.2      31
  4701.7    32.5  4761.7      31  4774.7   31.27  4775.1   31.28  4807.8   30.54
  4810.3   30.53  4846.4   30.39  4846.7   30.39  4881.8   30.75  4884.6   30.77
  4917.2   31.04  4917.4   31.04 4946.59    31.2  4946.7    31.2 4946.81    31.2
  4947.4    31.2  4950.5   31.22  4960.9   31.15 4961.01   31.15  4961.1   31.14
  4968.8   31.09  4986.5   19.47  4988.7   17.81  4988.8    17.8  4993.7   17.46
  4999.6   17.61  5003.5   17.52  5006.9   17.45  5011.1   17.74  5011.2   17.77
  5017.1   19.65  5040.2   28.76 5040.29    28.8  5040.4   28.84  5047.2   31.52
  5052.9   31.65  5057.3   31.75 5086.99   31.94  5087.1   31.94 5087.21   31.94
  5087.6   31.94  5101.5   32.03  5143.7   32.41  5143.9   32.41  5199.1   32.29
  5199.7   32.41    5200   32.47  5204.1    33.3
BR U #Mann= 5
  2820.1     .99    4000      .1  4968.8    .015  5047.2      .1  5204.1      .2
BR U Banks=4968.8,5047.2
BR D #Sta/Elev= 63
  2820.1   33.85  2820.2   31.25  2990.2   31.75    3072   31.95  3110.2   32.05
  3170.2   32.45  3320.2   31.05  3400.2   31.85  3590.2   31.45  3610.2   30.55
  3700.2   30.95  3810.2   30.55  3840.2   29.65    4000   29.96  4520.2   30.95
  4701.7   32.45  4761.7   30.95  4774.7   31.22  4775.1   31.23  4807.8   30.49
  4810.3   30.48  4846.4   30.34  4846.7   30.34  4881.8    30.7  4884.6   30.72
  4917.2   30.99  4917.4   30.99 4946.59   31.15  4946.7   31.15 4946.81   31.15
  4947.4   31.15  4950.5   31.17  4960.9    31.1 4961.01    31.1  4961.1   31.09
  4968.8   31.04  4986.5   19.42  4988.7   17.76  4988.8   17.75  4993.7   17.41
  4999.6   17.56  5003.5   17.47  5006.9    17.4  5011.1   17.69  5011.2   17.72
  5017.1    19.6  5040.2   28.71 5040.29   28.75  5040.4   28.79  5047.2   31.47
  5052.9    31.6  5057.3    31.7 5086.99   31.89  5087.1   31.89 5087.21   31.89
  5087.6   31.89  5101.5   31.98  5143.7   32.36  5143.9   32.36  5199.1   32.24
  5199.7   32.36    5200   32.42  5204.1   33.25
BR D #Mann= 5
  2820.1     .99    4000      .1  4968.8    .015  5047.2      .1  5204.1      .2
BR D Banks=4968.8,5047.2
BC Design=,, 0 ,, 0 ,,,,,,
BC HTab HWMax=33.94
BC Use User HTab Curves=0
BC User HTab FreeFlow(D)= 0

Type RM Length L Ch R = 1 ,23488.7 ,156.6,196.8,224.8
BEGIN DESCRIPTION:
Downstream Section of Bridge/Culvert/Weir
END DESCRIPTION:
XS GIS Cut Line= 5
        3164839.     13803611.98      3166624.82     13804383.26
      3166804.13     13804464.37      3166893.56     13804430.84
      3167017.37     13804509.02
#Sta/Elev= 30
  2820.1    33.8  2820.2    31.2  3110.2      32  3170.2    32.4  3320.2      31
  3400.2    31.8  3590.2    31.4  3610.2    30.5  3700.2    30.9  3810.2    30.5
  3840.2    29.6    4000   29.91  4520.2    30.9  4701.7    32.4  4761.7    30.9
  4775.1   31.18  4807.8   30.44  4846.7   30.29  4917.2   30.94  4968.8   30.99
  4986.5   19.37  4988.7   17.71  4993.7   17.36  5006.9   17.35  5011.1   17.64
  5017.1   19.55  5047.2   31.42  5143.7   32.31  5199.1   32.19  5204.1    33.2
#Mann= 5 ,-1 , 0
  2820.1     .99       0    4000      .1       0  4968.8    .015       0
  5047.2      .1       0  5204.1      .2       0
#XS Ineff= 2 , 0
       0    4958    31.8    5050       0    32.7
Permanent Ineff=
       F       F
Bank Sta=4968.8,5047.2
XS Rating Curve= 0 ,0
Exp/Cntr=0.5,0.3

Type RM Length L Ch R = 1 ,23291.9 ,608.7,950.5,952
BEGIN DESCRIPTION:
Cross Section 23291.9
END DESCRIPTION:
XS GIS Cut Line= 3
      3164754.31     13803830.24      3166600.04     13804473.46
      3166798.27      13804667.2
#Sta/Elev= 28
    2867    33.8  2867.1    29.3  3747.1    30.9  3797.1    32.5  3957.1    33.8
  4177.1    34.3  4187.1      34  4207.1    32.3  4377.1    30.9  4427.1    30.2
  4607.1    31.3  4821.7    30.8  4891.7    31.5  4910.2      32  4958.9   32.23
  4969.2   31.72  4988.2      23  4992.3   16.87    5000   16.46  5007.4   16.85
  5007.8   16.99    5009   23.03  5017.2    26.9  5027.1   30.92  5052.4   31.78
  5074.4   33.06  5091.7    33.1  5098.9    33.3
#Mann= 5 ,-1 , 0
    2867      .2       0  2867.1      .1       0  4969.2    .015       0
  5027.1      .1       0  5098.9      .2       0
#XS Ineff= 2 , 0
       0  4177.1    34.3               0
Permanent Ineff=
       F       F
Bank Sta=4969.2,5027.1
XS Rating Curve= 0 ,0
Exp/Cntr=0.3,0.1

Type RM Length L Ch R = 1 ,22341.4 ,173.7,125.6,105.8
BEGIN DESCRIPTION:
Cross Section 22341.4-Interpolated
END DESCRIPTION:
XS GIS Cut Line= 4
      3164690.23     13804044.83      3165397.79     13804332.28
      3166081.65     13805291.89      3166160.53     13805373.72
#Sta/Elev= 23
  3025.8    33.5  3025.9      29  3445.9    32.6  3789.6    32.9  4019.6    31.3
  4439.6    31.3  4449.6    30.8  4939.6    30.4  4949.6    29.7  4967.6   28.32
  4989.7   18.52  4990.4   15.48  4995.5   15.13  5000.3   14.94  5007.6   15.37
  5009.6   15.95  5010.4   21.45  5025.2   27.51    5028    28.9    5048    29.3
    5068    30.7  5081.6    30.9  5081.7    33.5
#Mann= 5 ,-1 , 0
  3025.8      .2       0  3025.9      .1       0  4967.6    .015       0
  5025.2      .1       0  5081.6      .2       0
#XS Ineff= 2 , 0
       0  3789.6    32.9               0
Permanent Ineff=
       F       F
Bank Sta=4967.6,5025.2
XS Rating Curve= 0 ,0
Exp/Cntr=0.5,0.3