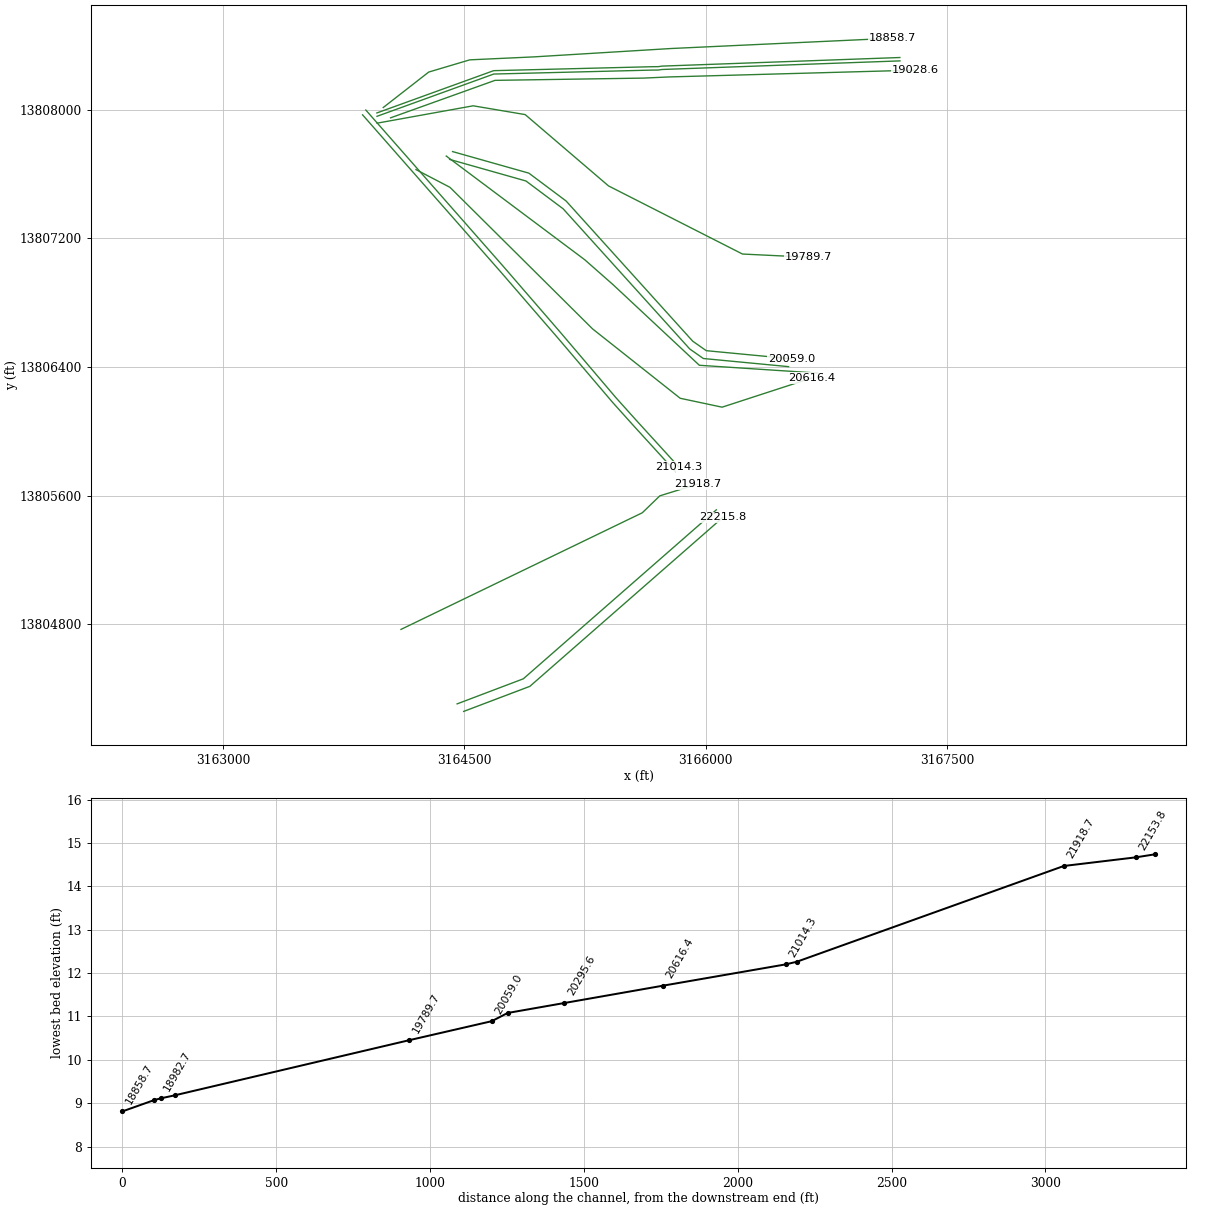
HEC-RAS study C106-00-00.PRJ: C106-00-00 2015

--- C106-00-00.g01 (geometry) --- (continued)

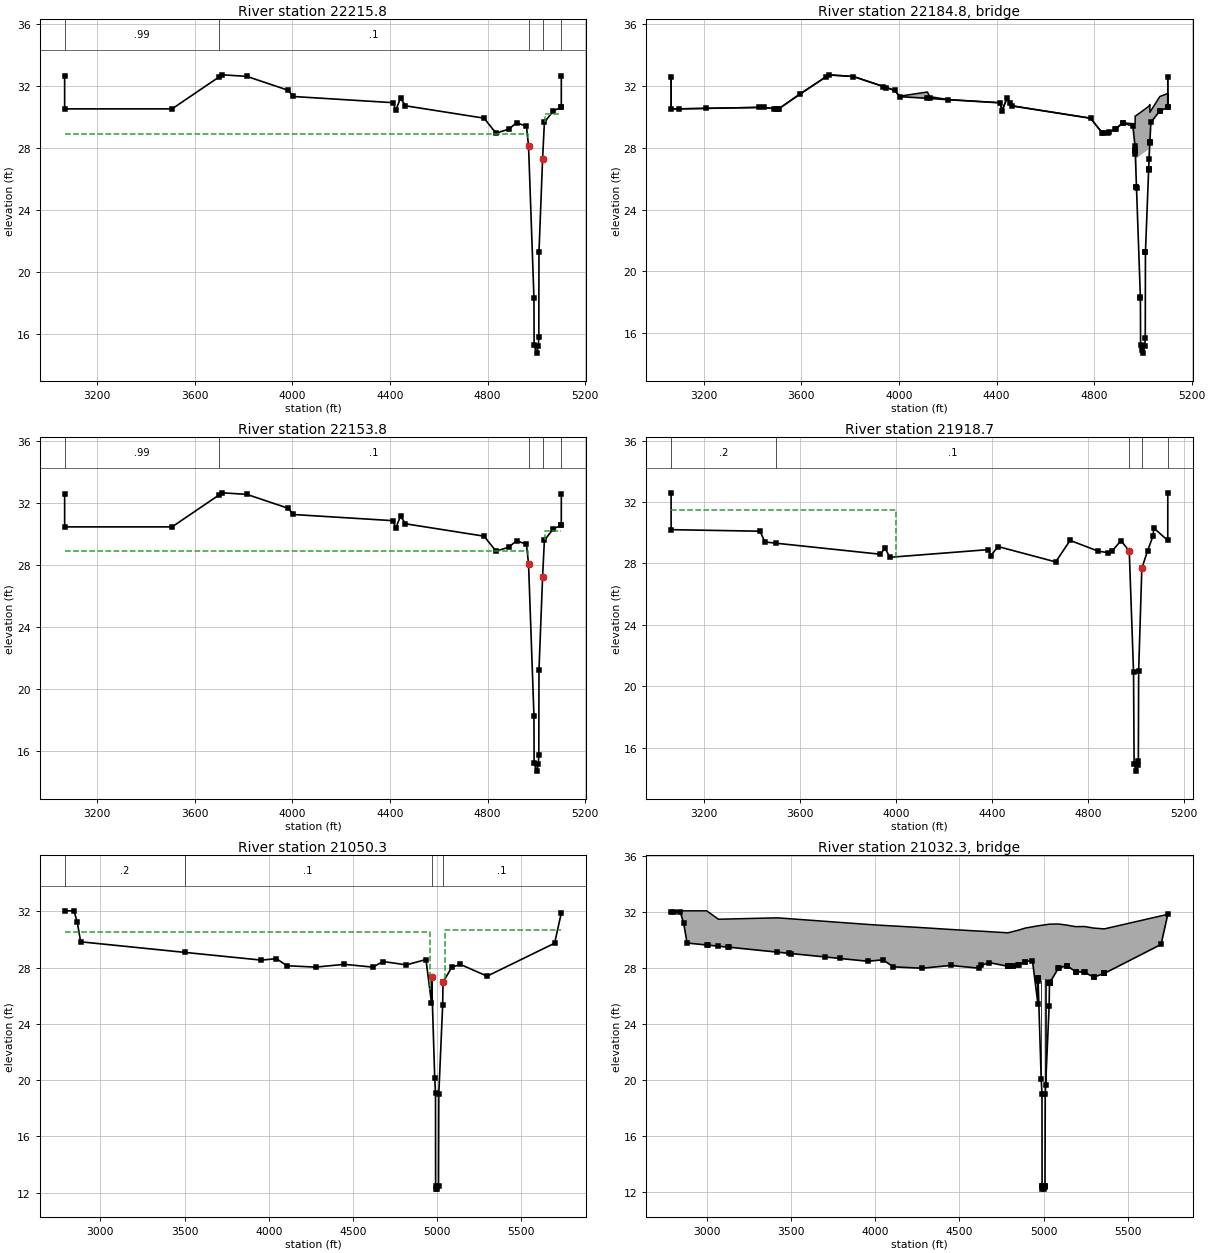
Type RM Length L Ch R = 1 ,22215.8 ,62,62,62
BEGIN DESCRIPTION:
Upstream Section of Bridge/Culvert/Weir
END DESCRIPTION:
XS GIS Cut Line= 4
        3164495.     13804258.61      3164906.71     13804414.59
      3166021.03     13805389.77      3166106.88     13805465.48
#Sta/Elev= 30
  3066.4   32.62  3066.5   30.52  3506.7   30.52    3700   32.59    3713   32.72
    3813   32.62    3983   31.72    4003   31.32    4413   30.92    4423   30.42
    4443   31.22    4463   30.72  4785.3   29.92  4834.3   28.95  4886.2   29.21
  4918.4   29.62    4959    29.4  4967.6   28.12  4989.7   18.32  4990.4   15.28
  5000.3   14.74  5007.6   15.17  5009.6   15.75  5010.3   21.25  5025.2   27.31
  5032.5   29.65  5069.4    30.4  5101.7   30.62  5101.8   30.62  5101.9   32.62
#Mann= 5 ,-1 , 0
  3066.4     .99       0    3700      .1       0  4967.6    .015       0
  5025.2      .1       0  5101.7      .2       0
#XS Ineff= 2 , 0
       0    4964    28.9  5033.6       0    30.2
Permanent Ineff=
       F       F
Bank Sta=4967.6,5025.2
XS Rating Curve= 0 ,0
Exp/Cntr=0.5,0.3

Type RM Length L Ch R = 3 ,22184.8 ,,,
BEGIN DESCRIPTION:
NEVADA AVENUE
Structure ID: C06-14
END DESCRIPTION:
Node Name=NEVADA AVENUE
Bridge Culvert--1,0,-1,-1, 0
Deck Dist Width WeirC Skew NumUp NumDn MinLoCord MaxHiCord MaxSubmerge Is_Ogee
10,42,2.6,0, 36, 36, , , 0.95, 0, 1,1,,
  3066.4  3066.5  3427.7  3506.7    3713    3813    3983    4003  4116.7  4126.7
    4203    4413    4423    4443    4463  4785.3  4834.3  4859.6  4886.2  4917.7
    4959  4967.6 4968.09  4968.2 4973.61  4973.7 5023.39  5023.5  5025.2  5028.5
 5028.61  5032.5  5069.4  5101.7  5101.8  5101.9
    32.6    30.5   30.61   30.51   32.71   32.61   31.71   31.33    31.6    31.3
   31.11   30.91   30.41   31.21   30.71   29.91   28.94      29    29.2   29.61
   29.55   29.55   29.55   30.05   30.09   30.09   30.67   30.67   30.71   30.79
   30.29   30.39   31.31    31.5    30.6    32.6
    32.6    30.5    30.6    30.5    32.7    32.6    31.7    31.3   31.19   31.18
    31.1    30.9    30.4    31.2    30.7    29.9   28.93   28.99   29.19    29.6
   29.38    28.1   27.88   27.83   25.43   27.32    27.9    26.6   27.29   28.35
   28.38   29.63   30.38    30.6    30.6    32.6
  3066.4  3066.5  3427.7  3506.7    3713    3813    3983    4003  4116.7  4126.7
    4203    4413    4423    4443    4463  4785.3  4834.3  4859.6  4886.2  4917.7
    4959  4967.6 4968.09  4968.2 4973.61  4973.7 5023.39  5023.5  5025.2  5028.5
 5028.61  5032.5  5069.4  5101.7  5101.8  5101.9
    32.6    30.5   30.61   30.51   32.71   32.61   31.71   31.33    31.6    31.3
   31.11   30.91   30.41   31.21   30.71   29.91   28.94      29    29.2   29.61
   29.55   29.55   29.55   30.05   30.09   30.09   30.67   30.67   30.71   30.79
   30.29   30.39   31.31    31.5    30.6    32.6
   32.56   30.46   30.56   30.46   32.66   32.56   31.66   31.26   31.15   31.14
   31.06   30.86   30.36   31.16   30.66   29.86   28.89   28.95   29.15   29.56
   29.34   28.06   27.84   27.79   25.39   27.28   27.86   26.56   27.25   28.31
   28.34   29.59   30.34   30.56   30.56   32.56
Abutment Skew #Up #Dn= , 2 , 2
  4973.5  4989.7
   27.32    18.3
  4973.5  4989.7
   27.28   18.26
Abutment Skew #Up #Dn= , 2 , 2
  5010.4 5023.59
   21.27    27.9
  5010.4 5023.59
   21.23   27.86
BR Coef= 1 , 1 , 0 ,1.25, 0 ,,,0.8,0,2,0,
WSPro=,,,, 1 ,,,, 0 ,,,, 0 ,,,,-1 ,-1 ,-1 , 0 , 0 , 0 , 0 , 0
BR U #Sta/Elev= 66
  3066.4    32.6  3066.5    30.5  3097.7   30.51  3207.7   30.54  3427.7    30.6
  3446.5    30.6  3487.7   30.53  3497.7   30.51  3506.5    30.5  3506.7    30.5
  3596.5    31.5    3700   32.57    3713    32.7    3813    32.6  3936.7   31.95
  3946.7   31.89    3983    31.7    4003    31.3  4116.7   31.19  4126.7   31.18
    4203    31.1    4413    30.9    4423    30.4    4443    31.2  4456.7   30.86
    4463    30.7  4785.3    29.9  4834.3   28.93  4834.4   28.93  4856.9   28.98
  4859.6   28.99  4886.2   29.19  4888.6   29.21  4917.7    29.6  4918.4    29.6
    4959   29.38  4967.6    28.1 4968.09   27.88  4968.2   27.83 4968.31   27.79
  4968.7   27.61  4973.5   25.48 4973.61   25.43  4973.7    25.4  4989.6   18.34
  4989.7    18.3  4990.4   15.26  4995.5   14.91  5000.3   14.72  5007.6   15.15
  5009.6   15.73  5010.3   21.23  5010.4   21.27 5023.39   26.55  5023.5    26.6
  5023.6   26.64  5025.2   27.29 5028.39   28.31  5028.5   28.35 5028.61   28.38
  5032.5   29.63  5069.4   30.38  5069.6   30.38  5101.7    30.6  5101.8    30.6
  5101.9    32.6
BR U #Mann= 5
  3066.4     .99    3700      .1  4967.6    .015  5025.2      .1  5101.7      .2
BR U Banks=4967.6,5025.2
BR D #Sta/Elev= 66
  3066.4   32.56  3066.5   30.46  3097.7   30.47  3207.7    30.5  3427.7   30.56
  3446.5   30.56  3487.7   30.49  3497.7   30.47  3506.5   30.46  3506.7   30.46
  3596.5   31.46    3700   32.53    3713   32.66    3813   32.56  3936.7   31.91
  3946.7   31.85    3983   31.66    4003   31.26  4116.7   31.15  4126.7   31.14
    4203   31.06    4413   30.86    4423   30.36    4443   31.16  4456.7   30.82
    4463   30.66  4785.3   29.86  4834.3   28.89  4834.4   28.89  4856.9   28.94
  4859.6   28.95  4886.2   29.15  4888.6   29.17  4917.7   29.56  4918.4   29.56
    4959   29.34  4967.6   28.06 4968.09   27.84  4968.2   27.79 4968.31   27.75
  4968.7   27.57  4973.5   25.44 4973.61   25.39  4973.7   25.36  4989.6    18.3
  4989.7   18.26  4990.4   15.22  4995.5   14.87  5000.3   14.68  5007.6   15.11
  5009.6   15.69  5010.3   21.19  5010.4   21.23 5023.39   26.51  5023.5   26.56
  5023.6    26.6  5025.2   27.25 5028.39   28.27  5028.5   28.31 5028.61   28.34
  5032.5   29.59  5069.4   30.34  5069.6   30.34  5101.7   30.56  5101.8   30.56
  5101.9   32.56
BR D #Mann= 5
  3066.4     .99    3700      .1  4967.6    .015  5025.2      .1  5101.7      .2
BR D Banks=4967.6,5025.2
BC Design=,, 0 ,, 0 ,,,,,,
BC HTab HWMax=32.72
BC Use User HTab Curves=0
BC User HTab FreeFlow(D)= 0

Type RM Length L Ch R = 1 ,22153.8 ,338.5,235.1,222.4
BEGIN DESCRIPTION:
Downstream Section of Bridge/Culvert/Weir
END DESCRIPTION:
XS GIS Cut Line= 4
      3164454.46     13804305.52      3164866.17     13804461.51
      3165980.49     13805436.69      3166066.35     13805512.39
#Sta/Elev= 30
  3066.4   32.55  3066.5   30.45  3506.7   30.45    3700   32.52    3713   32.65
    3813   32.55    3983   31.65    4003   31.25    4413   30.85    4423   30.35
    4443   31.15    4463   30.65  4785.3   29.85  4834.3   28.88  4886.2   29.14
  4918.4   29.55    4959   29.33  4967.6   28.05  4989.7   18.25  4990.4   15.21
  5000.3   14.67  5007.6    15.1  5009.6   15.68  5010.3   21.18  5025.2   27.24
  5032.5   29.58  5069.4   30.33  5101.7   30.55  5101.8   30.55  5101.9   32.55
#Mann= 5 ,-1 , 0
  3066.4     .99       0    3700      .1       0  4967.6    .015       0
  5025.2      .1       0  5101.7      .2       0
#XS Ineff= 2 , 0
       0    4964    28.9  5033.6       0    30.2
Permanent Ineff=
       F       F
Bank Sta=4967.6,5025.2
XS Rating Curve= 0 ,0
Exp/Cntr=0.5,0.3

Type RM Length L Ch R = 1 ,21918.7 ,1461.3,868.4,81.2
BEGIN DESCRIPTION:
Cross Section 21918.7
END DESCRIPTION:
XS GIS Cut Line= 4
      3164105.37      13804768.7      3165606.01     13805494.01
      3165715.16      13805599.4      3165951.84     13805672.85
#Sta/Elev= 30
  3064.8    32.6  3064.9    30.2  3434.9    30.1  3454.9    29.4    3500   29.32
  3934.9    28.6  3954.9      29  3974.9    28.4  4384.9    28.9  4394.9    28.5
  4424.9    29.1  4664.9    28.1  4724.9    29.5  4841.6    28.8  4883.4    28.7
    4898   28.78  4936.5   29.48    4971   28.81  4988.8   20.93  4991.2   14.92
  5000.1   14.47  5008.5    14.9  5008.8   15.11  5010.1   21.01  5023.3   27.68
  5047.1   28.82  5069.5   29.77  5073.4    30.3  5131.2    29.5  5131.3    32.6
#Mann= 5 ,-1 , 0
  3064.8      .2       0    3500      .1       0    4971    .015       0
  5023.3      .1       0  5131.2      .2       0
#XS Ineff= 2 , 0
       0    4000    31.5               0
Permanent Ineff=
       F       F
Bank Sta=4971,5023.3
XS Rating Curve= 0 ,0
Exp/Cntr=0.5,0.3

Type RM Length L Ch R = 1 ,21050.3 ,36,36,36
BEGIN DESCRIPTION:
Upstream Section of Bridge/Culvert/Weir
END DESCRIPTION:
XS GIS Cut Line= 6
      3163866.41     13807968.69      3164724.55      13806992.9
      3165078.94     13806583.19      3165421.01      13806180.9
      3165548.68     13806038.78      3165811.26     13805750.91
#Sta/Elev= 30
    2788   32.03    2843   32.03    2863   31.23    2883   29.83    3500   29.08
  3955.7   28.53  4045.7   28.63  4108.7   28.13  4278.7   28.03  4448.7   28.23
  4618.7   28.03  4678.5   28.43  4817.5   28.19  4934.1   28.57  4966.5   25.51
  4967.2   27.36    4986   20.15  4990.7   19.06  4991.3   12.48  4992.2   12.27
  5000.3   12.26  5008.5   12.48  5010.2   19.03  5033.1   25.31  5035.3   26.97
  5088.1   28.03  5138.7   28.22  5297.2   27.39    5698   29.73  5737.9   31.88
#Mann= 4 ,-1 , 0
    2788      .2       0    3500      .1       0  4967.2    .015       0
  5035.3      .1       0
#XS Ineff= 2 , 0
       0    4957    30.5    5045       0    30.7
Permanent Ineff=
       F       F
Bank Sta=4967.2,5035.3
XS Rating Curve= 0 ,0
Exp/Cntr=0.5,0.3

Type RM Length L Ch R = 3 ,21032.3 ,,,
BEGIN DESCRIPTION:
UNION PACIFIC RAILROAD
Structure ID: C06-13
END DESCRIPTION:
Node Name=UNION PACIFIC RA
Bridge Culvert--1,0,-1,-1, 0
Deck Dist Width WeirC Skew NumUp NumDn MinLoCord MaxHiCord MaxSubmerge Is_Ogee
10,16,2.6,0, 35, 35, , , 0.95, 0, 1,1,,
    2788  2804.5    2843    2863    2883  2999.5  3069.5  3419.5  3955.7  4045.7
  4108.7  4278.7  4448.7  4618.7  4628.7  4678.5 4788.49  4854.2  4891.8  4934.1
  4966.5  4967.2  4967.4    4986 5035.69  5035.8  5035.9  5088.1  5138.2  5190.6
  5243.3  5297.2  5360.8    5698  5737.9
      32    32.1    32.1    32.1    32.1    32.1    31.5    31.6   31.13   31.06
   31.02    30.9   30.77   30.65   30.65   30.61   30.53   30.73   30.87   30.96
   31.03   31.03   31.03   31.06   31.15   31.15   31.15   31.16   31.08   30.97
   30.98   30.87   30.81   31.74   31.85
      32      32      32    31.2    29.8   29.66   29.57   29.15    28.5    28.6
    28.1      28    28.2      28    28.2    28.4   28.14   28.26   28.48   28.54
   25.48   27.33   27.25   27.15   27.24   26.95   26.95      28   28.19   27.75
   27.72   27.36   27.63    29.7   31.85
    2788  2804.5    2843    2863    2883  2999.5  3069.5  3419.5  3955.7  4045.7
  4108.7  4278.7  4448.7  4618.7  4628.7  4678.5 4788.49  4854.2  4891.8  4934.1
  4966.5  4967.2  4967.4    4986 5035.69  5035.8  5035.9  5088.1  5138.2  5190.6
  5243.3  5297.2  5360.8    5698  5737.9
      32    32.1    32.1    32.1    32.1    32.1    31.5    31.6   31.13   31.06
   31.02    30.9   30.77   30.65   30.65   30.61   30.53   30.73   30.87   30.96
   31.03   31.03   31.03   31.06   31.15   31.15   31.15   31.16   31.08   30.97
   30.98   30.87   30.81   31.74   31.85
   31.98   31.98   31.98   31.18   29.78   29.64   29.55   29.13   28.48   28.58
   28.08   27.98   28.18   27.98   28.18   28.38   28.12   28.24   28.46   28.52
   25.46   27.31   27.23   27.13   27.22   26.93   26.93   27.98   28.17   27.73
    27.7   27.34   27.61   29.68   31.83
Pier Skew, UpSta & Num, DnSta & Num=  ,4986, 2 ,4986, 2 , 0 , 0 , 0 ,,
       2       2
   18.89   28.16
       2       2
   18.87   28.14
Pier Skew, UpSta & Num, DnSta & Num=  ,5012.4, 2 ,5012.4, 2 , 0 , 0 , 0 ,,
       2       2
   18.37    28.2
       2       2
   18.35   28.18
Abutment Skew #Up #Dn= , 2 , 2
  4967.2  4991.4
   27.25   12.43
  4967.2  4991.4
   27.23   12.41
Abutment Skew #Up #Dn= , 2 , 2
  5008.5 5035.89
   12.45   27.24
  5008.5 5035.89
   12.43   27.22
BR Coef= 1 , 1 , 0 ,1.25, 0 ,,,0.8,0,2,0,
WSPro=,,,, 1 ,,,, 0 ,,,, 0 ,,,,-1 ,-1 ,-1 , 0 , 0 , 0 , 0 , 0
BR U #Sta/Elev= 74
    2788      32  2804.5      32    2843      32    2863    31.2    2883    29.8
  2999.5   29.66  3009.5   29.65  3069.5   29.57  3124.5   29.51  3134.5    29.5
  3419.5   29.15  3489.5   29.06    3500   29.05  3699.5   28.81  3788.8    28.7
  3955.7    28.5  4045.7    28.6  4108.7    28.1  4278.7      28  4448.7    28.2
  4618.7      28  4628.7    28.2  4678.5    28.4 4788.49   28.14  4788.6   28.14
  4788.7   28.14 4788.81   28.14  4788.9   28.14  4817.5   28.16  4820.3   28.17
  4850.1   28.25  4854.2   28.26  4889.3   28.47  4891.8   28.48  4934.1   28.54
  4966.5   25.48  4967.1   27.07  4967.2   27.33 4967.31   27.29  4967.4   27.25
    4986   20.12  4990.7   19.03  4991.3   12.45  4991.4   12.43  4992.2   12.24
  5000.3   12.23  5006.2    12.4  5008.4   12.45  5008.5   12.45  5010.2      19
  5012.4   19.68  5033.1   25.28  5035.3   26.94 5035.69   26.95  5035.8   26.95
  5035.9   26.95  5041.2   27.05  5088.1      28    5089      28  5138.2   28.19
  5138.7   28.19  5190.6   27.75  5191.8   27.75    5243   27.72  5243.3   27.72
  5297.2   27.36  5299.8   27.37  5359.9   27.63 5359.99   27.63  5360.1   27.63
 5360.21   27.63  5360.8   27.63    5698    29.7  5737.9   31.85
BR U #Mann= 4
    2788      .2    3500      .1  4967.2    .015  5035.3      .1
BR U Banks=4967.2,5035.3
BR D #Sta/Elev= 74
    2788   31.98  2804.5   31.98    2843   31.98    2863   31.18    2883   29.78
  2999.5   29.64  3009.5   29.63  3069.5   29.55  3124.5   29.49  3134.5   29.48
  3419.5   29.13  3489.5   29.04    3500   29.03  3699.5   28.79  3788.8   28.68
  3955.7   28.48  4045.7   28.58  4108.7   28.08  4278.7   27.98  4448.7   28.18
  4618.7   27.98  4628.7   28.18  4678.5   28.38 4788.49   28.12  4788.6   28.12
  4788.7   28.12 4788.81   28.12  4788.9   28.12  4817.5   28.14  4820.3   28.15
  4850.1   28.23  4854.2   28.24  4889.3   28.45  4891.8   28.46  4934.1   28.52
  4966.5   25.46  4967.1   27.05  4967.2   27.31 4967.31   27.27  4967.4   27.23
    4986    20.1  4990.7   19.01  4991.3   12.43  4991.4   12.41  4992.2   12.22
  5000.3   12.21  5006.2   12.38  5008.4   12.43  5008.5   12.43  5010.2   18.98
  5012.4   19.66  5033.1   25.26  5035.3   26.92 5035.69   26.93  5035.8   26.93
  5035.9   26.93  5041.2   27.03  5088.1   27.98    5089   27.98  5138.2   28.17
  5138.7   28.17  5190.6   27.73  5191.8   27.73    5243    27.7  5243.3    27.7
  5297.2   27.34  5299.8   27.35  5359.9   27.61 5359.99   27.61  5360.1   27.61
 5360.21   27.61  5360.8   27.61    5698   29.68  5737.9   31.83
BR D #Mann= 4
    2788      .2    3500      .1  4967.2    .015  5035.3      .1
BR D Banks=4967.2,5035.3
BC Design=,, 0 ,, 0 ,,,,,,
BC HTab HWMax=32.03
BC Use User HTab Curves=0
BC User HTab FreeFlow(D)= 0

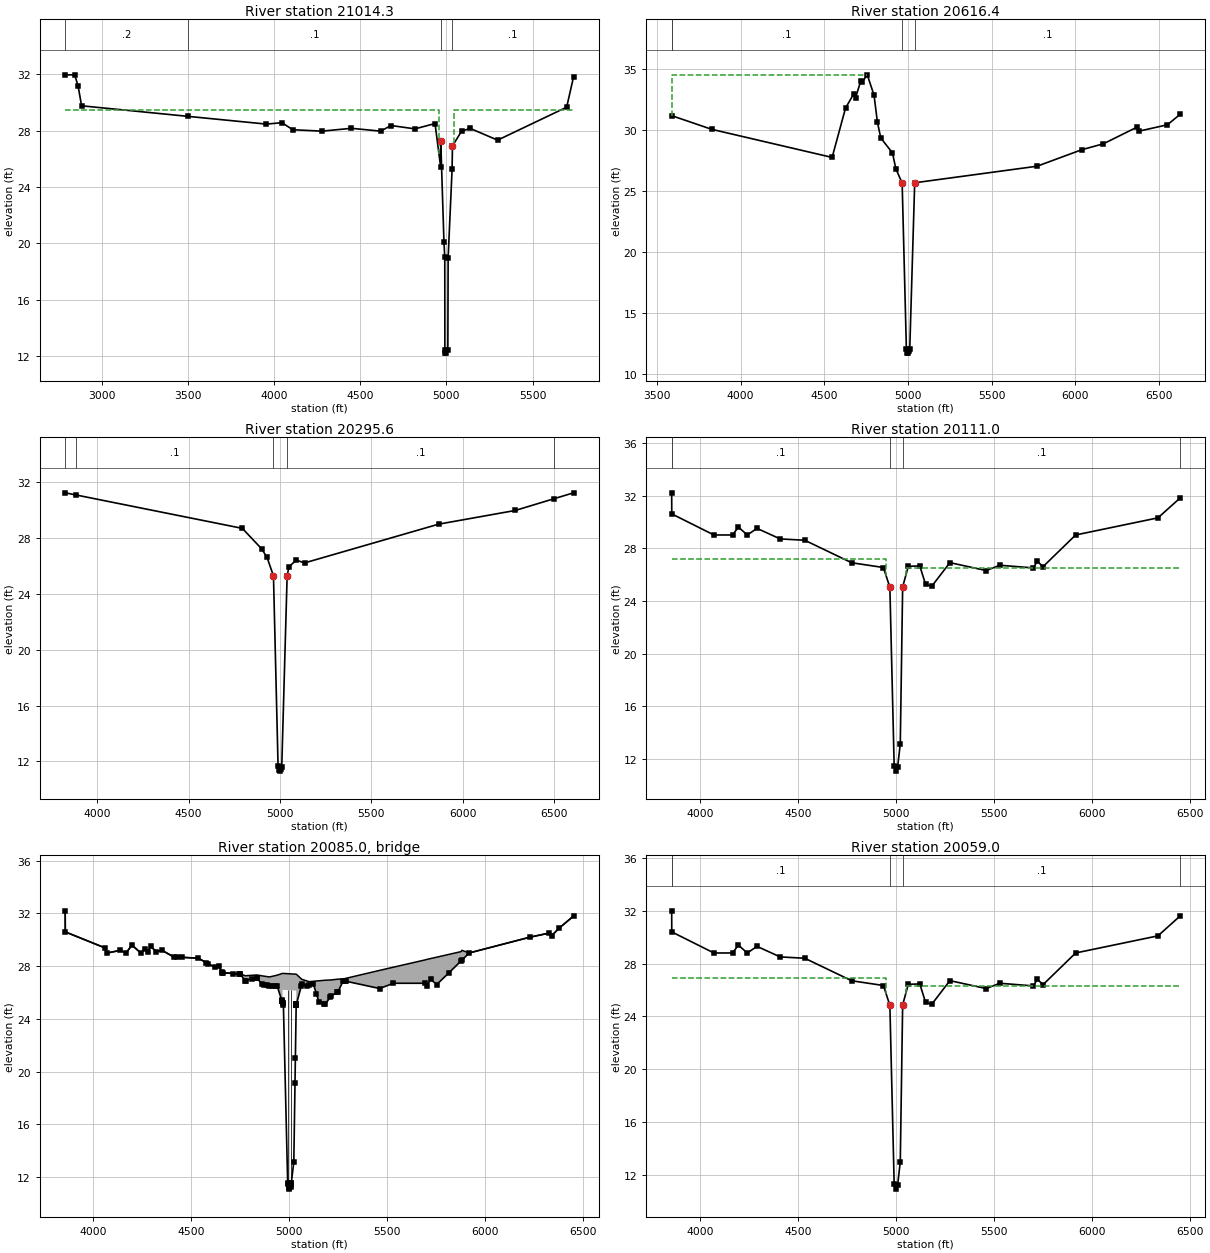
Type RM Length L Ch R = 1 ,21014.3 ,320.1,397.9,408.5
BEGIN DESCRIPTION:
Downstream Section of Bridge/Culvert/Weir
END DESCRIPTION:
XS GIS Cut Line= 6
      3163886.51     13807998.55      3164744.65     13807022.76
      3165099.04     13806613.05      3165441.11     13806210.76
      3165568.78     13806068.64      3165831.36     13805780.77
#Sta/Elev= 30
    2788   31.97    2843   31.97    2863   31.17    2883   29.77    3500   29.02
  3955.7   28.47  4045.7   28.57  4108.7   28.07  4278.7   27.97  4448.7   28.17
  4618.7   27.97  4678.5   28.37  4817.5   28.13  4934.1   28.51  4966.5   25.45
  4967.2    27.3    4986   20.09  4990.7      19  4991.3   12.42  4992.2   12.21
  5000.3    12.2  5008.5   12.42  5010.2   18.97  5033.1   25.25  5035.3   26.91
  5088.1   27.97  5138.7   28.16  5297.2   27.33    5698   29.67  5737.9   31.82
#Mann= 4 ,-1 , 0
    2788      .2       0    3500      .1       0  4967.2    .015       0
  5035.3      .1       0
#XS Ineff= 2 , 0
       0    4957    29.5    5045       0    29.5
Permanent Ineff=
       F       F
Bank Sta=4967.2,5035.3
XS Rating Curve= 0 ,0
Exp/Cntr=0.5,0.3

Type RM Length L Ch R = 1 ,20616.4 ,262.9,320.8,357.2
BEGIN DESCRIPTION:
Cross Section 20616.4-Interpolated
END DESCRIPTION:
XS GIS Cut Line= 6
      3164198.57     13807628.12      3164410.13      13807517.7
      3165297.19     13806637.13      3165841.77     13806206.01
      3166102.16     13806150.65      3166659.91     13806332.16
#Sta/Elev= 28
  3587.8    31.2  3826.4   30.08  4546.4   27.77  4626.4   31.82  4676.4   33.01
  4686.4   32.65  4716.4   34.01  4726.4   33.97  4756.4   34.55  4796.9   32.87
  4816.9   30.67  4836.9   29.37  4906.9   28.14  4926.9   26.85 4964.78   25.66
 4989.98   12.08 4995.38   11.76 4999.38   11.71 5006.58   11.87 5010.08   12.01
 5039.68   25.69  5770.9   27.05  6037.1    28.4  6167.1   28.89  6367.1   30.25
  6377.1   29.92  6549.6   30.45  6624.7    31.3
#Mann= 4 , 1 , 0
  3587.8      .2       0  3587.8      .1       0 4964.78    .015       0
 5039.68      .1       0
#XS Ineff= 2 , 0
       0  4756.4   34.55               0
Permanent Ineff=
       F       F
Bank Sta=4964.78,5039.68
XS Rating Curve= 0 ,0
Exp/Cntr=0.3,0.1

Type RM Length L Ch R = 1 ,20295.6 ,175.5,184.6,105.5
BEGIN DESCRIPTION:
Cross Section 20295.6-Interpolated
END DESCRIPTION:
XS GIS Cut Line= 5
      3164386.82     13807712.34      3165247.78     13807067.74
      3165424.26     13806912.44      3165960.76     13806411.23
      3166698.03     13806362.66
#Sta/Elev= 19
  3824.3    31.2  3886.1   31.04  4794.3   28.66  4899.8    27.2  4929.8   26.58
 4964.78   25.26 4989.98   11.68 4995.38   11.36 4999.38   11.31 5006.58   11.47
 5010.08   11.61 5039.68   25.29  5049.8   25.92  5089.8   26.39  5134.9   26.19
  5869.1   28.96  6289.1   29.94  6498.8   30.77    6608    31.2
#Mann= 5 , 1 , 0
  3824.3      .2       0  3886.1      .1       0 4964.78    .015       0
 5039.68      .1       0  6498.8      .2       0
Bank Sta=4964.78,5039.68
XS Rating Curve= 0 ,0
Exp/Cntr=0.5,0.3

Type RM Length L Ch R = 1 ,20111.0 ,52,52,52
BEGIN DESCRIPTION:
Upstream Section of Bridge/Culvert/Weir
END DESCRIPTION:
XS GIS Cut Line= 6
       3164407.8      13807691.5      3164882.37     13807557.35
      3165113.62     13807384.37      3165901.34     13806512.34
      3165985.65     13806453.32      3166515.61     13806402.73
#Sta/Elev= 30
  3856.1   32.21  3856.6   30.61  4071.6   29.01  4166.6   29.01  4196.6   29.61
  4241.6   29.01  4291.6   29.51  4409.8   28.71    4535   28.61 4774.67    26.9
 4936.49   26.54 4969.38   25.03  4991.3   11.45 4999.48   11.08 5008.79   11.38
 5022.45   13.15 5034.54   25.06 5063.16   26.63 5122.06   26.66 5151.64   25.25
 5183.83   25.13  5275.5   26.91  5460.5   26.31  5530.5   26.71  5701.2   26.51
  5721.2   27.01  5751.2   26.61  5917.2   29.01  6337.2   30.31  6449.6   31.81
#Mann= 5 ,-1 , 0
  3856.1      .2       0  3856.6      .1       0 4969.38    .015       0
 5034.54      .1       0  6449.6      .2       0
#XS Ineff= 2 , 0
       0    4950    27.2    5050       0    26.5
Permanent Ineff=
       F       F
Bank Sta=4969.38,5034.54
XS Rating Curve= 0 ,0
Exp/Cntr=0.5,0.3

Type RM Length L Ch R = 3 ,20085.0 ,,,
BEGIN DESCRIPTION:
TEXAS STREET, SKEW ANGLE OF 30 DEGREES
Structure ID: C06-12
END DESCRIPTION:
Node Name=TEXAS STREET
Bridge Culvert--1,0,-1,-1, 0
Deck Dist Width WeirC Skew NumUp NumDn MinLoCord MaxHiCord MaxSubmerge Is_Ogee
10,32,2.6,0, 51, 51, , , 0.95, 0, 1,1,,
  3856.1  3856.6  4056.6  4071.6  4136.6  4166.6  4196.6  4241.6  4261.6  4276.6
  4291.6  4321.6  4349.8  4409.8    4535    4620  4638.6  4658.6 4749.18 4774.67
 4834.18 4861.76  4898.4 4936.49 4964.85 4964.94 5034.78 5034.89 5063.16 5088.57
  5101.4 5122.06 5151.64 5183.83 5211.93  5246.3  5275.5  5460.5  5530.5  5691.2
  5701.2  5721.2  5751.2  5874.8  5880.4  5917.2  6227.2  6322.2  6337.2  6377.2
  6449.6
    32.2    30.6    29.4      29    29.2      29    29.6      29    29.3    29.1
    29.5    29.1    29.2    28.7   28.61   27.91   28.01   27.51   27.42   27.27
   27.33   27.26   27.18   27.31   27.45   27.45   27.39   27.39      27   26.88
   26.82   26.85   26.89   26.93   26.95   27.01   27.03   27.68   27.92   28.47
   28.51   28.58   28.68    29.1    29.2      29    30.2    30.5    30.3    30.9
    31.8
    32.2    30.6    29.4      29    29.2      29    29.6      29    29.3    29.1
    29.5    29.1    29.2    28.7    28.6    27.9      28    27.5   27.39   26.89
   27.09   26.61   26.53   26.53   25.23    26.2   26.14   25.07   26.62   26.47
   26.54   26.65   25.24   25.12   25.73   26.02    26.9    26.3    26.7    26.7
    26.5      27    26.6   28.38   28.46      29    30.2    30.5    30.3    30.9
    31.8
  3856.1  3856.6  4056.6  4071.6  4136.6  4166.6  4196.6  4241.6  4261.6  4276.6
  4291.6  4321.6  4349.8  4409.8    4535    4620  4638.6  4658.6 4749.18 4774.67
 4834.18 4861.76  4898.4 4936.49 4964.85 4964.94 5034.78 5034.89 5063.16 5088.57
  5101.4 5122.06 5151.64 5183.83 5211.93  5246.3  5275.5  5460.5  5530.5  5691.2
  5701.2  5721.2  5751.2  5874.8  5880.4  5917.2  6227.2  6322.2  6337.2  6377.2
  6449.6
    32.2    30.6    29.4      29    29.2      29    29.6      29    29.3    29.1
    29.5    29.1    29.2    28.7   28.61   27.91   28.01   27.51   27.42   27.27
   27.33   27.26   27.18   27.31   27.45   27.45   27.39   27.39      27   26.88
   26.82   26.85   26.89   26.93   26.95   27.01   27.03   27.68   27.92   28.47
   28.51   28.58   28.68    29.1    29.2      29    30.2    30.5    30.3    30.9
    31.8
   32.04   30.44   29.24   28.84   29.04   28.84   29.44   28.84   29.14   28.94
   29.34   28.94   29.04   28.54   28.44   27.74   27.84   27.34   27.23   26.73
   26.93   26.45   26.37   26.37   25.07   26.04   25.98   24.91   26.46   26.31
   26.38   26.49   25.08   24.96   25.57   25.86   26.74   26.14   26.54   26.54
   26.34   26.84   26.44   28.22    28.3   28.84   30.04   30.34   30.14   30.74
   31.64
Pier Skew, UpSta & Num, DnSta & Num=  ,4991.3, 2 ,4991.3, 2 , 0 , 0 , 0 ,,
       2       2
   10.37   27.17
       2       2
   10.21   27.01
Pier Skew, UpSta & Num, DnSta & Num=  ,5009.4, 2 ,5009.4, 2 , 0 , 0 , 0 ,,
       2       2
   10.35   27.15
       2       2
   10.19   26.99
Abutment Skew #Up #Dn= , 2 , 2
 4964.74 4991.21
    26.2    11.5
 4964.74 4991.21
   26.04   11.34
Abutment Skew #Up #Dn= , 2 , 2
 5030.45 5034.98
   21.02   26.14
 5030.45 5034.98
   20.86   25.98
BR Coef= 1 , 1 , 0 ,1.25, 0 ,,,0.8,-1,2,0,
WSPro=,,,, 1 ,,,, 0 ,,,, 0 ,,,,-1 ,-1 ,-1 , 0 , 0 , 0 , 0 , 0
BR U #Sta/Elev= 96
  3856.1    32.2  3856.6    30.6  4056.6    29.4  4071.6      29  4136.6    29.2
  4166.6      29  4196.6    29.6  4241.6      29  4261.6    29.3  4276.6    29.1
  4291.6    29.5  4321.6    29.1  4349.8    29.2  4409.8    28.7    4425   28.69
    4450   28.67    4535    28.6    4575   28.27    4585   28.19    4620    27.9
  4638.6      28    4655   27.59  4658.6    27.5    4660    27.5  4711.6   27.44
  4742.6    27.4 4749.09   27.39 4749.18   27.39 4774.67   26.89  4776.5    26.9
 4807.64   27.03  4833.5   27.09 4834.18   27.09 4861.76   26.61  4868.1   26.59
 4886.73   26.54  4898.4   26.53 4911.17   26.51  4924.4   26.52 4936.49   26.53
  4959.7   25.46 4962.29   25.35  4962.4   25.34 4962.51   25.34 4964.85   25.23
 4964.94   25.22 4969.38   25.02 4991.21    11.5  4991.3   11.44    4996   11.12
 4999.48   11.07 5005.74   11.23 5008.79   11.37 5008.87   11.52  5009.4    11.5
 5022.45   13.14  5028.5    19.1 5030.45   21.02 5034.54   25.05 5034.78   25.06
 5034.89   25.07  5035.1   25.08 5035.59   25.11  5035.7   25.11 5035.81   25.12
  5060.3   26.46 5063.16   26.62 5088.57   26.47  5101.4   26.54 5122.06   26.65
    5138   25.89 5151.64   25.24  5176.7   25.15 5183.83   25.12    5209   25.67
 5211.93   25.73  5245.3   26.01  5246.3   26.02  5275.5    26.9  5283.4   26.87
  5289.4   26.85  5460.5    26.3  5530.5    26.7  5691.2    26.7  5701.2    26.5
  5721.2      27  5751.2    26.6  5814.3    27.5  5874.8   28.38  5880.4   28.46
  5917.2      29  6227.2    30.2  6322.2    30.5  6337.2    30.3  6377.2    30.9
  6449.6    31.8
BR U #Mann= 5
  3856.1      .2  3856.6      .1 4969.38    .015 5034.54      .1  6449.6      .2
BR U Banks=4969.38,5034.54
BR D #Sta/Elev= 96
  3856.1   32.04  3856.6   30.44  4056.6   29.24  4071.6   28.84  4136.6   29.04
  4166.6   28.84  4196.6   29.44  4241.6   28.84  4261.6   29.14  4276.6   28.94
  4291.6   29.34  4321.6   28.94  4349.8   29.04  4409.8   28.54    4425   28.53
    4450   28.51    4535   28.44    4575   28.11    4585   28.03    4620   27.74
  4638.6   27.84    4655   27.43  4658.6   27.34    4660   27.34  4711.6   27.28
  4742.6   27.24 4749.09   27.23 4749.18   27.23 4774.67   26.73  4776.5   26.74
 4807.64   26.87  4833.5   26.93 4834.18   26.93 4861.76   26.45  4868.1   26.43
 4886.73   26.38  4898.4   26.37 4911.17   26.35  4924.4   26.36 4936.49   26.37
  4959.7    25.3 4962.29   25.19  4962.4   25.18 4962.51   25.18 4964.85   25.07
 4964.94   25.06 4969.38   24.86 4991.21   11.34  4991.3   11.28    4996   10.96
 4999.48   10.91 5005.74   11.07 5008.79   11.21 5008.87   11.36  5009.4   11.34
 5022.45   12.98  5028.5   18.94 5030.45   20.86 5034.54   24.89 5034.78    24.9
 5034.89   24.91  5035.1   24.92 5035.59   24.95  5035.7   24.95 5035.81   24.96
  5060.3    26.3 5063.16   26.46 5088.57   26.31  5101.4   26.38 5122.06   26.49
    5138   25.73 5151.64   25.08  5176.7   24.99 5183.83   24.96    5209   25.51
 5211.93   25.57  5245.3   25.85  5246.3   25.86  5275.5   26.74  5283.4   26.71
  5289.4   26.69  5460.5   26.14  5530.5   26.54  5691.2   26.54  5701.2   26.34
  5721.2   26.84  5751.2   26.44  5814.3   27.34  5874.8   28.22  5880.4    28.3
  5917.2   28.84  6227.2   30.04  6322.2   30.34  6337.2   30.14  6377.2   30.74
  6449.6   31.64
BR D #Mann= 5
  3856.1      .2  3856.6      .1 4969.38    .015 5034.54      .1  6449.6      .2
BR D Banks=4969.38,5034.54
BC Design=,, 0 ,, 0 ,,,,,,
BC HTab HWMax=32.21
BC Use User HTab Curves=0
BC User HTab FreeFlow(D)= 0

Type RM Length L Ch R = 1 ,20059.0 ,362.1,269.3,176.5
BEGIN DESCRIPTION:
Downstream Section of Bridge/Culvert/Weir
END DESCRIPTION:
XS GIS Cut Line= 6
        3164426.     13807740.22      3164900.57     13807606.07
      3165131.82     13807433.09      3165919.54     13806561.06
      3166003.85     13806502.04      3166533.81     13806451.45
#Sta/Elev= 30
  3856.1   32.02  3856.6   30.42  4071.6   28.82  4166.6   28.82  4196.6   29.42
  4241.6   28.82  4291.6   29.32  4409.8   28.52    4535   28.42 4774.67   26.71
 4936.49   26.35 4969.38   24.84  4991.3   11.26 4999.48   10.89 5008.79   11.19
 5022.45   12.96 5034.54   24.87 5063.16   26.44 5122.06   26.47 5151.64   25.06
 5183.83   24.94  5275.5   26.72  5460.5   26.12  5530.5   26.52  5701.2   26.32
  5721.2   26.82  5751.2   26.42  5917.2   28.82  6337.2   30.12  6449.6   31.62
#Mann= 5 ,-1 , 0
  3856.1      .2       0  3856.6      .1       0 4969.38    .015       0
 5034.54      .1       0  6449.6      .2       0
#XS Ineff= 2 , 0
       0    4950    26.9    5050       0    26.3
Permanent Ineff=
       F       F
Bank Sta=4969.38,5034.54
XS Rating Curve= 0 ,0
Exp/Cntr=0.5,0.3

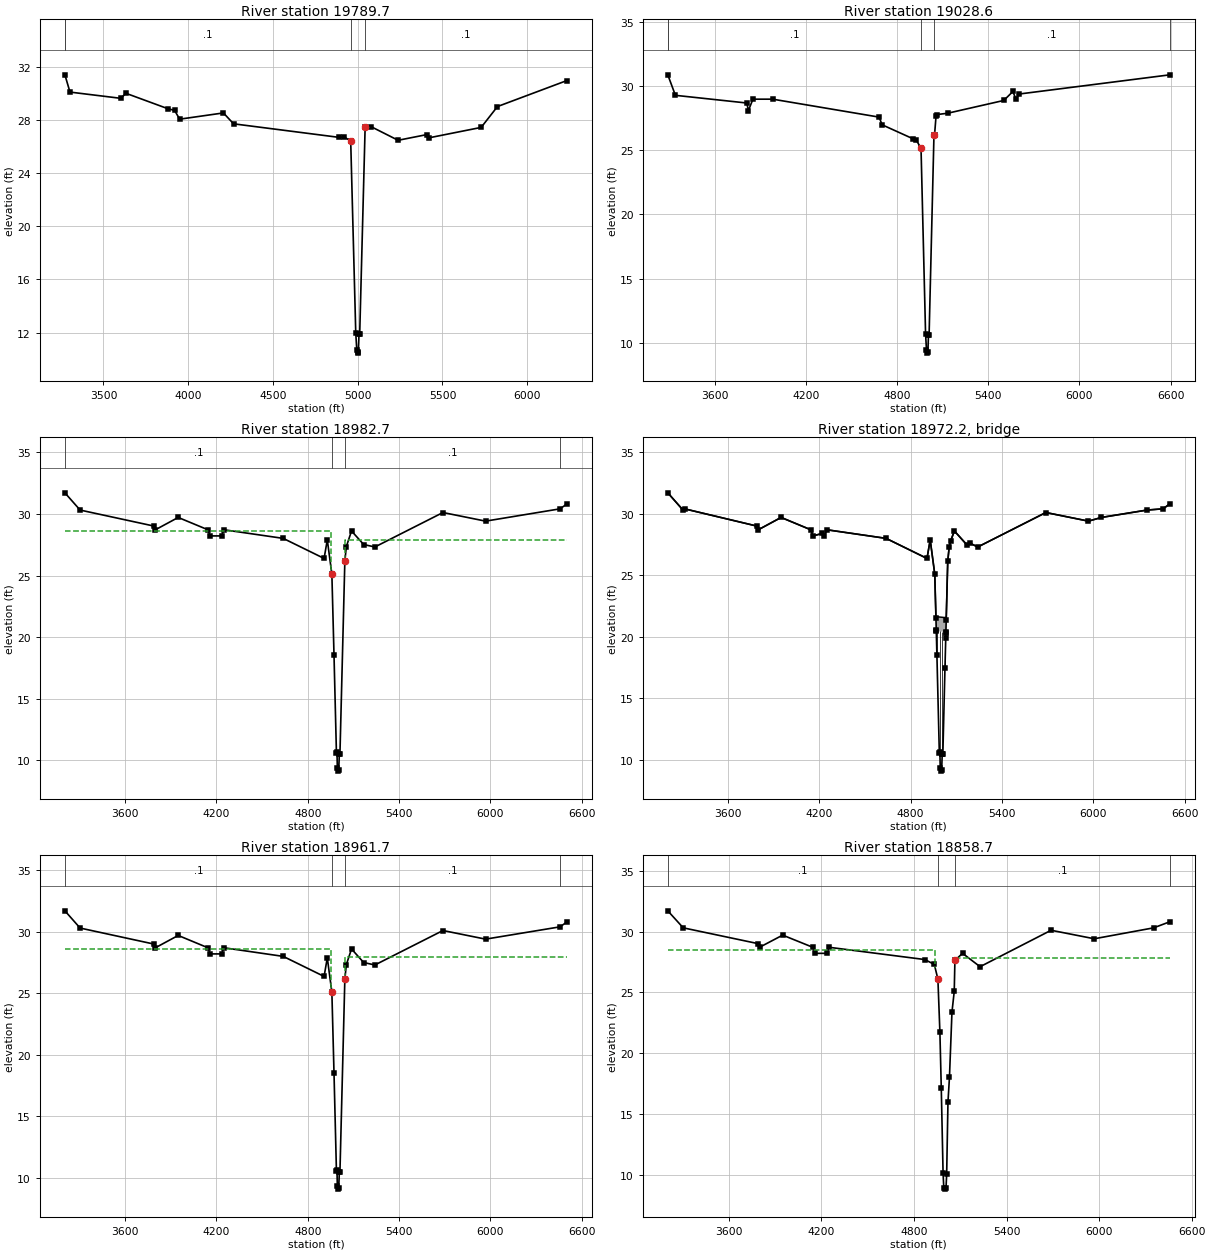
Type RM Length L Ch R = 1 ,19789.7 ,526.5,761.1,877.3
BEGIN DESCRIPTION:
Cross Section 19789.7-Interpolated
END DESCRIPTION:
XS GIS Cut Line= 6
      3163956.65     13807916.88      3164554.15     13808024.86
      3164877.59      13807970.2      3165396.02     13807526.59
      3166229.02     13807103.04      3166638.52     13807083.22
#Sta/Elev= 26
  3272.3   31.41  3302.3   30.11  3602.3   29.64  3632.3   30.02  3879.5   28.86
  3919.5   28.73  3949.5   28.07  4207.5   28.54  4267.5   27.72  4889.8    26.7
  4919.8   26.72 4958.49   26.44 4988.39   11.95 4994.39    10.7 4998.89   10.45
 5003.59   10.52 5007.49   11.86 5011.59   11.87 5043.69   27.49  5079.8    27.5
  5238.2   26.48  5408.2   26.91  5418.2   26.66  5728.2   27.45  5824.3   29.02
  6234.3   30.98
#Mann= 4 , 1 , 0
  3272.3      .2       0  3272.3      .1       0 4958.49    .015       0
 5043.69      .1       0
Bank Sta=4958.49,5043.69
XS Rating Curve= 0 ,0
Exp/Cntr=0.3,0.1

Type RM Length L Ch R = 1 ,19028.6 ,45.8,45.9,50.3
BEGIN DESCRIPTION:
Cross Section 19028.6-Interpolated
END DESCRIPTION:
XS GIS Cut Line= 5
      3164040.64     13807950.15       3164690.1      13808183.1
      3165614.86     13808197.22      3165770.16     13808204.28
      3167302.02     13808246.64
#Sta/Elev= 27
  3292.6    30.9  3342.6    29.3  3812.6    28.7  3822.6    28.1  3852.6      29
  3982.6      29  4682.6    27.6  4702.6      27  4907.4    25.9  4927.4    25.8
 4958.49   25.17 4988.39   10.68 4994.39    9.43 4998.89    9.18 5003.59    9.25
 5007.49   10.59 5011.59    10.6 5043.69   26.22  5047.4    26.2  5057.4    27.7
  5062.9    27.8  5132.9    27.9  5502.9    28.9  5562.9    29.6  5582.9      29
  5602.9    29.4  6595.4    30.9
#Mann= 5 , 1 , 0
  3292.6      .2       0  3292.6      .1       0 4958.49    .015       0
 5043.69      .1       0  6595.4      .2       0
Bank Sta=4958.49,5043.69
XS Rating Curve= 0 ,0
Exp/Cntr=0.5,0.3

Type RM Length L Ch R = 1 ,18982.7 ,21,21,21
BEGIN DESCRIPTION:
Upstream Section of Bridge/Culvert/Weir
END DESCRIPTION:
XS GIS Cut Line= 6
      3163956.09     13807959.52       3164682.2     13808222.41
      3165662.67     13808246.85      3165706.05     13808247.35
      3165728.34     13808250.68      3167208.44     13808304.18
#Sta/Elev= 30
  3203.6   31.72  3303.6   30.32  3788.6   29.02  3798.6   28.72  3948.4   29.72
  4143.4   28.72  4158.4   28.22  4233.4   28.22  4248.4   28.72  4638.4   28.02
 4907.29   26.39 4928.39    27.9 4958.49    25.1 4972.39   18.58 4988.39   10.61
 4991.99    10.7 4994.39    9.36 4998.89    9.11 5003.59    9.18 5007.49   10.52
 5011.59   10.53 5043.69   26.15 5053.29   27.34  5087.6   28.62  5167.6   27.52
  5241.1   27.32  5688.7   30.12  5968.7   29.42  6458.6   30.42  6503.6   30.82
#Mann= 4 ,-1 , 0
  3203.6      .1       0 4958.49    .015       0 5043.69      .1       0
  6458.6      .2       0
#XS Ineff= 2 , 0
       0    4956    28.6    5044       0    27.9
Permanent Ineff=
       F       F
Bank Sta=4958.49,5043.69
XS Rating Curve= 0 ,0
Exp/Cntr=0.5,0.3

Type RM Length L Ch R = 3 ,18972.2 ,,,
BEGIN DESCRIPTION:
14" PIPELINE
END DESCRIPTION:
Bridge Culvert--1,0,-1,-1, 0
Deck Dist Width WeirC Skew NumUp NumDn MinLoCord MaxHiCord MaxSubmerge Is_Ogee
10,1,2.6,0, 45, 45, , , 0.95, 0, 1,1,,
  3203.6  3303.6  3313.6  3788.6  3798.6  3948.4  4143.4  4158.4  4218.4  4233.4
  4248.4  4638.4 4907.29 4928.39 4958.49 4966.09  4968.2 4968.29 4972.39 4988.39
 4991.99 4994.39 4998.89 5003.59 5007.49 5007.59 5011.59 5025.39 5030.59 5031.48
 5031.59 5033.69 5043.69 5053.29 5063.39  5087.6  5167.6  5191.1  5241.1  5688.7
  5968.7  6053.7  6353.7  6458.6  6503.6
    31.7    30.3    30.4      29    28.7    29.7    28.7    28.2    28.4    28.2
    28.7      28   26.37   27.88   25.08   21.64   21.64   21.64   21.63   21.61
   21.61    21.6    21.6   21.59   21.59   21.59   21.58   21.57   21.56   21.55
   21.55   21.53   26.13   27.32   27.82    28.6    27.5    27.6    27.3    30.1
    29.4    29.7    30.3    30.4    30.8
    31.7    30.3    30.4      29    28.7    29.7    28.7    28.2    28.4    28.2
    28.7      28   26.37   27.88   25.08   21.52   20.53   20.48   20.46   20.44
   20.44   20.43   20.43   20.42   20.42   20.42   20.41    20.4   20.39   20.38
   20.38   21.38   26.13   27.32   27.82    28.6    27.5    27.6    27.3    30.1
    29.4    29.7    30.3    30.4    30.8
  3203.6  3303.6  3313.6  3788.6  3798.6  3948.4  4143.4  4158.4  4218.4  4233.4
  4248.4  4638.4 4907.29 4928.39 4958.49 4966.09  4968.2 4968.29 4972.39 4988.39
 4991.99 4994.39 4998.89 5003.59 5007.49 5007.59 5011.59 5025.39 5030.59 5031.48
 5031.59 5033.69 5043.69 5053.29 5063.39  5087.6  5167.6  5191.1  5241.1  5688.7
  5968.7  6053.7  6353.7  6458.6  6503.6
    31.7    30.3    30.4      29    28.7    29.7    28.7    28.2    28.4    28.2
    28.7      28   26.37   27.88   25.08   21.64   21.64   21.64   21.63   21.61
   21.61    21.6    21.6   21.59   21.59   21.59   21.58   21.57   21.56   21.55
   21.55   21.53   26.13   27.32   27.82    28.6    27.5    27.6    27.3    30.1
    29.4    29.7    30.3    30.4    30.8
    31.7    30.3    30.4      29    28.7    29.7    28.7    28.2    28.4    28.2
    28.7      28   26.37   27.88   25.08   21.52   20.53   20.48   20.46   20.44
   20.44   20.43   20.43   20.42   20.42   20.42   20.41    20.4   20.39   20.38
   20.38   21.38   26.13   27.32   27.82    28.6    27.5    27.6    27.3    30.1
    29.4    29.7    30.3    30.4    30.8
Pier Skew, UpSta & Num, DnSta & Num=  ,4972.4, 2 ,4972.4, 2 , 0 , 0 , 0 ,,
       1       1
   17.31   21.46
       1       1
   17.31   21.46
Pier Skew, UpSta & Num, DnSta & Num=  ,4992, 2 ,4992, 2 , 0 , 0 , 0 ,,
       1       1
     9.4   21.44
       1       1
     9.4   21.44
Pier Skew, UpSta & Num, DnSta & Num=  ,5007.6, 2 ,5007.6, 2 , 0 , 0 , 0 ,,
       1       1
    9.36   21.42
       1       1
    9.36   21.42
Pier Skew, UpSta & Num, DnSta & Num=  ,5025.4, 2 ,5025.4, 2 , 0 , 0 , 0 ,,
       1       1
   16.19    21.4
       1       1
   16.19    21.4
BR Coef= 1 , 1 , 0 ,1.25, 0 ,,,0.8,0,2,0,
WSPro=,,,, 1 ,,,, 0 ,,,, 0 ,,,,-1 ,-1 ,-1 , 0 , 0 , 0 , 0 , 0
BR U #Sta/Elev= 45
  3203.6    31.7  3303.6    30.3  3313.6    30.4  3788.6      29  3798.6    28.7
  3948.4    29.7  4143.4    28.7  4158.4    28.2  4218.4    28.4  4233.4    28.2
  4248.4    28.7  4638.4      28 4907.29   26.37 4928.39   27.88 4958.49   25.08
 4966.09   21.52  4968.2   20.53 4968.29   20.48 4972.39   18.56 4988.39   10.59
 4991.99   10.68 4994.39    9.34 4998.89    9.09 5003.59    9.16 5007.49    10.5
 5007.59    10.5 5011.59   10.51 5025.39   17.44 5030.59   19.91 5031.48   20.33
 5031.59   20.38 5033.69   21.38 5043.69   26.13 5053.29   27.32 5063.39   27.82
  5087.6    28.6  5167.6    27.5  5191.1    27.6  5241.1    27.3  5688.7    30.1
  5968.7    29.4  6053.7    29.7  6353.7    30.3  6458.6    30.4  6503.6    30.8
BR U #Mann= 5
  3203.6      .2  3203.6      .1 4958.49    .015 5043.69      .1  6458.6      .2
BR U Banks=4958.49,5043.69
BR D #Sta/Elev= 45
  3203.6    31.7  3303.6    30.3  3313.6    30.4  3788.6      29  3798.6    28.7
  3948.4    29.7  4143.4    28.7  4158.4    28.2  4218.4    28.4  4233.4    28.2
  4248.4    28.7  4638.4      28 4907.29   26.37 4928.39   27.88 4958.49   25.08
 4966.09   21.52  4968.2   20.53 4968.29   20.48 4972.39   18.56 4988.39   10.59
 4991.99   10.68 4994.39    9.34 4998.89    9.09 5003.59    9.16 5007.49    10.5
 5007.59    10.5 5011.59   10.51 5025.39   17.44 5030.59   19.91 5031.48   20.33
 5031.59   20.38 5033.69   21.38 5043.69   26.13 5053.29   27.32 5063.39   27.82
  5087.6    28.6  5167.6    27.5  5191.1    27.6  5241.1    27.3  5688.7    30.1
  5968.7    29.4  6053.7    29.7  6353.7    30.3  6458.6    30.4  6503.6    30.8
BR D #Mann= 5
  3203.6      .2  3203.6      .1 4958.49    .015 5043.69      .1  6458.6      .2
BR D Banks=4958.49,5043.69
BC Design=,, 0 ,, 0 ,,,,,,
BC HTab HWMax=31.72
BC Use User HTab Curves=0
BC User HTab FreeFlow(D)= 0

Type RM Length L Ch R = 1 ,18961.7 ,104,103,102
BEGIN DESCRIPTION:
Downstream Section of Bridge/Culvert/Weir
END DESCRIPTION:
XS GIS Cut Line= 6
      3163955.53     13807980.51      3164681.64     13808243.41
      3165662.11     13808267.85      3165705.49     13808268.35
      3165727.78     13808271.68      3167207.88     13808325.17
#Sta/Elev= 30
  3203.6   31.68  3303.6   30.28  3788.6   28.98  3798.6   28.68  3948.4   29.68
  4143.4   28.68  4158.4   28.18  4233.4   28.18  4248.4   28.68  4638.4   27.98
 4907.29   26.35 4928.39   27.86 4958.49   25.06 4972.39   18.54 4988.39   10.57
 4991.99   10.66 4994.39    9.32 4998.89    9.07 5003.59    9.14 5007.49   10.48
 5011.59   10.49 5043.69   26.11 5053.29    27.3  5087.6   28.58  5167.6   27.48
  5241.1   27.28  5688.7   30.08  5968.7   29.38  6458.6   30.38  6503.6   30.78
#Mann= 4 ,-1 , 0
  3203.6      .1       0 4958.49    .015       0 5043.69      .1       0
  6458.6      .2       0
#XS Ineff= 2 , 0
       0    4956    28.6    5044       0    27.9
Permanent Ineff=
       F       F
Bank Sta=4958.49,5043.69
XS Rating Curve= 0 ,0
Exp/Cntr=0.5,0.3

Type RM Length L Ch R = 1 ,18858.7 ,116,116,116
BEGIN DESCRIPTION:
Upstream Section of Bridge/Culvert/Weir
END DESCRIPTION:
XS GIS Cut Line= 6
      3163994.94     13808014.23      3164277.88     13808234.71
      3164533.09     13808310.68      3164932.77     13808329.13
      3165784.57     13808381.14      3167159.62     13808445.02
#Sta/Elev= 30
  3203.6   31.72  3303.6   30.32  3788.6   29.02  3798.6   28.72  3948.4   29.72
  4143.4   28.72  4158.4   28.22  4233.4   28.22  4248.4   28.72  4869.5   27.71
  4931.5   27.31  4954.8    26.1  4967.8   21.71  4976.6   17.17  4988.4    10.1
    4993    8.93  4999.9    8.81  5007.5    8.94  5011.6   10.02    5020   15.96
  5029.7   18.01    5046   23.39  5060.7   25.08  5065.1   27.64  5114.7   28.22
  5228.2   27.12  5688.7   30.12  5968.7   29.42  6353.7   30.32  6458.6   30.82
#Mann= 4 ,-1 , 0
  3203.6      .1       0  4954.8    .015       0  5065.1      .1       0
  6458.6      .2       0
#XS Ineff= 2 , 0
       0    4937    28.5    5073       0    27.8
Permanent Ineff=
       F       F
Bank Sta=4954.8,5065.1
XS Rating Curve= 0 ,0
Exp/Cntr=0.5,0.3