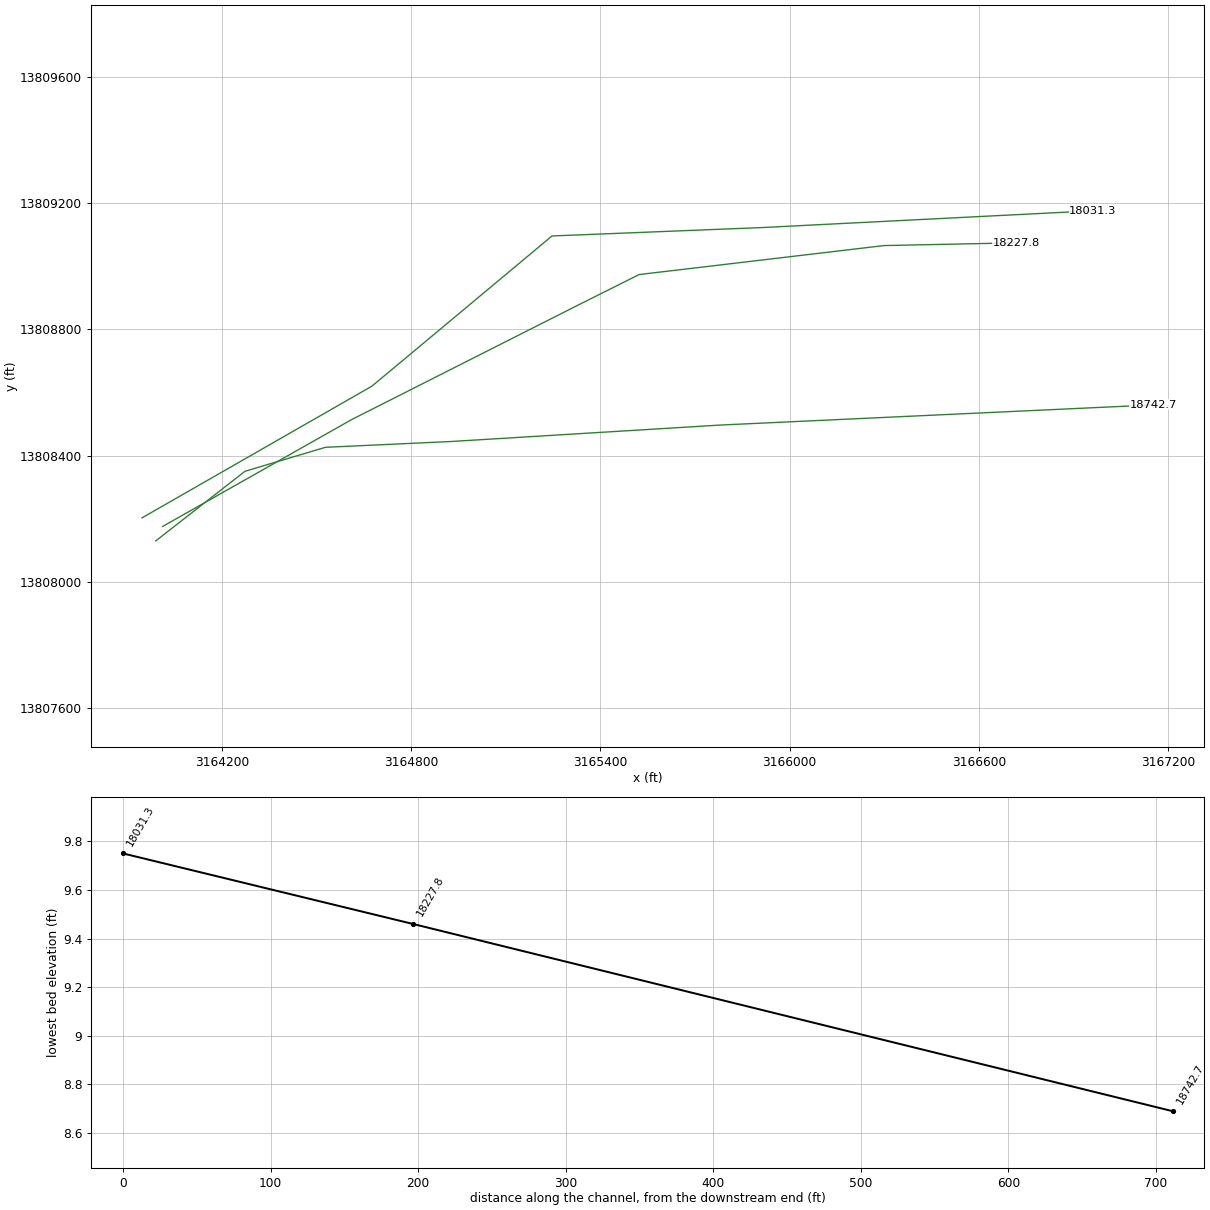
HEC-RAS study C106-00-00.PRJ: C106-00-00 2015

--- C106-00-00.g01 (geometry) --- (continued)

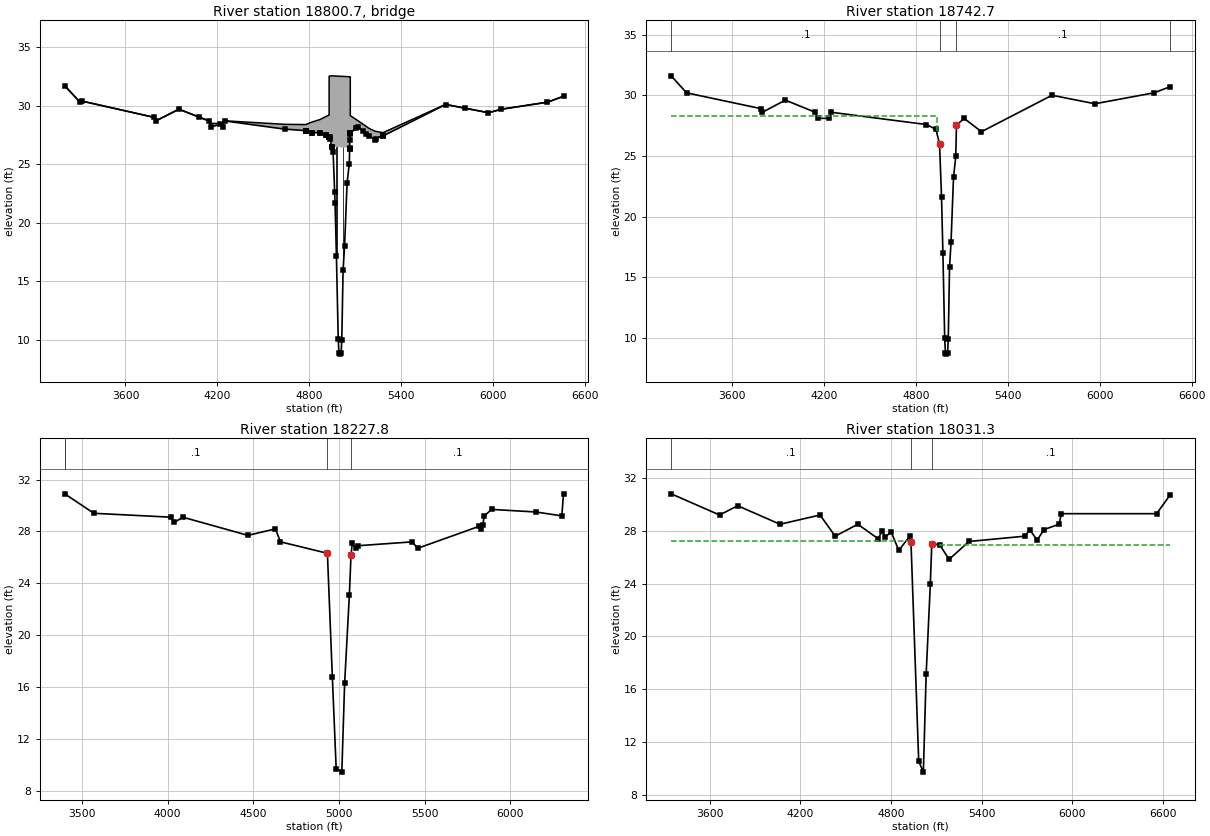
Type RM Length L Ch R = 3 ,18800.7 ,,,
BEGIN DESCRIPTION:
SPENCER HWY
Structure ID: C06-10
END DESCRIPTION:
Node Name=SPENCER HWY
Bridge Culvert--1,0,-1,-1, 0
Deck Dist Width WeirC Skew NumUp NumDn MinLoCord MaxHiCord MaxSubmerge Is_Ogee
10,96,2.6,0, 34, 34, , , 0.95, 0, 1,1,,
  3203.6  3303.6  3313.6  3788.6  3798.6  3948.4  4143.4  4158.4  4218.4  4233.4
  4248.4  4638.4  4776.9  4814.3  4869.5 4928.79  4928.9  4931.5 4946.91    5063
  5064.1  5065.1  5067.1 5067.21  5114.7  5189.6  5228.2  5280.6  5280.7  5688.7
  5968.7  6053.7  6353.7  6458.6
    31.7    30.3    30.4      29    28.7    29.7   28.71   28.49   28.48   28.48
   28.71   28.41   28.39   28.59   28.82   29.21   32.51   32.53   32.55   32.47
   32.47   32.46   32.45   29.15   28.74   28.06   27.82    27.7    27.7   30.11
    29.4    29.7    30.3    30.8
    31.7    30.3    30.4      29    28.7    29.7    28.7    28.2    28.4    28.2
    28.7      28   27.87    27.7   27.69   27.31   27.31   27.29   26.49    26.4
   27.04   27.62   27.64   27.64    28.2   27.44    27.1    27.5   27.41    30.1
    29.4    29.7    30.3    30.8
  3203.6  3303.6  3313.6  3788.6  3798.6  3948.4  4143.4  4158.4  4218.4  4233.4
  4248.4  4638.4  4776.9  4814.3  4869.5 4928.79  4928.9  4931.5 4946.91    5063
  5064.1  5065.1  5067.1 5067.21  5114.7  5189.6  5228.2  5280.6  5280.7  5688.7
  5968.7  6053.7  6353.7  6458.6
    31.7    30.3    30.4      29    28.7    29.7   28.71   28.49   28.48   28.48
   28.71   28.41   28.39   28.59   28.82   29.21   32.51   32.53   32.55   32.47
   32.47   32.46   32.45   29.15   28.74   28.06   27.82    27.7    27.7   30.11
    29.4    29.7    30.3    30.8
   31.58   30.18   30.28   28.88   28.58   29.58   28.58   28.08   28.28   28.08
   28.58   27.88   27.75   27.58   27.57   27.19   27.19   27.17   26.37   26.28
   26.92    27.5   27.52   27.52   28.08   27.32   26.98   27.38   27.29   29.98
   29.28   29.58   30.18   30.68
Pier Skew, UpSta & Num, DnSta & Num=  ,4976.6, 2 ,4976.6, 2 , 0 , 0 , 0 ,,
     1.3     1.3
   15.76   27.48
     1.3     1.3
   15.64   27.36
Pier Skew, UpSta & Num, DnSta & Num=  ,5020, 2 ,5020, 2 , 0 , 0 , 0 ,,
     1.3     1.3
   14.48   27.45
     1.3     1.3
   14.36   27.33
BR Coef= 1 , 1 , 0 ,1.25, 0 ,,,0.8,-1,2,0,
WSPro=,,,, 1 ,,,, 0 ,,,, 0 ,,,,-1 ,-1 ,-1 , 0 , 0 , 0 , 0 , 0
BR U #Sta/Elev= 67
  3203.6    31.7  3303.6    30.3  3313.6    30.4  3788.6      29  3798.6    28.7
  3948.4    29.7  4077.9   29.04  4143.4    28.7  4158.4    28.2  4218.4    28.4
  4233.4    28.2  4248.4    28.7  4638.4      28    4776   27.87  4776.9   27.87
  4779.3   27.86  4814.3    27.7  4816.4    27.7    4869   27.69  4869.5   27.69
  4910.9   27.46  4911.1   27.46 4928.79   27.31  4928.9   27.31 4929.01   27.31
  4931.5   27.29  4934.1   27.15 4946.91   26.49    4947   26.49  4947.1   26.48
  4954.8   26.08  4965.1   22.61  4967.8   21.69  4976.6   17.15  4988.4   10.08
    4993    8.91  4999.9    8.79  5007.5    8.92  5011.6      10    5020   15.94
  5029.7   17.99    5046   23.37  5060.7   25.06  5062.8   26.28 5062.89   26.33
    5063    26.4  5064.1   27.04  5065.1   27.62 5066.99   27.64  5067.1   27.64
 5067.21   27.64  5102.4   28.06  5114.7    28.2  5146.9   27.86  5171.1   27.61
  5189.6   27.44  5228.2    27.1  5234.5   27.15  5280.6    27.5  5280.7   27.41
    5283   27.43  5688.7    30.1  5813.6   29.79  5968.7    29.4  6053.7    29.7
  6353.7    30.3  6458.6    30.8
BR U #Mann= 4
  3203.6      .1  4954.8    .015  5065.1      .1  6458.6      .2
BR U Banks=4954.8,5065.1
BR D #Sta/Elev= 67
  3203.6   31.58  3303.6   30.18  3313.6   30.28  3788.6   28.88  3798.6   28.58
  3948.4   29.58  4077.9   28.92  4143.4   28.58  4158.4   28.08  4218.4   28.28
  4233.4   28.08  4248.4   28.58  4638.4   27.88    4776   27.75  4776.9   27.75
  4779.3   27.74  4814.3   27.58  4816.4   27.58    4869   27.57  4869.5   27.57
  4910.9   27.34  4911.1   27.34 4928.79   27.19  4928.9   27.19 4929.01   27.19
  4931.5   27.17  4934.1   27.03 4946.91   26.37    4947   26.37  4947.1   26.36
  4954.8   25.96  4965.1   22.49  4967.8   21.57  4976.6   17.03  4988.4    9.96
    4993    8.79  4999.9    8.67  5007.5     8.8  5011.6    9.88    5020   15.82
  5029.7   17.87    5046   23.25  5060.7   24.94  5062.8   26.16 5062.89   26.21
    5063   26.28  5064.1   26.92  5065.1    27.5 5066.99   27.52  5067.1   27.52
 5067.21   27.52  5102.4   27.94  5114.7   28.08  5146.9   27.74  5171.1   27.49
  5189.6   27.32  5228.2   26.98  5234.5   27.03  5280.6   27.38  5280.7   27.29
    5283   27.31  5688.7   29.98  5813.6   29.67  5968.7   29.28  6053.7   29.58
  6353.7   30.18  6458.6   30.68
BR D #Mann= 4
  3203.6      .1  4954.8    .015  5065.1      .1  6458.6      .2
BR D Banks=4954.8,5065.1
BC Design=,, 0 ,, 0 ,,,,,,
BC HTab HWMax=31.72
BC Use User HTab Curves=0
BC User HTab FreeFlow(D)= 0

Type RM Length L Ch R = 1 ,18742.7 ,456.6,514.9,545.1
BEGIN DESCRIPTION:
Downstream Section of Bridge/Culvert/Weir
END DESCRIPTION:
XS GIS Cut Line= 6
      3163990.29     13808130.14      3164273.22     13808350.61
      3164528.43     13808426.58      3164928.11     13808445.03
      3165779.91     13808497.04      3167154.96     13808560.92
#Sta/Elev= 30
  3203.6    31.6  3303.6    30.2  3788.6    28.9  3798.6    28.6  3948.4    29.6
  4143.4    28.6  4158.4    28.1  4233.4    28.1  4248.4    28.6  4869.5   27.59
  4931.5   27.19  4954.8   25.98  4967.8   21.59  4976.6   17.05  4988.4    9.98
    4993    8.81  4999.9    8.69  5007.5    8.82  5011.6     9.9    5020   15.84
  5029.7   17.89    5046   23.27  5060.7   24.96  5065.1   27.52  5114.7    28.1
  5228.2      27  5688.7      30  5968.7    29.3  6353.7    30.2  6458.6    30.7
#Mann= 4 ,-1 , 0
  3203.6      .1       0  4954.8    .015       0  5065.1      .1       0
  6458.6      .2       0
#XS Ineff= 2 , 0
       0    4937    28.3    5073       0    27.6
Permanent Ineff=
       F       F
Bank Sta=4954.8,5065.1
XS Rating Curve= 0 ,0
Exp/Cntr=0.5,0.3

Type RM Length L Ch R = 1 ,18227.8 ,190,196.5,193.9
BEGIN DESCRIPTION:
Cross Section 18227.8-Interpolated
END DESCRIPTION:
XS GIS Cut Line= 6
      3164012.41     13808176.05      3164612.44     13808514.89
      3165325.43     13808874.91      3165523.09     13808973.74
      3166299.61     13809065.51      3166719.45     13809074.26
#Sta/Elev= 28
  3399.6    30.9  3569.6    29.4  4019.6    29.1  4039.6    28.7  4088.7    29.1
  4468.7    27.7  4628.7    28.2  4658.7    27.2  4932.4   26.32  4961.3   16.77
  4983.6    9.73  5016.5    9.46  5032.9    16.3  5060.5   23.08  5070.1   26.17
  5077.4    27.1  5097.4    26.7  5108.4    26.9  5428.4    27.2  5458.4    26.7
  5818.4    28.4  5828.4    28.2  5838.4    28.5  5848.4    29.2  5890.3    29.7
  6150.3    29.5  6300.3    29.2  6310.3    30.9
#Mann= 4 , 1 , 0
  3399.6      .2       0  3399.6      .1       0  4932.4    .015       0
  5070.1      .1       0
Bank Sta=4932.4,5070.1
XS Rating Curve= 0 ,0
Exp/Cntr=0.5,0.3

Type RM Length L Ch R = 1 ,18031.3 ,58.2,58.2,58.2
BEGIN DESCRIPTION:
Upstream Section of Bridge/Culvert/Weir
END DESCRIPTION:
XS GIS Cut Line= 6
      3163946.72     13808203.12      3164675.45     13808620.06
      3164794.84     13808719.27      3165246.84     13809095.94
      3165914.58     13809122.65       3166961.8     13809175.63
#Sta/Elev= 30
  3346.1   30.78  3666.1   29.18  3786.1   29.88  4066.1   28.48  4330.9   29.18
  4430.9   27.58  4580.9   28.48  4715.9   27.38  4740.9   27.98  4761.7   27.51
  4801.7    27.9  4851.5   26.51  4924.9   27.57  4932.4   27.17  4983.6   10.58
  5014.4    9.75  5032.9   17.15  5060.4   23.93  5070.1   27.02  5121.5   26.94
  5184.9   25.83  5316.2   27.18  5687.4   27.58  5717.4   28.08  5767.4   27.28
  5812.4   28.08  5912.4   28.48  5927.4   29.28  6557.4   29.28  6646.1   30.68
#Mann= 3 ,-1 , 0
  3346.1      .1       0  4932.4    .015       0  5070.1      .1       0
#XS Ineff= 2 , 0
       0  4932.2    27.2  5069.6       0    26.9
Permanent Ineff=
       F       F
Bank Sta=4932.4,5070.1
XS Rating Curve= 0 ,0
Exp/Cntr=0.5,0.3