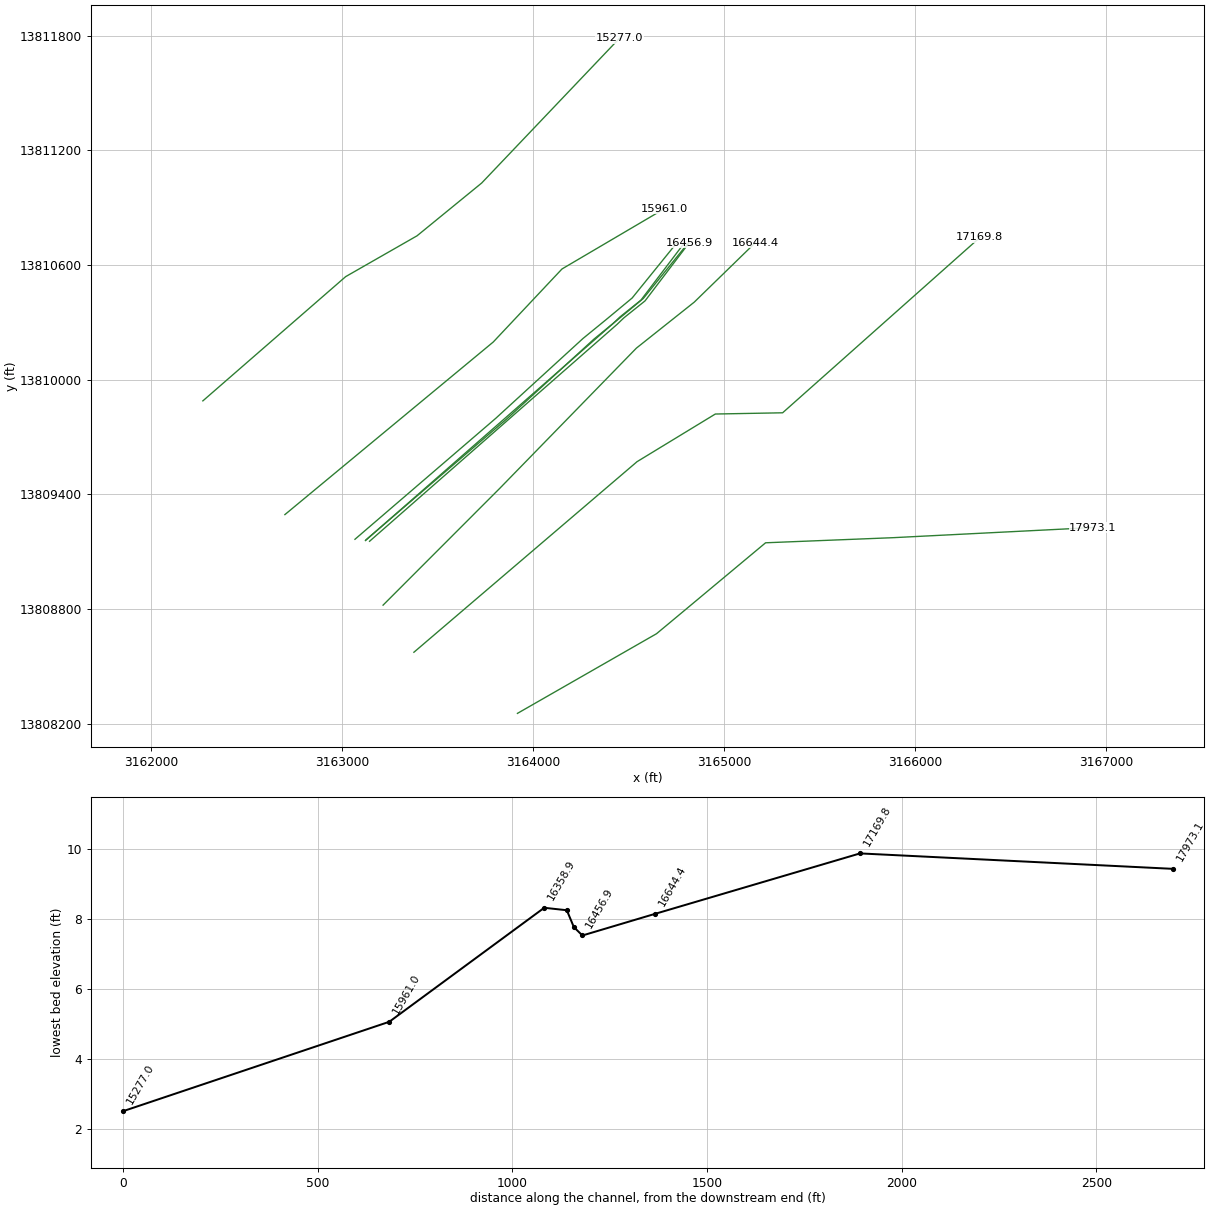
HEC-RAS study C106-00-00.PRJ: C106-00-00 2015

--- C106-00-00.g01 (geometry) --- (continued)

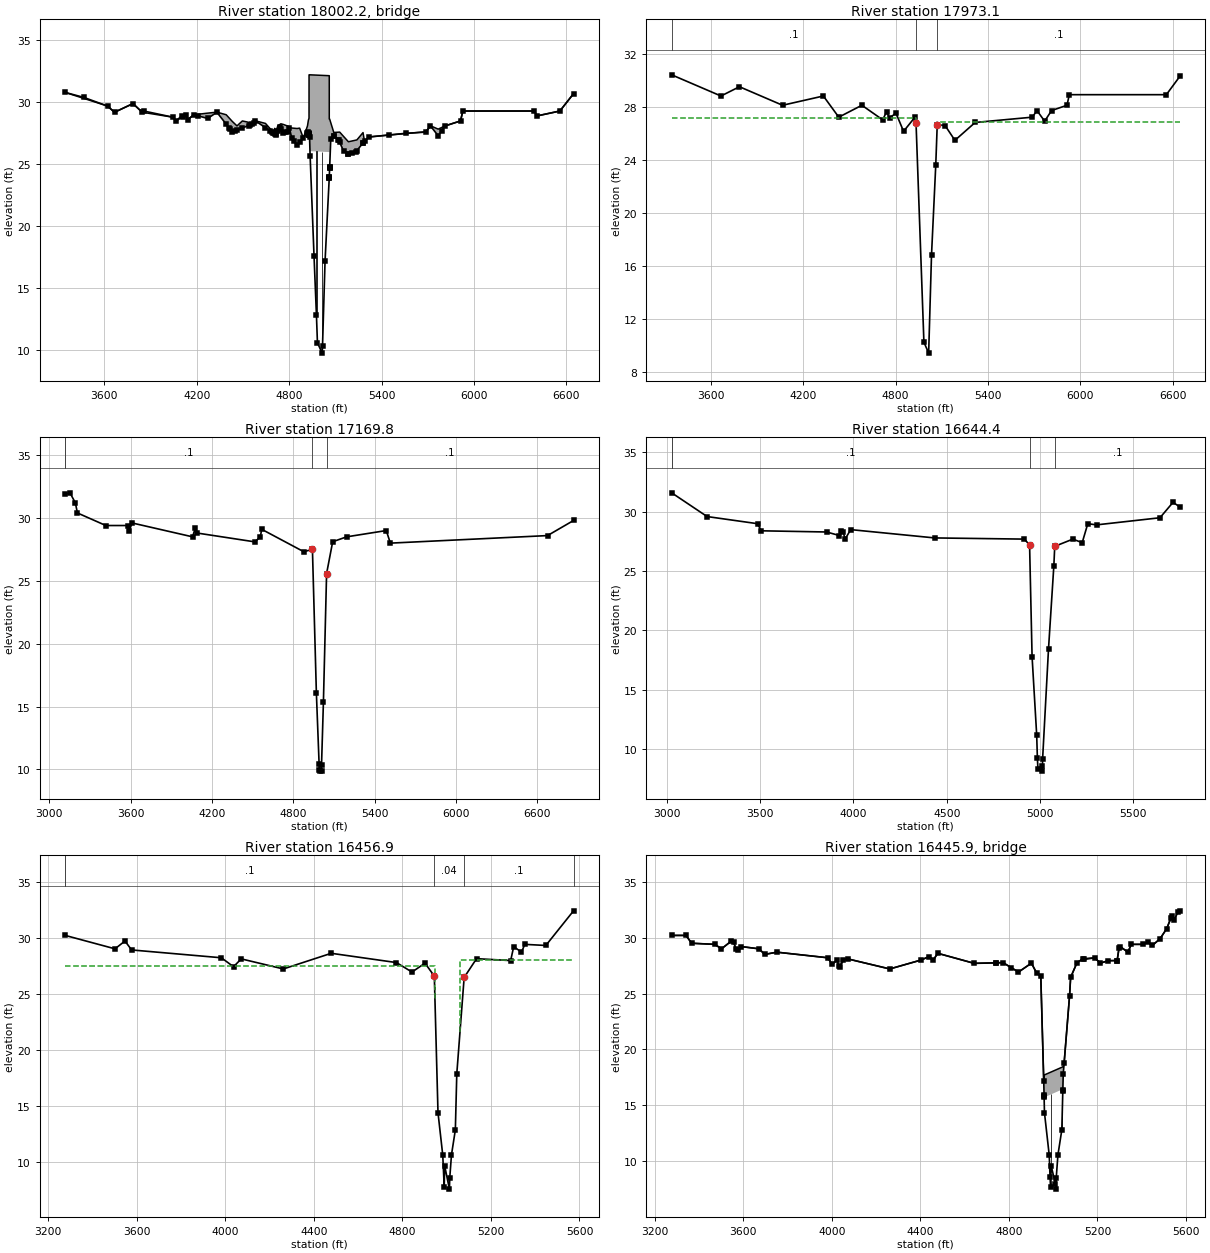
Type RM Length L Ch R = 3 ,18002.2 ,,,
BEGIN DESCRIPTION:
COLLEGE AVENUE
Structure ID: C06-9
END DESCRIPTION:
Node Name=COLLEGE AVENUE
Bridge Culvert--1,0,-1,-1, 0
Deck Dist Width WeirC Skew NumUp NumDn MinLoCord MaxHiCord MaxSubmerge Is_Ogee
10,38.2,2.6,0, 60, 60, , , 0.95, 0, 1,1,,
  3346.1  3621.1  3666.1  3786.1  3846.1  4046.1  4066.1  4131.1  4141.1  4180.9
  4270.9  4330.9  4391.2  4430.9  4461.2  4496.2  4570.9  4580.9  4646.2  4696.2
  4706.2  4715.9  4726.2  4745.8  4761.7  4792.2  4801.7  4816.5  4851.5    4868
    4892  4918.9  4924.9 4928.89  4929.1  4932.4    4936  5060.3  5060.4 5062.79
  5062.9  5070.1  5089.8    5128    5154  5184.7  5239.6  5279.5  5289.2  5316.2
  5687.4  5717.4  5767.4  5812.4  5912.4  5927.4  6392.4  6407.4  6557.4  6646.1
    30.8    29.7    29.2    29.9    29.2    28.8    28.5      29    28.6      29
   29.13   29.21      29   28.46    28.1    28.5    28.3   28.51    28.3    27.6
    27.9   27.71    28.1   28.27   28.22   28.08   28.02   27.93   27.89   27.92
   27.12    28.1   28.57   28.72   32.22   32.22   32.22   32.15   28.65   28.65
   28.65   28.36   27.57    27.6   27.24   26.82   26.97   27.56   26.86   27.21
   27.63   28.11   27.84    28.1    28.5    29.3    29.3    28.9    29.3    30.7
    30.8    29.7    29.2    29.9    29.2    28.8    28.5      29    28.6      29
    28.7    29.2   28.24    27.6   27.75   27.93    28.3    28.5   27.96   27.54
   27.46    27.4   27.65   27.89   27.53   27.61   27.92   27.13   26.53   26.77
   27.11    27.5   27.59   27.38   27.37   27.19   26.06   25.99   25.99   25.99
   24.75   27.04   27.25   26.78   26.05   25.85   26.11   26.72   26.85    27.2
    27.6    28.1    27.3    28.1    28.5    29.3    29.3    28.9    29.3    30.7
  3346.1  3621.1  3666.1  3786.1  3846.1  4046.1  4066.1  4131.1  4141.1  4180.9
  4270.9  4330.9  4391.2  4430.9  4461.2  4496.2  4570.9  4580.9  4646.2  4696.2
  4706.2  4715.9  4726.2  4745.8  4761.7  4792.2  4801.7  4816.5  4851.5    4868
    4892  4918.9  4924.9 4928.89  4929.1  4932.4    4936  5060.3  5060.4 5062.79
  5062.9  5070.1  5089.8    5128    5154  5184.7  5239.6  5279.5  5289.2  5316.2
  5687.4  5717.4  5767.4  5812.4  5912.4  5927.4  6392.4  6407.4  6557.4  6646.1
    30.8    29.7    29.2    29.9    29.2    28.8    28.5      29    28.6      29
   29.13   29.21      29   28.46    28.1    28.5    28.3   28.51    28.3    27.6
    27.9   27.71    28.1   28.27   28.22   28.08   28.02   27.93   27.89   27.92
   27.12    28.1   28.57   28.72   32.22   32.22   32.22   32.15   28.65   28.65
   28.65   28.36   27.57    27.6   27.24   26.82   26.97   27.56   26.86   27.21
   27.63   28.11   27.84    28.1    28.5    29.3    29.3    28.9    29.3    30.7
   30.45   29.35   28.85   29.55   28.85   28.45   28.15   28.65   28.25   28.65
   28.35   28.85   27.89   27.25    27.4   27.58   27.95   28.15   27.61   27.19
   27.11   27.05    27.3   27.54   27.18   27.26   27.57   26.78   26.18   26.42
   26.76   27.15   27.24   27.03   27.02   26.84   25.71   25.64   25.64   25.64
    24.4   26.69    26.9   26.43    25.7    25.5   25.76   26.37    26.5   26.85
   27.25   27.75   26.95   27.75   28.15   28.95   28.95   28.55   28.95   30.35
Pier Skew, UpSta & Num, DnSta & Num=  ,4976.9, 2 ,4976.9, 2 , 0 , 0 , 0 ,,
     1.3     1.3
   11.66   27.03
     1.3     1.3
   11.31   26.68
Pier Skew, UpSta & Num, DnSta & Num=  ,5014.4, 2 ,5014.4, 2 , 0 , 0 , 0 ,,
     1.3     1.3
    8.79   27.01
     1.3     1.3
    8.44   26.66
BR Coef= 1 , 1 , 0 ,1.25, 0 ,,,0.8,0,2,0,
WSPro=,,,, 1 ,,,, 0 ,,,, 0 ,,,,-1 ,-1 ,-1 , 0 , 0 , 0 , 0 , 0
BR U #Sta/Elev= 103
  3346.1    30.8  3466.1    30.4  3621.1    29.7  3666.1    29.2  3786.1    29.9
  3846.1    29.2  3856.1    29.3  4046.1    28.8  4066.1    28.5  4101.1    28.9
  4111.1    28.8  4131.1      29  4141.1    28.6  4180.9      29  4206.2   28.92
  4270.9    28.7  4330.9    29.2  4391.2   28.24  4411.2   27.92  4416.2   27.84
  4430.9    27.6  4451.2    27.7  4461.2   27.75  4496.2   27.93  4536.2   28.13
  4546.2   28.18  4556.2   28.23  4570.9    28.3  4580.9    28.5  4646.2   27.96
  4676.2   27.71  4686.2   27.62  4696.2   27.54  4700.9    27.5  4706.2   27.46
  4715.9    27.4  4716.2   27.41  4726.2   27.65  4740.9      28  4745.8   27.89
  4761.7   27.53  4775.1   27.57  4792.2   27.61  4801.7   27.92  4816.5   27.13
  4829.9    26.9  4851.5   26.53    4868   26.77    4892   27.11  4918.9    27.5
  4924.9   27.59  4926.8   27.49 4926.91   27.48    4927   27.48  4927.1   27.47
 4928.89   27.38  4929.1   27.37 4929.21   27.36  4932.4   27.19    4936    25.7
  4961.3   17.64  4976.9   12.88  4983.6    10.6  5014.4    9.77  5016.5   10.33
  5032.9   17.17 5060.19    23.9  5060.3   23.93  5060.4   23.95 5060.51   23.99
  5062.7   24.68 5062.79   24.71  5062.9   24.75    5063   24.78  5070.1   27.04
  5089.6   27.25  5089.8   27.25  5117.6      27  5121.5   26.96    5128   26.78
    5154   26.05  5184.7   25.85  5184.9   25.85  5210.5   25.95  5233.4   26.02
  5239.6   26.11  5279.5   26.72  5281.9   26.76  5289.2   26.85  5316.2    27.2
  5449.2   27.37  5556.2    27.5  5687.4    27.6  5717.4    28.1  5767.4    27.3
  5789.5   27.69  5812.4    28.1  5912.4    28.5  5927.4    29.3  6392.4    29.3
  6407.4    28.9  6557.4    29.3  6646.1    30.7
BR U #Mann= 3
  3346.1      .1  4932.4    .015  5070.1      .1
BR U Banks=4932.4,5070.1
BR D #Sta/Elev= 103
  3346.1   30.45  3466.1   30.05  3621.1   29.35  3666.1   28.85  3786.1   29.55
  3846.1   28.85  3856.1   28.95  4046.1   28.45  4066.1   28.15  4101.1   28.55
  4111.1   28.45  4131.1   28.65  4141.1   28.25  4180.9   28.65  4206.2   28.57
  4270.9   28.35  4330.9   28.85  4391.2   27.89  4411.2   27.57  4416.2   27.49
  4430.9   27.25  4451.2   27.35  4461.2    27.4  4496.2   27.58  4536.2   27.78
  4546.2   27.83  4556.2   27.88  4570.9   27.95  4580.9   28.15  4646.2   27.61
  4676.2   27.36  4686.2   27.27  4696.2   27.19  4700.9   27.15  4706.2   27.11
  4715.9   27.05  4716.2   27.06  4726.2    27.3  4740.9   27.65  4745.8   27.54
  4761.7   27.18  4775.1   27.22  4792.2   27.26  4801.7   27.57  4816.5   26.78
  4829.9   26.55  4851.5   26.18    4868   26.42    4892   26.76  4918.9   27.15
  4924.9   27.24  4926.8   27.14 4926.91   27.13    4927   27.13  4927.1   27.12
 4928.89   27.03  4929.1   27.02 4929.21   27.01  4932.4   26.84    4936   25.35
  4961.3   17.29  4976.9   12.53  4983.6   10.25  5014.4    9.42  5016.5    9.98
  5032.9   16.82 5060.19   23.55  5060.3   23.58  5060.4    23.6 5060.51   23.64
  5062.7   24.33 5062.79   24.36  5062.9    24.4    5063   24.43  5070.1   26.69
  5089.6    26.9  5089.8    26.9  5117.6   26.65  5121.5   26.61    5128   26.43
    5154    25.7  5184.7    25.5  5184.9    25.5  5210.5    25.6  5233.4   25.67
  5239.6   25.76  5279.5   26.37  5281.9   26.41  5289.2    26.5  5316.2   26.85
  5449.2   27.02  5556.2   27.15  5687.4   27.25  5717.4   27.75  5767.4   26.95
  5789.5   27.34  5812.4   27.75  5912.4   28.15  5927.4   28.95  6392.4   28.95
  6407.4   28.55  6557.4   28.95  6646.1   30.35
BR D #Mann= 3
  3346.1      .1  4932.4    .015  5070.1      .1
BR D Banks=4932.4,5070.1
BC Design=,, 0 ,, 0 ,,,,,,
BC HTab HWMax=30.78
BC Use User HTab Curves=0
BC User HTab FreeFlow(D)= 0

Type RM Length L Ch R = 1 ,17973.1 ,798.1,803.3,810.2
BEGIN DESCRIPTION:
Downstream Section of Bridge/Culvert/Weir
END DESCRIPTION:
XS GIS Cut Line= 6
      3163917.58      13808253.5      3164646.31     13808670.44
       3164765.7     13808769.65       3165217.7     13809146.32
      3165885.44     13809173.03      3166932.66     13809226.01
#Sta/Elev= 30
  3346.1   30.46  3666.1   28.86  3786.1   29.56  4066.1   28.16  4330.9   28.86
  4430.9   27.26  4580.9   28.16  4715.9   27.06  4740.9   27.66  4761.7   27.19
  4801.7   27.58  4851.5   26.19  4924.9   27.25  4932.4   26.85  4983.6   10.26
  5014.4    9.43  5032.9   16.83  5060.4   23.61  5070.1    26.7  5121.5   26.62
  5184.9   25.51  5316.2   26.86  5687.4   27.26  5717.4   27.76  5767.4   26.96
  5812.4   27.76  5912.4   28.16  5927.4   28.96  6557.4   28.96  6646.1   30.36
#Mann= 3 ,-1 , 0
  3346.1      .1       0  4932.4    .015       0  5070.1      .1       0
#XS Ineff= 2 , 0
       0  4932.2    27.2  5069.6       0    26.9
Permanent Ineff=
       F       F
Bank Sta=4932.4,5070.1
XS Rating Curve= 0 ,0
Exp/Cntr=0.5,0.3

Type RM Length L Ch R = 1 ,17169.8 ,525.3,525.4,539
BEGIN DESCRIPTION:
Cross Section 17169.8
END DESCRIPTION:
XS GIS Cut Line= 5
      3163375.11     13808573.48      3164544.31      13809570.9
      3164954.36     13809820.26      3165306.99     13809826.68
      3166340.36     13810744.24
#Sta/Elev= 30
  3117.3    31.9  3152.3      32  3192.3    31.2  3207.3    30.4  3417.3    29.4
  3577.3    29.4  3587.3      29  3612.3    29.6  4057.3    28.5  4077.3    29.2
  4092.3    28.8  4517.3    28.1  4557.3    28.5  4567.3    29.1  4877.4   27.32
  4941.8    27.5    4971   16.05    4991   10.46  4991.2    9.96  4997.3    9.87
  5008.9     9.9    5009   10.38  5022.8   15.34  5046.3   25.58  5091.2   28.11
  5194.1    28.5  5486.8      29  5516.8      28  6676.8    28.6  6868.7    29.8
#Mann= 4 , 1 , 0
  3117.3      .2       0  3117.3      .1       0  4941.8    .035       0
  5046.3      .1       0
Bank Sta=4941.8,5046.3
XS Rating Curve= 0 ,0
Exp/Cntr=0.3,0.1

Type RM Length L Ch R = 1 ,16644.4 ,192,187.5,142.7
BEGIN DESCRIPTION:
Cross Section 16644.4-Interpolated
END DESCRIPTION:
XS GIS Cut Line= 5
      3163213.53     13808820.03       3163828.2     13809434.71
      3164540.87      13810165.2      3164843.76     13810405.72
      3165164.46     13810717.52
#Sta/Elev= 30
  3026.3    31.6  3216.3    29.6  3486.3      29  3506.3    28.4  3856.3    28.3
  3925.6      28  3935.6    28.4  3945.6    28.3  3955.6    27.7  3985.6    28.5
  4435.6    27.8  4916.1    27.7 4944.17   27.21 4957.57   17.79 4982.27   11.19
 4985.97    9.26 4988.87    8.35 5010.57     8.6 5012.37    8.15 5013.97    9.17
 5045.67   18.47 5074.27   25.47 5078.97   27.09  5176.1    27.7  5226.1    27.4
  5256.1      29  5302.9    28.9  5642.9    29.5  5712.9    30.8  5750.2    30.4
#Mann= 4 , 1 , 0
  3026.3      .2       0  3026.3      .1       0 4944.17     .04       0
 5078.97      .1       0
Bank Sta=4944.17,5078.97
XS Rating Curve= 0 ,0
Exp/Cntr=0.5,0.3

Type RM Length L Ch R = 1 ,16456.9 ,22,22,22
BEGIN DESCRIPTION:
Upstream Section of Bridge/Culvert/Weir
END DESCRIPTION:
XS GIS Cut Line= 6
      3163142.74     13809154.24      3164439.46     13810289.42
      3164461.64     13810310.69      3164476.89     13810325.01
      3164586.06     13810412.35      3164817.05     13810716.15
#Sta/Elev= 30
  3276.6   30.23  3501.6   29.03  3546.6   29.73  3576.6   28.93    3982   28.23
    4037   27.43    4072   28.13    4262   27.23  4478.6   28.63 4773.17    27.8
 4843.37   26.95 4901.97   27.75 4944.17   26.59 4960.77   14.37 4982.27   10.57
 4988.87    7.73 4990.87    9.63 5012.37    7.53 5013.97    8.55 5021.67    10.6
 5039.17   12.83 5045.67   17.85 5078.97   26.47 5134.97   28.15 5289.07   27.98
  5302.9   29.23  5337.9   28.73  5352.9   29.43  5447.9   29.33  5573.1   32.43
#Mann= 5 , 1 , 0
  3276.6      .2       0  3276.6      .1       0 4944.17     .04       0
 5078.97      .1       0  5573.1      .2       0
#XS Ineff= 2 , 0
       0    4947    27.5    5060       0      28
Permanent Ineff=
       F       F
Bank Sta=4944.17,5078.97
XS Rating Curve= 0 ,0
Exp/Cntr=0.5,0.3

Type RM Length L Ch R = 3 ,16445.9 ,,,
BEGIN DESCRIPTION:
24" PIPELINE
END DESCRIPTION:
Bridge Culvert--1,0,-1,-1, 0
Deck Dist Width WeirC Skew NumUp NumDn MinLoCord MaxHiCord MaxSubmerge Is_Ogee
10,2,2.6,0, 60, 60, , , 0.95, 0, 1,1,,
  3276.6  3341.6  3366.6  3471.6  3501.6  3546.6  3556.6  3566.6  3576.6  3591.6
  3671.6  3696.6    3752    3982    4002    4022    4032    4037    4052    4072
    4262  4403.6  4438.6  4458.6  4478.6  4643.6 4773.17 4843.37 4901.97 4925.97
 4944.17 4957.57 4959.17 4960.77 5043.66 5043.77 5045.67 5049.57 5074.27 5078.97
 5107.57 5134.97 5189.37 5211.97 5248.87 5289.07  5297.9  5302.9  5337.9  5352.9
  5407.9  5427.9  5447.9  5482.9  5512.9  5532.9  5537.9  5547.9  5562.9  5573.1
    30.2    30.2    29.5    29.4      29    29.7    29.6      29    28.9    29.2
      29    28.5    28.7    28.2    27.6      28    27.5    27.4      28    28.1
    27.2      28    28.3      28    28.6    27.7   27.77   26.92   27.72   26.81
   26.56   17.14    17.7   17.72   18.44   18.44   18.46   18.78   24.82   26.44
   27.75   28.12    28.2   27.71   27.94   27.95    29.1    29.2    28.7    29.4
    29.4    29.6    29.3    29.9    30.8    31.8    31.9    31.6    32.3    32.4
    30.2    30.2    29.5    29.4      29    29.7    29.6      29    28.9    29.2
      29    28.5    28.7    28.2    27.6      28    27.5    27.4      28    28.1
    27.2      28    28.3      28    28.6    27.7   27.77   26.92   27.72   26.81
   26.56   17.14   15.74   15.72   16.44   16.35   17.82   18.77   24.82   26.44
   27.75   28.12    28.2   27.71   27.94   27.95    29.1    29.2    28.7    29.4
    29.4    29.6    29.3    29.9    30.8    31.8    31.9    31.6    32.3    32.4
  3276.6  3341.6  3366.6  3471.6  3501.6  3546.6  3556.6  3566.6  3576.6  3591.6
  3671.6  3696.6    3752    3982    4002    4022    4032    4037    4052    4072
    4262  4403.6  4438.6  4458.6  4478.6  4643.6 4773.17 4843.37 4901.97 4925.97
 4944.17 4957.57 4959.17 4960.77 5043.66 5043.77 5045.67 5049.57 5074.27 5078.97
 5107.57 5134.97 5189.37 5211.97 5248.87 5289.07  5297.9  5302.9  5337.9  5352.9
  5407.9  5427.9  5447.9  5482.9  5512.9  5532.9  5537.9  5547.9  5562.9  5573.1
    30.2    30.2    29.5    29.4      29    29.7    29.6      29    28.9    29.2
      29    28.5    28.7    28.2    27.6      28    27.5    27.4      28    28.1
    27.2      28    28.3      28    28.6    27.7   27.77   26.92   27.72   26.81
   26.56   17.14    17.7   17.72   18.44   18.44   18.46   18.78   24.82   26.44
   27.75   28.12    28.2   27.71   27.94   27.95    29.1    29.2    28.7    29.4
    29.4    29.6    29.3    29.9    30.8    31.8    31.9    31.6    32.3    32.4
    30.2    30.2    29.5    29.4      29    29.7    29.6      29    28.9    29.2
      29    28.5    28.7    28.2    27.6      28    27.5    27.4      28    28.1
    27.2      28    28.3      28    28.6    27.7   27.77   26.92   27.72   26.81
   26.56   17.14   15.74   15.72   16.44   16.35   17.82   18.77   24.82   26.44
   27.75   28.12    28.2   27.71   27.94   27.95    29.1    29.2    28.7    29.4
    29.4    29.6    29.3    29.9    30.8    31.8    31.9    31.6    32.3    32.4
Pier Skew, UpSta & Num, DnSta & Num=  ,4990.9, 2 ,4990.9, 2 , 0 , 0 , 0 ,,
     1.3     1.3
    7.98   16.99
     1.3     1.3
    7.98   16.99
Pier Skew, UpSta & Num, DnSta & Num=  ,5039.2, 2 ,5039.2, 2 , 0 , 0 , 0 ,,
     1.3     1.3
   11.72   17.41
     1.3     1.3
   11.72   17.41
BR Coef= 1 , 1 , 0 ,1.25, 0 ,,,0.8,0,2,0,
WSPro=,,,, 1 ,,,, 0 ,,,, 0 ,,,,-1 ,-1 ,-1 , 0 , 0 , 0 , 0 , 0
BR U #Sta/Elev= 76
  3276.6    30.2  3341.6    30.2  3366.6    29.5  3471.6    29.4  3501.6      29
  3546.6    29.7  3556.6    29.6  3566.6      29  3576.6    28.9  3591.6    29.2
  3671.6      29  3696.6    28.5    3752    28.7    3982    28.2    4002    27.6
    4022      28    4032    27.5    4037    27.4    4052      28    4072    28.1
    4262    27.2  4403.6      28  4438.6    28.3  4458.6      28  4478.6    28.6
  4643.6    27.7 4740.77   27.74 4740.87   27.74 4773.17   27.77 4810.47   27.32
 4843.37   26.92 4901.97   27.72 4925.97   26.81 4944.17   26.56 4957.57   17.14
 4958.97   15.92 4959.08   15.82 4959.17   15.74 4960.77   14.34 4982.27   10.54
 4985.97    8.61 4988.87     7.7 4990.87     9.6 5010.57    7.95 5012.37     7.5
 5013.97    8.52 5021.67   10.57 5039.17    12.8 5043.66   16.27 5043.77   16.35
 5045.67   17.82 5049.57   18.77 5074.27   24.82 5078.97   26.44 5107.57   27.75
 5134.97   28.12 5139.87   28.05 5189.37    28.2 5211.97   27.71 5248.87   27.94
 5288.87   27.95 5289.07   27.95  5297.9    29.1  5302.9    29.2  5337.9    28.7
  5352.9    29.4  5407.9    29.4  5427.9    29.6  5447.9    29.3  5482.9    29.9
  5512.9    30.8  5532.9    31.8  5537.9    31.9  5547.9    31.6  5562.9    32.3
  5573.1    32.4
BR U #Mann= 5
  3276.6      .2  3276.6      .1 4944.17    .035 5078.97      .1  5573.1      .2
BR U Banks=4944.17,5078.97
BR D #Sta/Elev= 76
  3276.6    30.2  3341.6    30.2  3366.6    29.5  3471.6    29.4  3501.6      29
  3546.6    29.7  3556.6    29.6  3566.6      29  3576.6    28.9  3591.6    29.2
  3671.6      29  3696.6    28.5    3752    28.7    3982    28.2    4002    27.6
    4022      28    4032    27.5    4037    27.4    4052      28    4072    28.1
    4262    27.2  4403.6      28  4438.6    28.3  4458.6      28  4478.6    28.6
  4643.6    27.7 4740.77   27.74 4740.87   27.74 4773.17   27.77 4810.47   27.32
 4843.37   26.92 4901.97   27.72 4925.97   26.81 4944.17   26.56 4957.57   17.14
 4958.97   15.92 4959.08   15.82 4959.17   15.74 4960.77   14.34 4982.27   10.54
 4985.97    8.61 4988.87     7.7 4990.87     9.6 5010.57    7.95 5012.37     7.5
 5013.97    8.52 5021.67   10.57 5039.17    12.8 5043.66   16.27 5043.77   16.35
 5045.67   17.82 5049.57   18.77 5074.27   24.82 5078.97   26.44 5107.57   27.75
 5134.97   28.12 5139.87   28.05 5189.37    28.2 5211.97   27.71 5248.87   27.94
 5288.87   27.95 5289.07   27.95  5297.9    29.1  5302.9    29.2  5337.9    28.7
  5352.9    29.4  5407.9    29.4  5427.9    29.6  5447.9    29.3  5482.9    29.9
  5512.9    30.8  5532.9    31.8  5537.9    31.9  5547.9    31.6  5562.9    32.3
  5573.1    32.4
BR D #Mann= 5
  3276.6      .2  3276.6      .1 4944.17    .035 5078.97      .1  5573.1      .2
BR D Banks=4944.17,5078.97
BC Design=,, 0 ,, 0 ,,,,,,
BC HTab HWMax=32.43
BC Use User HTab Curves=0
BC User HTab FreeFlow(D)= 0

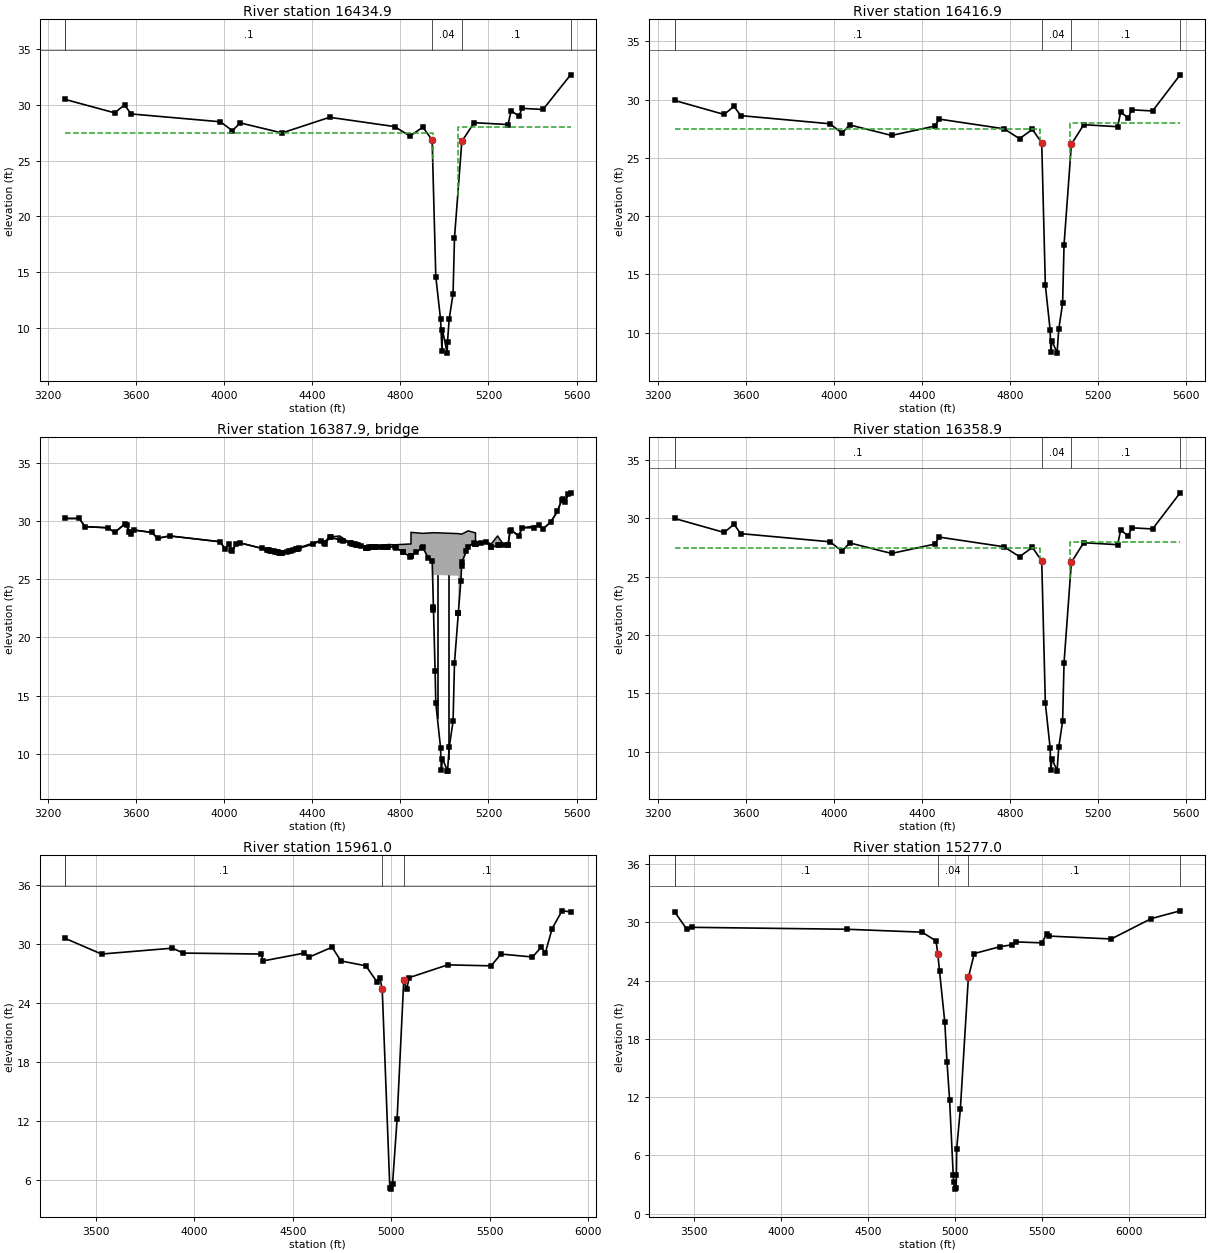
Type RM Length L Ch R = 1 ,16434.9 ,18,18,18
BEGIN DESCRIPTION:
Downstream Section of Bridge/Culvert/Weir
END DESCRIPTION:
XS GIS Cut Line= 6
      3163121.06     13809157.97      3164417.78     13810293.16
      3164439.96     13810314.43      3164455.21     13810328.75
      3164564.38     13810416.09      3164795.37     13810719.88
#Sta/Elev= 30
  3276.6   30.47  3501.6   29.27  3546.6   29.97  3576.6   29.17    3982   28.47
    4037   27.67    4072   28.37    4262   27.47  4478.6   28.87 4773.17   28.04
 4843.37   27.19 4901.97   27.99 4944.17   26.83 4960.77   14.61 4982.27   10.81
 4988.87    7.97 4990.87    9.87 5012.37    7.77 5013.97    8.79 5021.67   10.84
 5039.17   13.07 5045.67   18.09 5078.97   26.71 5134.97   28.39 5289.07   28.22
  5302.9   29.47  5337.9   28.97  5352.9   29.67  5447.9   29.57  5573.1   32.67
#Mann= 5 , 1 , 0
  3276.6      .2       0  3276.6      .1       0 4944.17     .04       0
 5078.97      .1       0  5573.1      .2       0
#XS Ineff= 2 , 0
       0    4947    27.5    5060       0      28
Permanent Ineff=
       F       F
Bank Sta=4944.17,5078.97
XS Rating Curve= 0 ,0
Exp/Cntr=0.5,0.3

Type RM Length L Ch R = 1 ,16416.9 ,58,58,58
BEGIN DESCRIPTION:
Upstream Section of Bridge/Culvert/Weir
END DESCRIPTION:
XS GIS Cut Line= 6
      3163124.04     13809161.84      3163861.59     13809794.77
      3164318.38     13810212.27      3164441.54     13810312.74
      3164576.52     13810424.65      3164810.09     13810712.84
#Sta/Elev= 30
  3276.6   29.93  3501.6   28.73  3546.6   29.43  3576.6   28.63    3982   27.93
    4037   27.13    4072   27.83    4262   26.93  4458.6   27.73  4478.6   28.33
  4773.2    27.5  4843.5   26.65    4902   27.45  4944.3   26.29  4960.8   14.07
  4982.3   10.27    4986    8.34  4990.9    9.33    5014    8.25  5021.7    10.3
  5039.2   12.53  5045.7   17.55    5079   26.17    5135   27.85  5289.1   27.68
  5302.9   28.93  5337.9   28.43  5352.9   29.13  5447.9   29.03  5573.1   32.13
#Mann= 5 , 1 , 0
  3276.6      .2       0  3276.6      .1       0  4944.3     .04       0
    5079      .1       0  5573.1      .2       0
#XS Ineff= 2 , 0
       0  4938.6    27.5  5073.3       0      28
Permanent Ineff=
       F       F
Bank Sta=4944.3,5079
XS Rating Curve= 0 ,0
Exp/Cntr=0.5,0.3

Type RM Length L Ch R = 3 ,16387.9 ,,,
BEGIN DESCRIPTION:
GEORGIA AVENUE, SKEW ANGLE OF 35 DEGREES
Structure ID: C06-8
END DESCRIPTION:
Node Name=GEORGIA AVENUE
Bridge Culvert--1,0,-1,-1, 0
Deck Dist Width WeirC Skew NumUp NumDn MinLoCord MaxHiCord MaxSubmerge Is_Ogee
10,38,2.6,0, 60, 60, , , 0.95, 0, 1,1,,
  3276.6  3341.6  3366.6  3471.6  3501.6  3546.6  3556.6  3576.6  3591.6  3671.6
  3696.6    3752    3982    4002    4022    4037    4052    4072    4262  4438.6
  4458.6  4478.6  4524.2  4569.2  4644.2  4740.9  4742.3  4773.2  4843.5 4847.99
  4848.1    4902    4926  4944.3 4949.89 4949.98 5063.19  5063.3  5074.3    5079
  5107.6  5141.2 5141.31  5189.4  5212.8  5241.4  5268.2  5289.1  5297.9  5302.9
  5337.9  5352.9  5427.9  5447.9  5482.9  5512.9  5532.9  5547.9  5562.9  5573.1
    30.2    30.2    29.5    29.4      29    29.7    29.6    28.9    29.2      29
    28.5    28.7    28.2    27.6      28    27.4      28    28.1   27.21   28.31
   28.26   28.61    28.7   28.12    27.7   27.75   27.97   27.94   28.01   28.01
   29.01   28.92   28.95   28.97   28.98   28.98    28.9    28.9   28.86   28.86
   29.14   28.96   28.06   28.21   28.01    28.7   27.97   27.95    29.1    29.2
    28.7    29.4    29.6    29.3    29.9    30.8    31.8    31.6    32.3    32.4
    30.2    30.2    29.5    29.4      29    29.7    29.6    28.9    29.2      29
    28.5    28.7    28.2    27.6      28    27.4      28    28.1    27.2    28.3
      28    28.6   28.35   28.11    27.7   27.74   27.74   27.77   26.92   26.98
   26.98   27.72   26.81   26.56    22.6   25.36   25.28   22.13   24.82   26.44
   27.75   28.05   28.05    28.2   27.71   27.89   27.94   27.95    29.1    29.2
    28.7    29.4    29.6    29.3    29.9    30.8    31.8    31.6    32.3    32.4
  3276.6  3341.6  3366.6  3471.6  3501.6  3546.6  3556.6  3576.6  3591.6  3671.6
  3696.6    3752    3982    4002    4022    4037    4052    4072    4262  4438.6
  4458.6  4478.6  4524.2  4569.2  4644.2  4740.9  4742.3  4773.2  4843.5 4847.99
  4848.1    4902    4926  4944.3 4949.89 4949.98 5063.19  5063.3  5074.3    5079
  5107.6  5141.2 5141.31  5189.4  5212.8  5241.4  5268.2  5289.1  5297.9  5302.9
  5337.9  5352.9  5427.9  5447.9  5482.9  5512.9  5532.9  5547.9  5562.9  5573.1
    30.2    30.2    29.5    29.4      29    29.7    29.6    28.9    29.2      29
    28.5    28.7    28.2    27.6      28    27.4      28    28.1   27.21   28.31
   28.26   28.61    28.7   28.12    27.7   27.75   27.97   27.94   28.01   28.01
   29.01   28.92   28.95   28.97   28.98   28.98    28.9    28.9   28.86   28.86
   29.14   28.96   28.06   28.21   28.01    28.7   27.97   27.95    29.1    29.2
    28.7    29.4    29.6    29.3    29.9    30.8    31.8    31.6    32.3    32.4
   30.08   30.08   29.38   29.28   28.88   29.58   29.48   28.78   29.08   28.88
   28.38   28.58   28.08   27.48   27.88   27.28   27.88   27.98   27.08   28.18
   27.88   28.48   28.23   27.99   27.58   27.62   27.62   27.65    26.8   26.86
   26.86    27.6   26.69   26.44   22.48   25.24   25.16   22.01    24.7   26.32
   27.63   27.93   27.93   28.08   27.59   27.77   27.82   27.83   28.98   29.08
   28.58   29.28   29.48   29.18   29.78   30.68   31.68   31.48   32.18   32.28
Pier Skew, UpSta & Num, DnSta & Num=  ,4967.9, 2 ,4967.9, 2 , 0 , 0 , 0 ,,
     1.5     1.5
   11.96   26.39
     1.5     1.5
   11.84   26.27
Pier Skew, UpSta & Num, DnSta & Num=  ,5017.8, 2 ,5017.8, 2 , 0 , 0 , 0 ,,
     1.5     1.5
    8.33   26.44
     1.5     1.5
    8.21   26.32
BR Coef= 1 , 1 , 0 ,1.25, 0 ,,,0.8,0,2,0,
WSPro=,,,, 1 ,,,, 0 ,,,, 0 ,,,,-1 ,-1 ,-1 , 0 , 0 , 0 , 0 , 0
BR U #Sta/Elev= 141
  3276.6    30.2  3341.6    30.2  3366.6    29.5  3471.6    29.4  3501.6      29
  3546.6    29.7  3556.6    29.6  3566.6      29  3576.6    28.9  3591.6    29.2
  3671.6      29  3696.6    28.5    3752    28.7    3982    28.2    4002    27.6
    4022      28    4032    27.5    4037    27.4    4052      28    4072    28.1
  4169.2   27.64  4194.2   27.52  4199.2    27.5  4204.2   27.47  4209.2   27.45
  4214.2   27.43  4224.2   27.38  4229.2   27.36  4239.2   27.31  4244.2   27.28
  4249.2   27.26  4254.2   27.24  4259.2   27.21    4262    27.2  4264.2   27.21
  4284.2   27.33  4294.2   27.38  4304.2   27.44  4314.2   27.49  4324.2   27.55
  4329.2   27.58  4334.2   27.61  4339.2   27.64  4403.6      28  4438.6    28.3
  4454.2   28.07  4458.6      28  4478.6    28.6  4484.2   28.57  4524.2   28.35
  4539.2   28.27  4569.2   28.11  4574.2   28.08  4579.2   28.05  4589.2      28
  4594.2   27.97  4599.2   27.94  4604.2   27.91  4609.2   27.89  4619.2   27.83
  4643.6    27.7  4644.2    27.7  4649.2    27.7  4654.2    27.7  4659.2   27.71
  4664.2   27.71  4669.2   27.71  4674.2   27.71  4679.2   27.71  4684.2   27.72
  4689.2   27.72  4709.2   27.73  4719.2   27.73  4729.2   27.74  4734.2   27.74
  4739.2   27.74  4740.8   27.74  4740.9   27.74  4742.3   27.74  4773.2   27.77
  4780.3   27.68  4809.5   27.33  4810.5   27.32  4843.5   26.92 4847.99   26.98
  4848.1   26.98 4848.21   26.98  4871.6    27.3  4898.4   27.67    4902   27.72
    4926   26.81  4944.3   26.56 4949.89    22.6 4949.98   22.54 4950.23   22.36
  4957.6   17.14  4960.8   14.34  4982.3   10.54    4986    8.61  4990.9     9.6
  5013.1    8.56    5014    8.52  5021.7   10.57  5039.2    12.8  5045.7   17.82
 5063.12   22.08 5063.19    22.1  5063.3   22.13  5074.3   24.82  5078.2   26.16
    5079   26.44  5099.2   27.37  5107.6   27.75    5135   28.12  5139.9   28.05
 5141.09   28.05  5141.2   28.05 5141.31   28.05  5164.4   28.12  5189.4    28.2
    5212   27.71  5212.8   27.71  5241.4   27.89  5248.9   27.94  5268.2   27.94
  5288.9   27.95  5289.1   27.95  5297.9    29.1  5302.9    29.2  5337.9    28.7
  5352.9    29.4  5407.9    29.4  5427.9    29.6  5447.9    29.3  5482.9    29.9
  5512.9    30.8  5532.9    31.8  5537.9    31.9  5547.9    31.6  5562.9    32.3
  5573.1    32.4
BR U #Mann= 5
  3276.6      .2  3276.6      .1  4944.3     .04    5079      .1  5573.1      .2
BR U Banks=4944.3,5079
BR D #Sta/Elev= 141
  3276.6   30.08  3341.6   30.08  3366.6   29.38  3471.6   29.28  3501.6   28.88
  3546.6   29.58  3556.6   29.48  3566.6   28.88  3576.6   28.78  3591.6   29.08
  3671.6   28.88  3696.6   28.38    3752   28.58    3982   28.08    4002   27.48
    4022   27.88    4032   27.38    4037   27.28    4052   27.88    4072   27.98
  4169.2   27.52  4194.2    27.4  4199.2   27.38  4204.2   27.35  4209.2   27.33
  4214.2   27.31  4224.2   27.26  4229.2   27.24  4239.2   27.19  4244.2   27.16
  4249.2   27.14  4254.2   27.12  4259.2   27.09    4262   27.08  4264.2   27.09
  4284.2   27.21  4294.2   27.26  4304.2   27.32  4314.2   27.37  4324.2   27.43
  4329.2   27.46  4334.2   27.49  4339.2   27.52  4403.6   27.88  4438.6   28.18
  4454.2   27.95  4458.6   27.88  4478.6   28.48  4484.2   28.45  4524.2   28.23
  4539.2   28.15  4569.2   27.99  4574.2   27.96  4579.2   27.93  4589.2   27.88
  4594.2   27.85  4599.2   27.82  4604.2   27.79  4609.2   27.77  4619.2   27.71
  4643.6   27.58  4644.2   27.58  4649.2   27.58  4654.2   27.58  4659.2   27.59
  4664.2   27.59  4669.2   27.59  4674.2   27.59  4679.2   27.59  4684.2    27.6
  4689.2    27.6  4709.2   27.61  4719.2   27.61  4729.2   27.62  4734.2   27.62
  4739.2   27.62  4740.8   27.62  4740.9   27.62  4742.3   27.62  4773.2   27.65
  4780.3   27.56  4809.5   27.21  4810.5    27.2  4843.5    26.8 4847.99   26.86
  4848.1   26.86 4848.21   26.86  4871.6   27.18  4898.4   27.55    4902    27.6
    4926   26.69  4944.3   26.44 4949.89   22.48 4949.98   22.42 4950.23   22.24
  4957.6   17.02  4960.8   14.22  4982.3   10.42    4986    8.49  4990.9    9.48
  5013.1    8.44    5014     8.4  5021.7   10.45  5039.2   12.68  5045.7    17.7
 5063.12   21.96 5063.19   21.98  5063.3   22.01  5074.3    24.7  5078.2   26.04
    5079   26.32  5099.2   27.25  5107.6   27.63    5135      28  5139.9   27.93
 5141.09   27.93  5141.2   27.93 5141.31   27.93  5164.4      28  5189.4   28.08
    5212   27.59  5212.8   27.59  5241.4   27.77  5248.9   27.82  5268.2   27.82
  5288.9   27.83  5289.1   27.83  5297.9   28.98  5302.9   29.08  5337.9   28.58
  5352.9   29.28  5407.9   29.28  5427.9   29.48  5447.9   29.18  5482.9   29.78
  5512.9   30.68  5532.9   31.68  5537.9   31.78  5547.9   31.48  5562.9   32.18
  5573.1   32.28
BR D #Mann= 5
  3276.6      .2  3276.6      .1  4944.3     .04    5079      .1  5573.1      .2
BR D Banks=4944.3,5079
BC Design=,, 0 ,, 0 ,,,,,,
BC HTab HWMax=32.13
BC Use User HTab Curves=0
BC User HTab FreeFlow(D)= 0

Type RM Length L Ch R = 1 ,16358.9 ,395.5,397.9,402.2
BEGIN DESCRIPTION:
Downstream Section of Bridge/Culvert/Weir
END DESCRIPTION:
XS GIS Cut Line= 6
      3163066.11     13809164.68      3163803.65     13809797.61
      3164260.44     13810215.11       3164383.6     13810315.58
      3164518.58     13810427.49      3164752.15     13810715.68
#Sta/Elev= 30
  3276.6      30  3501.6    28.8  3546.6    29.5  3576.6    28.7    3982      28
    4037    27.2    4072    27.9    4262      27  4458.6    27.8  4478.6    28.4
  4773.2   27.57  4843.5   26.72    4902   27.52  4944.3   26.36  4960.8   14.14
  4982.3   10.34    4986    8.41  4990.9     9.4    5014    8.32  5021.7   10.37
  5039.2    12.6  5045.7   17.62    5079   26.24    5135   27.92  5289.1   27.75
  5302.9      29  5337.9    28.5  5352.9    29.2  5447.9    29.1  5573.1    32.2
#Mann= 5 , 1 , 0
  3276.6      .2       0  3276.6      .1       0  4944.3     .04       0
    5079      .1       0  5573.1      .2       0
#XS Ineff= 2 , 0
       0  4938.6    27.5  5073.3       0      28
Permanent Ineff=
       F       F
Bank Sta=4944.3,5079
XS Rating Curve= 0 ,0
Exp/Cntr=0.5,0.3

Type RM Length L Ch R = 1 ,15961.0 ,693.7,684,654.9
BEGIN DESCRIPTION:
Cross Section 15961.0
END DESCRIPTION:
XS GIS Cut Line= 4
      3162699.08     13809293.84       3163790.7     13810197.06
      3164150.88     13810579.41      3164688.38     13810895.26
#Sta/Elev= 30
  3344.7    30.6  3529.7      29  3889.7    29.6  3944.7    29.1  4339.7      29
  4349.7    28.3  4559.7    29.1  4584.7    28.7  4699.7    29.7  4744.7    28.3
  4871.5    27.8  4926.5    26.2  4942.4    26.6  4954.3   25.41  4992.9     5.2
  4998.8    5.07  5006.8    5.62  5029.9   12.24  5063.6   26.34  5078.5   25.45
  5091.2    26.6  5286.8    27.9  5506.8    27.8  5556.8      29  5716.8    28.7
  5761.8    29.7  5781.8    29.1  5816.8    31.6  5866.8    33.4  5910.3    33.3
#Mann= 4 , 1 , 0
  3344.7      .2       0  3344.7      .1       0  4954.3     .04       0
  5063.6      .1       0
Bank Sta=4954.3,5063.6
XS Rating Curve= 0 ,0
Exp/Cntr=0.3,0.1

Type RM Length L Ch R = 1 ,15277.0 ,233.7,284.2,270.3
BEGIN DESCRIPTION:
Cross Section 15277.0-Interpolated
END DESCRIPTION:
XS GIS Cut Line= 5
      3162269.24     13809889.04      3163017.54     13810539.35
      3163391.69     13810753.15      3163730.21     13811029.31
      3164451.79     13811786.52
#Sta/Elev= 29
  3389.7    31.1  3459.7    29.3  3489.7    29.5  4381.1    29.3    4812      29
    4892    28.1    4902    26.8    4912      25 4942.28   19.75 4955.18   15.59
 4970.08    11.7 4990.78    3.97 4993.28    3.26 5000.78    2.52 5007.88     2.6
 5009.18    3.98 5010.78     6.7 5031.68   10.73 5077.88   24.34    5112    26.8
  5258.9    27.5  5328.9    27.7  5348.9      28  5498.9    27.9  5528.9    28.8
  5538.9    28.6  5898.9    28.3  6128.9    30.4  6294.9    31.2
#Mann= 5 , 1 , 0
  3389.7      .2       0  3389.7      .1       0    4902     .04       0
 5077.88      .1       0  6294.9      .2       0
Bank Sta=4902,5077.88
XS Rating Curve= 0 ,0
Exp/Cntr=0.5,0.3