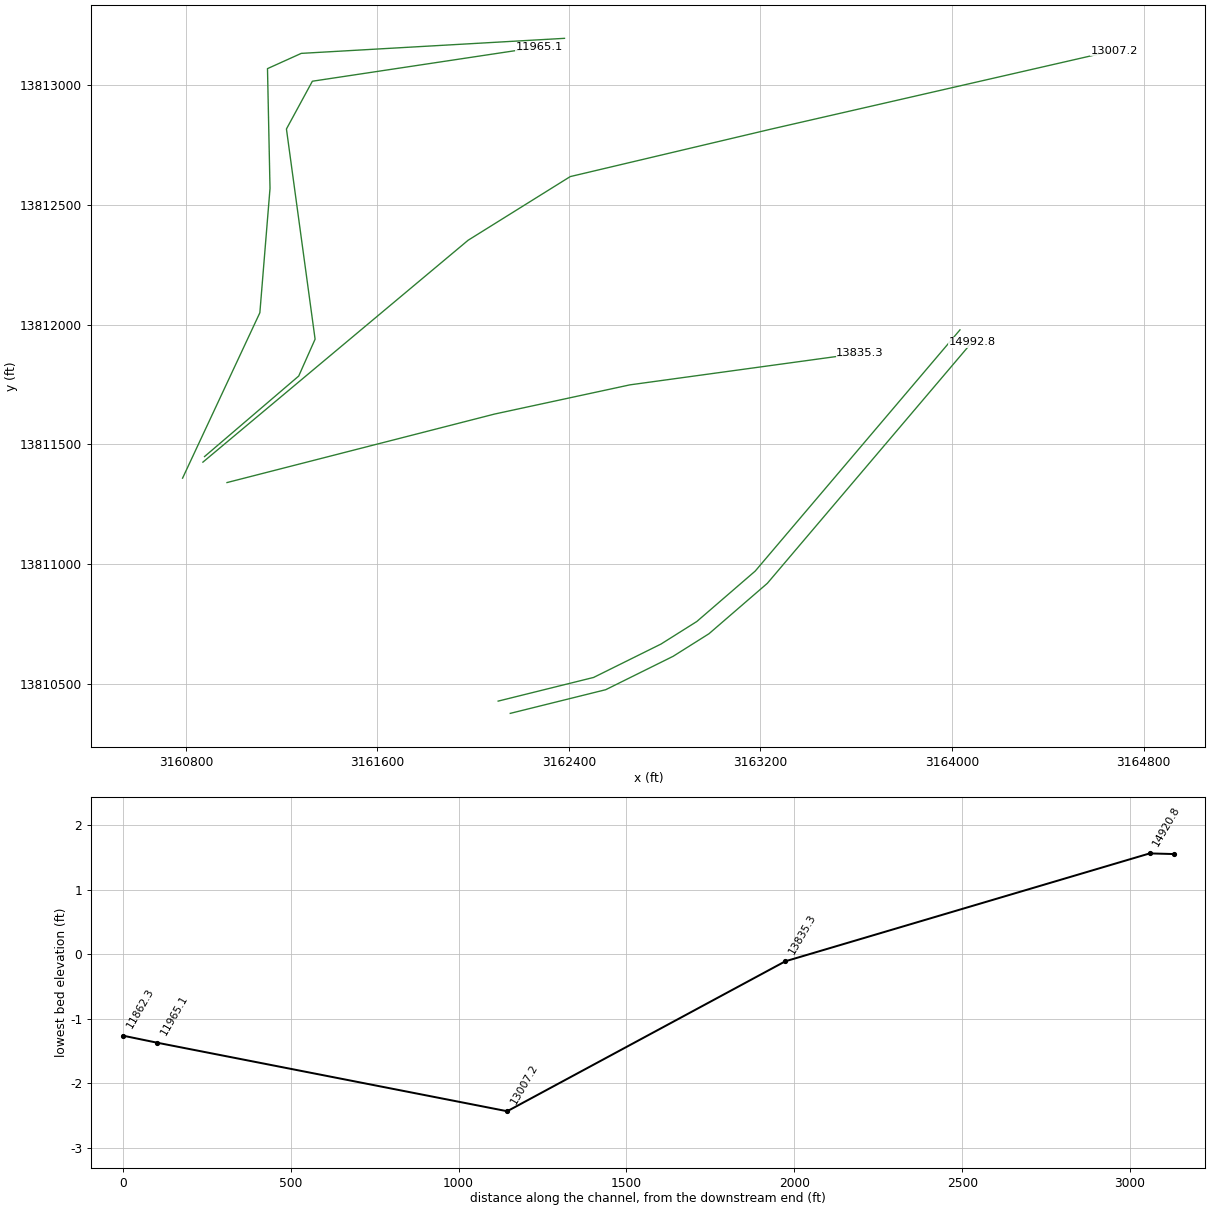
HEC-RAS study C106-00-00.PRJ: C106-00-00 2015

--- C106-00-00.g01 (geometry) --- (continued)

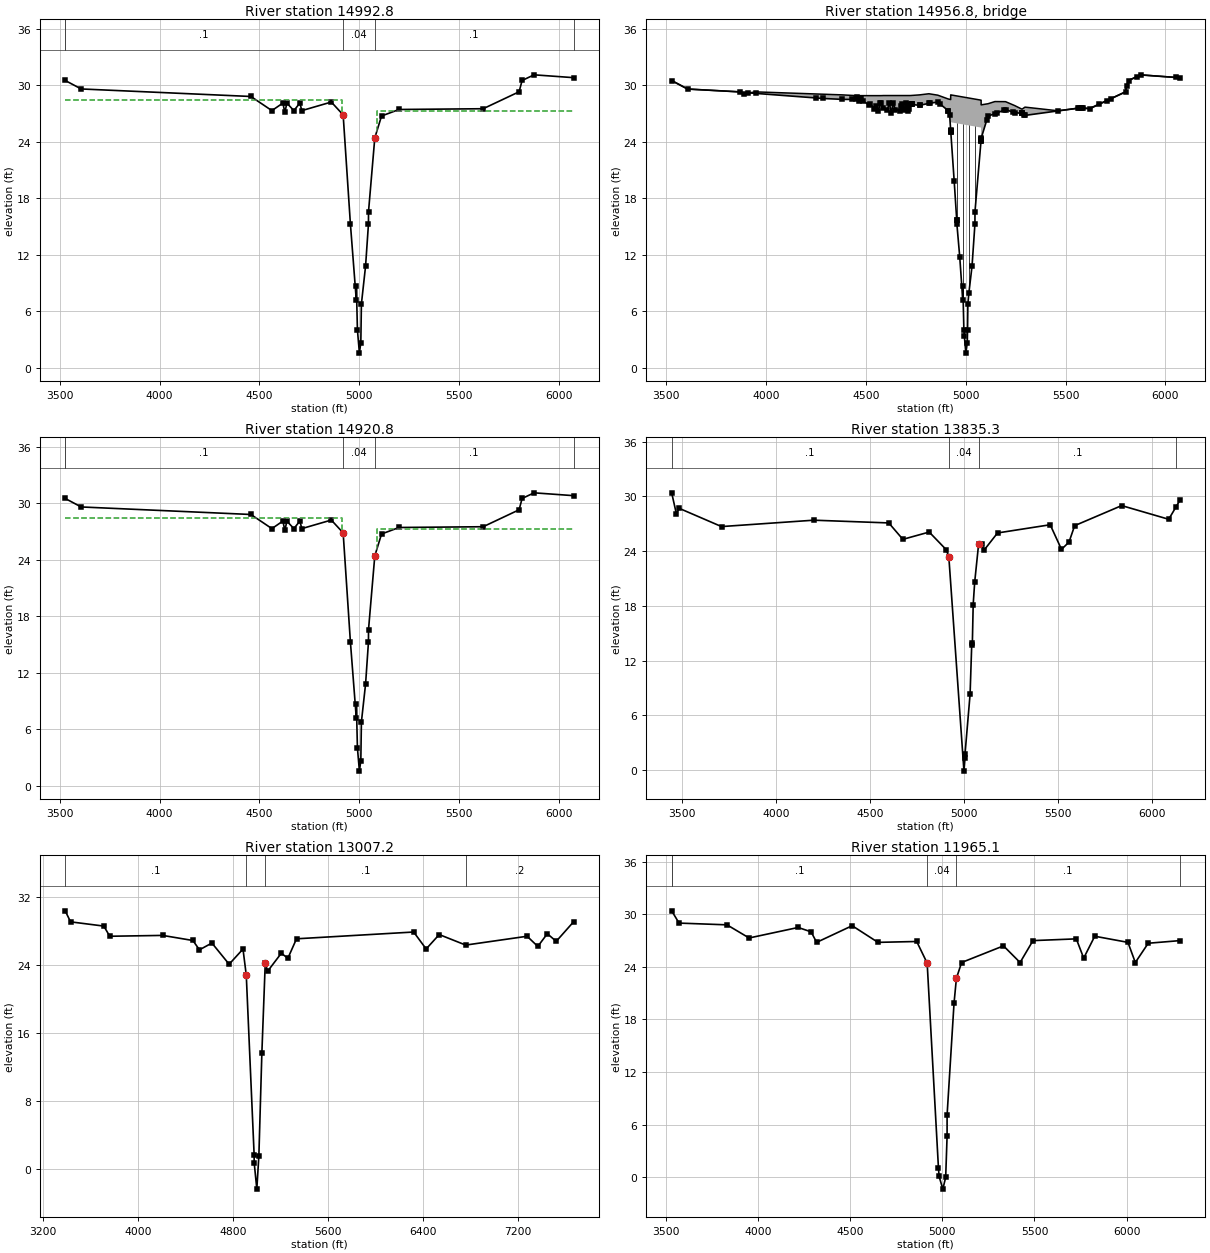
Type RM Length L Ch R = 1 ,14992.8 ,72,72,72
BEGIN DESCRIPTION:
Upstream Section of Bridge/Culvert/Weir
END DESCRIPTION:
XS GIS Cut Line= 6
      3162154.77     13810376.31      3162553.57      13810475.2
       3162835.2     13810614.75      3162984.81     13810708.95
      3163228.63     13810919.52      3164083.88     13811927.05
#Sta/Elev= 30
  3527.4    30.5  3607.4    29.6  4457.5    28.8  4562.5    27.3  4617.5    28.1
  4627.5    27.1  4637.5    28.1  4672.5    27.3  4702.5    28.1  4712.5    27.3
  4860.1   28.21  4919.4   26.85  4955.7   15.28  4985.2    7.19  4985.7    8.65
  4990.8    4.04  5000.8    1.55  5007.9    2.67  5010.8    6.77  5031.7    10.8
  5046.2   15.28  5046.4   16.57  5077.9   24.41  5111.7   26.73  5199.5   27.42
  5620.6    27.5  5800.6    29.3  5815.6    30.5  5875.6    31.1  6073.2    30.8
#Mann= 5 , 1 , 0
  3527.4      .2       0  3527.4      .1       0  4919.4     .04       0
  5077.9      .1       0  6073.2      .2       0
#XS Ineff= 2 , 0
       0  4915.7    28.4  5086.7       0    27.3
Permanent Ineff=
       F       F
Bank Sta=4919.4,5077.9
XS Rating Curve= 0 ,0
Exp/Cntr=0.5,0.3

Type RM Length L Ch R = 3 ,14956.8 ,,,
BEGIN DESCRIPTION:
RICHEY DRIVE
Structure ID: C06-7
END DESCRIPTION:
Node Name=RICHEY DRIVE
Bridge Culvert--1,0,-1,-1, 0
Deck Dist Width WeirC Skew NumUp NumDn MinLoCord MaxHiCord MaxSubmerge Is_Ogee
10,52,2.6,0, 60, 60, , , 0.95, 0, 1,1,,
  3527.4  3607.4  3867.4  3887.4  3947.6  4382.5  4452.5  4457.5  4467.5  4477.5
  4487.5  4517.5  4522.5  4542.5  4552.5  4562.5  4572.5  4577.5  4587.5  4607.5
  4617.5  4627.5  4637.5  4647.5  4672.5  4677.5  4682.5  4687.5  4692.5  4702.5
  4712.5  4717.5  4722.5  4768.8  4815.7  4860.1  4911.7  4919.4 4924.69  4924.8
 4925.11  4925.2 5076.79  5076.9  5077.2 5077.31  5111.7  5146.2  5199.5  5245.7
  5281.9  5296.9  5462.6  5575.6  5620.6  5800.6  5805.6  5815.6  5875.6  6073.2
    30.5    29.6    29.3    29.1    29.3   28.98    28.9    28.9    28.9    28.9
    28.9    28.9    28.9    28.9    28.9    28.9    28.9    28.9   28.91   28.91
   28.91   28.91   28.91   28.91   28.91   28.91   28.91   28.91   28.91   28.91
   28.91   28.91   28.91   28.98    29.1   28.95   28.55   28.51   28.48   28.98
   28.98   28.98   28.42   28.42   28.42   27.92   28.04   28.27   28.26   27.84
   27.46   27.68   27.29   27.61   27.54   29.31   29.91   30.51   31.11    30.8
    30.5    29.6    29.3    29.1   29.14    28.5    28.5    28.8    28.3    28.7
    28.3    27.9      28    27.5    27.8    27.3    28.1    28.1    27.6    27.4
    28.1    27.1    28.1    27.4    27.3    27.8      28    27.5    27.4    28.1
    27.3    27.5      28   27.87   28.08   28.21   27.31   26.85   25.23   25.19
    25.1   26.07   25.51   24.16   24.24   24.26   26.73   26.98   27.42   27.07
   27.02    26.8   27.28    27.6    27.5    29.3    29.9    30.5    31.1    30.8
  3527.4  3607.4  3867.4  3887.4  3947.6  4382.5  4452.5  4457.5  4467.5  4477.5
  4487.5  4517.5  4522.5  4542.5  4552.5  4562.5  4572.5  4577.5  4587.5  4607.5
  4617.5  4627.5  4637.5  4647.5  4672.5  4677.5  4682.5  4687.5  4692.5  4702.5
  4712.5  4717.5  4722.5  4768.8  4815.7  4860.1  4911.7  4919.4 4924.69  4924.8
 4925.11  4925.2 5076.79  5076.9  5077.2 5077.31  5111.7  5146.2  5199.5  5245.7
  5281.9  5296.9  5462.6  5575.6  5620.6  5800.6  5805.6  5815.6  5875.6  6073.2
   30.53   29.63   29.33   29.13    29.3   28.98    28.9    28.9    28.9    28.9
    28.9    28.9    28.9    28.9    28.9    28.9    28.9    28.9   28.91   28.91
   28.91   28.91   28.91   28.91   28.91   28.91   28.91   28.91   28.91   28.91
   28.91   28.91   28.91   28.98    29.1   28.95   28.55   28.51   28.48   28.98
   28.98   28.98   28.42   28.42   28.42   27.92   28.04   28.27   28.26   27.84
   27.46   27.68   27.31   27.63   27.54   29.33   29.93   30.53   31.13   30.83
   30.53   29.63   29.33   29.13   29.17   28.53   28.53   28.83   28.33   28.73
   28.33   27.93   28.03   27.53   27.83   27.33   28.13   28.13   27.63   27.43
   28.13   27.13   28.13   27.43   27.33   27.83   28.03   27.53   27.43   28.13
   27.33   27.53   28.03    27.9   28.11   28.24   27.34   26.88   25.26   25.22
   25.13    26.1   25.54   24.19   24.27   24.29   26.76   27.01   27.45    27.1
   27.05   26.83   27.31   27.63   27.53   29.33   29.93   30.53   31.13   30.83
Pier Skew, UpSta & Num, DnSta & Num=  ,4955.1, 2 ,4955.1, 2 , 0 , 0 , 0 ,,
     1.2     1.2
   14.28   26.96
     1.2     1.2
   14.31   26.99
Pier Skew, UpSta & Num, DnSta & Num=  ,4985.7, 2 ,4985.7, 2 , 0 , 0 , 0 ,,
     1.2     1.2
    6.22   26.85
     1.2     1.2
    6.25   26.88
Pier Skew, UpSta & Num, DnSta & Num=  ,5015.9, 2 ,5015.9, 2 , 0 , 0 , 0 ,,
     1.2     1.2
     6.8   26.73
     1.2     1.2
    6.83   26.76
Pier Skew, UpSta & Num, DnSta & Num=  ,5046.4, 2 ,5046.4, 2 , 0 , 0 , 0 ,,
     1.2     1.2
   14.16   26.62
     1.2     1.2
   14.19   26.65
BR Coef= 1 , 1 , 0 ,1.25, 0 ,,,0.8,0,2,0,
WSPro=,,,, 1 ,,,, 0 ,,,, 0 ,,,,-1 ,-1 ,-1 , 0 , 0 , 0 , 0 , 0
BR U #Sta/Elev= 112
  3527.4    30.5  3607.4    29.6  3867.4    29.3  3887.4    29.1  3911.5    29.2
  3947.6   29.14  4252.6   28.65  4286.5    28.6  4382.5    28.5  4429.4    28.5
  4452.5    28.5  4457.5    28.8  4467.5    28.3  4477.5    28.7  4487.5    28.3
  4517.5    27.9  4522.5      28  4542.5    27.5  4552.5    27.8  4562.5    27.3
  4572.5    28.1  4577.5    28.1  4587.5    27.6  4607.5    27.4  4617.5    28.1
  4627.5    27.1  4637.5    28.1  4647.5    27.4  4672.5    27.3  4677.5    27.8
  4682.5      28  4687.5    27.5  4692.5    27.4  4702.5    28.1  4707.5    27.6
  4712.5    27.3  4717.5    27.5  4722.5      28  4729.7   27.96  4729.8   27.96
  4729.9   27.96  4768.8   27.87  4771.2   27.88  4815.7   28.08  4819.4    28.1
  4860.1   28.21  4869.4   28.05  4911.7   27.31  4912.1   27.29  4919.4   26.85
 4924.69   25.23  4924.8   25.19 4924.91   25.16    4925   25.13 4925.11    25.1
  4925.2   25.07  4925.3   25.04  4942.3   19.82  4955.1   15.66  4955.2   15.66
  4955.7   15.28  4970.1   11.77  4985.2    7.19  4985.7    8.65  4990.8    4.04
  4993.3    3.33  5000.8    1.55  5007.9    2.67  5009.2    4.05  5010.8    6.77
  5015.9    7.94  5031.7    10.8  5046.2   15.28  5046.4   16.57  5076.7   24.11
 5076.79   24.13  5076.9   24.16 5076.99   24.18  5077.1   24.21  5077.2   24.24
 5077.31   24.26  5077.9   24.41  5106.3   26.36  5111.7   26.73  5146.2   26.98
  5157.9   27.07  5193.3   27.37  5199.5   27.42    5237   27.14  5245.7   27.07
  5280.6   27.04  5280.7   27.04  5281.9   27.02  5291.5   26.88  5296.9    26.8
  5462.6   27.28  5562.6   27.56  5567.6   27.58  5575.6    27.6  5582.6   27.58
  5587.6   27.57  5620.6    27.5  5667.6   27.97  5707.6   28.37  5727.6   28.57
  5800.6    29.3  5805.6    29.9  5815.6    30.5  5857.6   30.92  5875.6    31.1
  6052.8   30.83  6073.2    30.8
BR U #Mann= 5
  3527.4      .2  3527.4      .1  4919.4     .04  5077.9      .1  6073.2      .2
BR U Banks=4919.4,5077.9
BR D #Sta/Elev= 112
  3527.4   30.53  3607.4   29.63  3867.4   29.33  3887.4   29.13  3911.5   29.23
  3947.6   29.17  4252.6   28.68  4286.5   28.63  4382.5   28.53  4429.4   28.53
  4452.5   28.53  4457.5   28.83  4467.5   28.33  4477.5   28.73  4487.5   28.33
  4517.5   27.93  4522.5   28.03  4542.5   27.53  4552.5   27.83  4562.5   27.33
  4572.5   28.13  4577.5   28.13  4587.5   27.63  4607.5   27.43  4617.5   28.13
  4627.5   27.13  4637.5   28.13  4647.5   27.43  4672.5   27.33  4677.5   27.83
  4682.5   28.03  4687.5   27.53  4692.5   27.43  4702.5   28.13  4707.5   27.63
  4712.5   27.33  4717.5   27.53  4722.5   28.03  4729.7   27.99  4729.8   27.99
  4729.9   27.99  4768.8    27.9  4771.2   27.91  4815.7   28.11  4819.4   28.13
  4860.1   28.24  4869.4   28.08  4911.7   27.34  4912.1   27.32  4919.4   26.88
 4924.69   25.26  4924.8   25.22 4924.91   25.19    4925   25.16 4925.11   25.13
  4925.2    25.1  4925.3   25.07  4942.3   19.85  4955.1   15.69  4955.2   15.69
  4955.7   15.31  4970.1    11.8  4985.2    7.22  4985.7    8.68  4990.8    4.07
  4993.3    3.36  5000.8    1.58  5007.9     2.7  5009.2    4.08  5010.8     6.8
  5015.9    7.97  5031.7   10.83  5046.2   15.31  5046.4    16.6  5076.7   24.14
 5076.79   24.16  5076.9   24.19 5076.99   24.21  5077.1   24.24  5077.2   24.27
 5077.31   24.29  5077.9   24.44  5106.3   26.39  5111.7   26.76  5146.2   27.01
  5157.9    27.1  5193.3    27.4  5199.5   27.45    5237   27.17  5245.7    27.1
  5280.6   27.07  5280.7   27.07  5281.9   27.05  5291.5   26.91  5296.9   26.83
  5462.6   27.31  5562.6   27.59  5567.6   27.61  5575.6   27.63  5582.6   27.61
  5587.6    27.6  5620.6   27.53  5667.6      28  5707.6    28.4  5727.6    28.6
  5800.6   29.33  5805.6   29.93  5815.6   30.53  5857.6   30.95  5875.6   31.13
  6052.8   30.86  6073.2   30.83
BR D #Mann= 5
  3527.4      .2  3527.4      .1  4919.4     .04  5077.9      .1  6073.2      .2
BR D Banks=4919.4,5077.9
BC Design=,, 0 ,, 0 ,,,,,,
BC HTab HWMax=31.1
BC Use User HTab Curves=0
BC User HTab FreeFlow(D)= 0

Type RM Length L Ch R = 1 ,14920.8 ,1095.9,1085.5,1070.5
BEGIN DESCRIPTION:
Downstream Section of Bridge/Culvert/Weir
END DESCRIPTION:
XS GIS Cut Line= 6
      3162104.18     13810427.54      3162502.97     13810526.42
       3162784.6     13810665.97      3162934.21     13810760.17
      3163178.03     13810970.74      3164033.29     13811978.28
#Sta/Elev= 30
  3527.4   30.51  3607.4   29.61  4457.5   28.81  4562.5   27.31  4617.5   28.11
  4627.5   27.11  4637.5   28.11  4672.5   27.31  4702.5   28.11  4712.5   27.31
  4860.1   28.22  4919.4   26.86  4955.7   15.29  4985.2     7.2  4985.7    8.66
  4990.8    4.05  5000.8    1.56  5007.9    2.68  5010.8    6.78  5031.7   10.81
  5046.2   15.29  5046.4   16.58  5077.9   24.42  5111.7   26.74  5199.5   27.43
  5620.6   27.51  5800.6   29.31  5815.6   30.51  5875.6   31.11  6073.2   30.81
#Mann= 5 , 1 , 0
  3527.4      .2       0  3527.4      .1       0  4919.4     .04       0
  5077.9      .1       0  6073.2      .2       0
#XS Ineff= 2 , 0
       0  4915.7    28.4  5086.7       0    27.3
Permanent Ineff=
       F       F
Bank Sta=4919.4,5077.9
XS Rating Curve= 0 ,0
Exp/Cntr=0.5,0.3

Type RM Length L Ch R = 1 ,13835.3 ,808.5,828.1,860.2
BEGIN DESCRIPTION:
Cross Section 13835.3
END DESCRIPTION:
XS GIS Cut Line= 4
      3160971.61     13811340.47      3162089.54      13811626.7
      3162654.75     13811748.61      3163615.74     13811880.51
#Sta/Elev= 30
  3446.5    30.4  3471.5    28.1  3486.5    28.7  3711.5    26.7  4201.5    27.4
  4600.5    27.1  4675.5    25.3  4815.5    26.1  4905.8   24.17  4919.7   23.41
  5000.2    -.11  5005.9    1.35    5006     1.8  5032.8    8.31  5041.4   13.68
  5044.9   13.93  5049.3   18.15  5057.2   20.59  5078.3   24.81  5093.8   24.84
  5106.6    24.1  5178.7      26  5458.7    26.9  5518.7    24.2  5558.7      25
  5588.7    26.8  5838.7      29  6088.7    27.5  6128.2   28.88  6148.7    29.6
#Mann= 4 , 1 , 0
  3446.5      .1       0  4919.7     .04       0  5078.3      .1       0
  6128.2      .2       0
Bank Sta=4919.7,5078.3
XS Rating Curve= 0 ,0
Exp/Cntr=0.3,0.1

Type RM Length L Ch R = 1 ,13007.2 ,859.9,1042.1,1217.3
BEGIN DESCRIPTION:
Cross Section 13007.2
END DESCRIPTION:
XS GIS Cut Line= 5
      3160870.91     13811425.77      3161978.72      13812352.6
      3162405.39     13812618.58      3163243.74     13812816.74
       3164677.3       13813145.
#Sta/Elev= 30
  3389.6    30.4  3434.6    29.1  3714.6    28.6  3764.6    27.4  4209.6    27.5
  4464.6    26.9  4519.6    25.8  4624.6    26.6  4769.6    24.1  4886.3   25.89
  4913.9   22.81  4980.1    1.59  4980.3     .71  5002.7   -2.43    5020    1.53
  5045.1   13.61  5073.8    24.3  5092.9   23.26    5209    25.4    5264    24.8
  5336.8    27.1  6323.2    27.9  6428.2    25.9  6538.2    27.6  6761.2   26.36
  7278.2    27.4  7368.2    26.2  7448.2    27.7  7523.2    26.8  7668.9    29.1
#Mann= 4 , 1 , 0
  3389.6      .1       0  4913.9    .035       0  5073.8      .1       0
  6761.2      .2       0
Bank Sta=4913.9,5073.8
XS Rating Curve= 0 ,0
Exp/Cntr=0.3,0.1

Type RM Length L Ch R = 1 ,11965.1 ,105.8,102.8,100.5
BEGIN DESCRIPTION:
Cross Section 11965.1-Interpolated
END DESCRIPTION:
XS GIS Cut Line= 6
      3160877.75     13811449.07      3161271.15     13811785.45
      3161339.56     13811939.39      3161219.84      13812817.4
      3161328.16     13813016.94      3162274.59     13813159.48
#Sta/Elev= 30
  3532.5    30.4  3572.5      29  3832.5    28.8  3952.5    27.3  4218.6    28.5
  4288.6      28  4318.6    26.8  4511.3    28.7  4651.3    26.8  4861.3    26.9
    4918   24.43  4979.3    1.01  4982.8     .08    5003   -1.37  5018.4    -.02
    5026    4.66  5026.1     7.1  5063.7   19.86  5076.6    22.7  5104.8    24.5
  5331.9    26.4  5421.9    24.5  5491.9      27  5726.8    27.2  5766.8      25
  5826.8    27.5  6006.8    26.8  6046.8    24.5  6116.8    26.7  6289.1      27
#Mann= 5 , 1 , 0
  3532.5      .2       0  3532.5      .1       0    4918     .04       0
  5076.6      .1       0  6289.1      .2       0
Bank Sta=4918,5076.6
XS Rating Curve= 0 ,0
Exp/Cntr=0.5,0.3

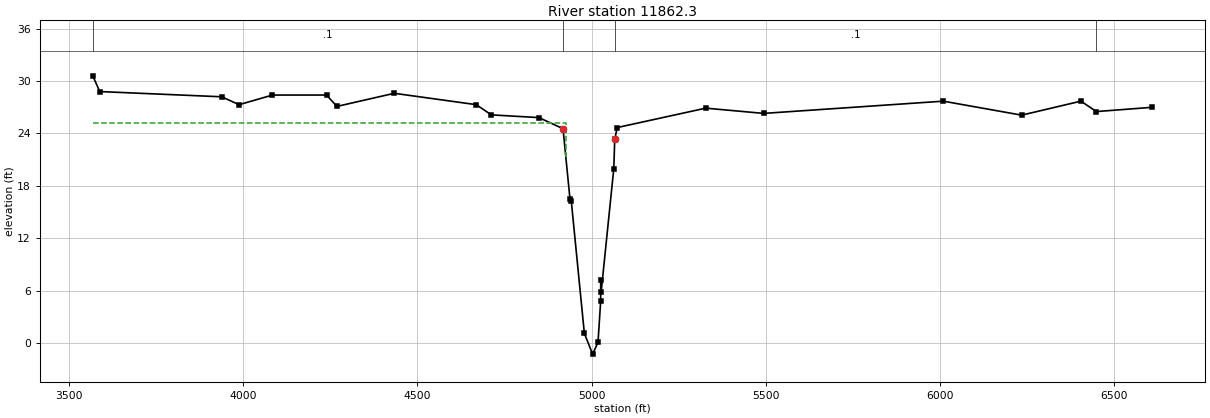
Type RM Length L Ch R = 1 ,11862.3 ,73,73,73
BEGIN DESCRIPTION:
Upstream Section of Bridge/Culvert/Weir
END DESCRIPTION:
XS GIS Cut Line= 6
      3160785.97     13811358.85      3161108.83     13812049.88
      3161151.23     13812568.92      3161140.69     13813069.53
       3161281.8     13813133.26      3162381.25     13813196.08
#Sta/Elev= 30
  3568.4   30.59  3588.4   28.79  3938.4   28.19  3988.4   27.29  4084.2   28.39
  4239.2   28.39  4269.2   27.09  4433.7   28.59  4668.9   27.29  4712.5   26.12
  4848.8   25.81    4918   24.54  4937.9   16.52  4941.7   16.27  4979.2    1.12
    5003   -1.26  5018.4     .09    5026    4.77  5026.1    7.21  5027.5    5.86
  5063.7   19.97  5066.4   23.32  5073.5   24.67  5327.6   26.89    5494   26.29
  6009.3   27.69  6234.3   26.09  6404.3   27.69  6448.9    26.5  6609.6   26.99
#Mann= 4 , 1 , 0
  3568.4      .1       0    4918     .04       0  5066.4      .1       0
  6448.9      .2       0
#XS Ineff= 2 , 0
       0  4925.9    25.2  5073.7       0    24.2
Permanent Ineff=
       F       F
Bank Sta=4918,5066.4
XS Rating Curve= 0 ,0
Exp/Cntr=0.5,0.3