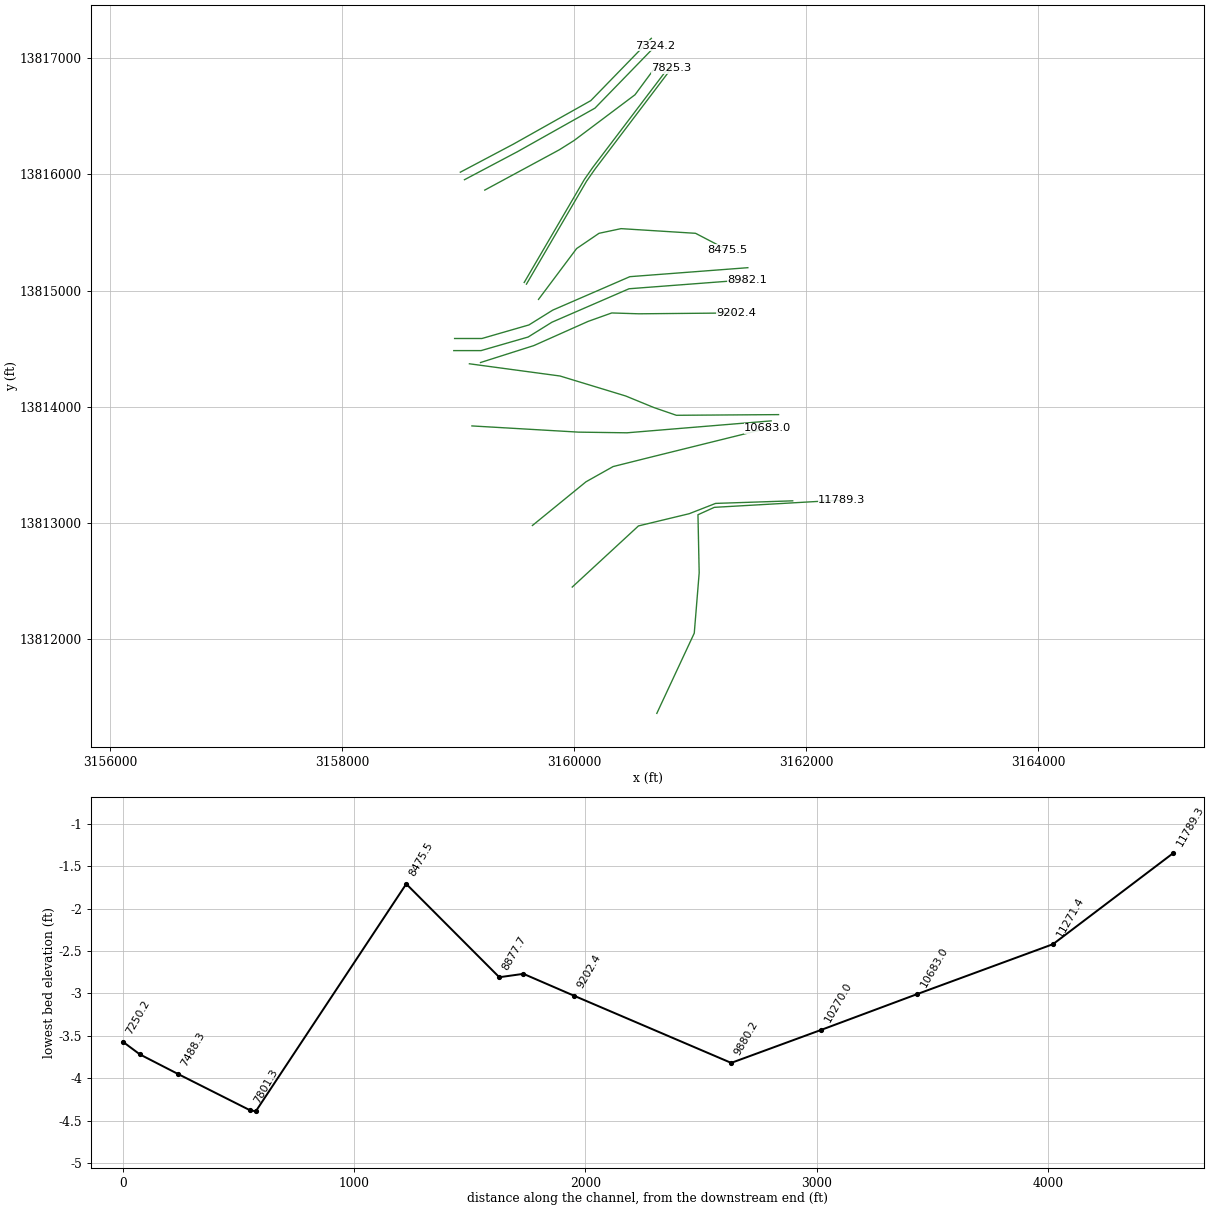
HEC-RAS study C106-00-00.PRJ: C106-00-00 2015

--- C106-00-00.g01 (geometry) --- (continued)

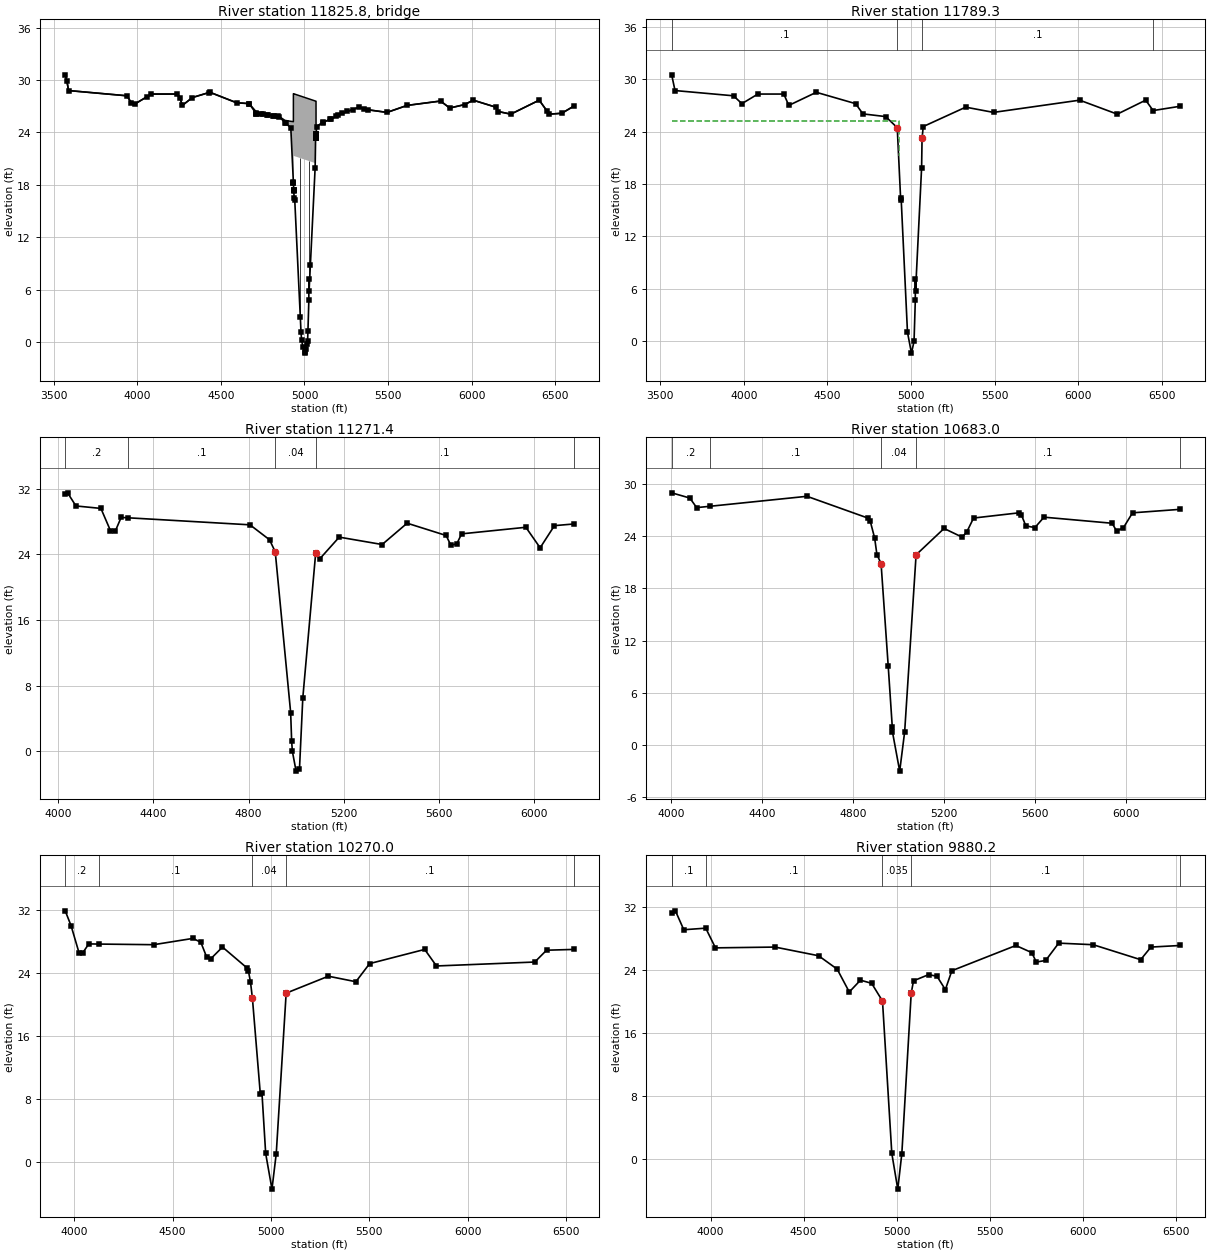
Type RM Length L Ch R = 3 ,11825.8 ,,,
BEGIN DESCRIPTION:
FOREST OAKS BLVD
Structure ID: C06-6
END DESCRIPTION:
Node Name=FOREST OAKS BLVD
Bridge Culvert--1,0,-1,-1, 0
Deck Dist Width WeirC Skew NumUp NumDn MinLoCord MaxHiCord MaxSubmerge Is_Ogee
10,53,2.6,0, 47, 47, , , 0.95, 0, 1,1,,
  3568.4  3578.4  3588.4  3938.4  3963.4  3988.4  4084.2  4239.2  4254.2  4269.2
  4329.2  4433.7  4593.7  4668.9    4709  4712.5  4776.4  4848.8  4882.9    4918
 4933.49  4933.6 4935.71  4935.8  5063.7  5066.4    5069 5069.11  5073.5  5110.8
    5161    5200  5327.6    5379    5494    5614    5814    5869    5959  6009.3
  6144.3  6159.3  6234.3  6404.3  6464.3  6539.3  6609.6
    30.6    29.9    28.8    28.2    27.4    27.3    28.4    28.4      28    27.1
      28   28.61   27.41   27.31   26.42    26.4   26.04   25.83   25.39   25.28
   25.24   28.44   28.43   28.43   27.61   27.59   27.58   24.38   24.69   25.18
   25.56   25.99   26.91    26.6    26.3    27.1    27.6    26.8    27.2    27.7
    26.9    26.4    26.1    27.7    26.1    26.2      27
    30.6    29.9    28.8    28.2    27.4    27.3    28.4    28.4      28    27.1
      28    28.6    27.4    27.3   26.22   26.13   26.03   25.82   25.13   24.55
   18.31   18.26   17.41   21.32    20.5   23.33   23.82   23.85   24.68   25.17
   25.55   25.98    26.9    26.6    26.3    27.1    27.6    26.8    27.2    27.7
    26.9    26.4    26.1    27.7    26.1    26.2      27
  3568.4  3578.4  3588.4  3938.4  3963.4  3988.4  4084.2  4239.2  4254.2  4269.2
  4329.2  4433.7  4593.7  4668.9    4709  4712.5  4776.4  4848.8  4882.9    4918
 4933.49  4933.6 4935.71  4935.8  5063.7  5066.4    5069 5069.11  5073.5  5110.8
    5161    5200  5327.6    5379    5494    5614    5814    5869    5959  6009.3
  6144.3  6159.3  6234.3  6404.3  6464.3  6539.3  6609.6
    30.6    29.9    28.8    28.2    27.4    27.3    28.4    28.4      28    27.1
      28   28.61   27.41   27.31   26.42    26.4   26.04   25.83   25.39   25.28
   25.24   28.44   28.43   28.43   27.61   27.59   27.58   24.38   24.69   25.18
   25.56   25.99   26.91    26.6    26.3    27.1    27.6    26.8    27.2    27.7
    26.9    26.4    26.1    27.7    26.1    26.2      27
   30.52   29.82   28.72   28.12   27.32   27.22   28.32   28.32   27.92   27.02
   27.92   28.52   27.32   27.22   26.14   26.05   25.95   25.74   25.05   24.47
   18.23   18.18   17.33   21.24   20.42   23.25   23.74   23.77    24.6   25.09
   25.47    25.9   26.82   26.52   26.22   27.02   27.52   26.72   27.12   27.62
   26.82   26.32   26.02   27.62   26.02   26.12   26.92
Pier Skew, UpSta & Num, DnSta & Num=  ,4975, 2 ,4975, 2 , 0 , 0 , 0 ,,
       2       2
    1.45    22.1
       2       2
    1.37   22.02
Pier Skew, UpSta & Num, DnSta & Num=  ,5027.5, 2 ,5027.5, 2 , 0 , 0 , 0 ,,
       2       2
    5.26   21.76
       2       2
    5.18   21.68
BR Coef= 1 , 1 , 0 ,1.25, 0 ,,,0.8,0,2,0,
WSPro=,,,, 1 ,,,, 0 ,,,, 0 ,,,,-1 ,-1 ,-1 , 0 , 0 , 0 , 0 , 0
BR U #Sta/Elev= 90
  3568.4    30.6  3578.4    29.9  3588.4    28.8  3938.4    28.2  3963.4    27.4
  3988.4    27.3  4058.4    28.1  4084.2    28.4  4239.2    28.4  4254.2      28
  4269.2    27.1  4329.2      28  4429.3   28.57  4433.7    28.6  4593.7    27.4
  4668.7    27.3  4668.9    27.3    4709   26.22  4712.5   26.13  4712.6   26.13
  4740.7   26.12    4752   26.09  4776.4   26.03    4780   26.02  4808.6   25.94
  4814.7   25.92  4842.3   25.84  4848.8   25.82  4882.9   25.13  4888.1   25.04
    4918   24.55 4933.49   18.31  4933.6   18.26 4933.71   18.22  4935.6   17.46
 4935.71   17.41  4935.8   17.38  4935.9   17.34  4937.9   16.53  4941.7   16.28
    4975    2.86  4979.2    1.13  4982.8      .2  4991.3    -.57    5001   -1.13
    5003   -1.25  5009.6    -.75  5013.8     -.2  5018.4      .1  5020.7    1.31
    5026    4.78  5026.1    7.22  5027.5    5.87  5035.3    8.88  5063.7   19.98
  5066.4   23.33  5066.5   23.35 5066.59   23.37  5066.7   23.39  5066.8   23.41
 5068.89    23.8    5069   23.82 5069.11   23.85  5073.5   24.68  5108.5   25.14
  5110.8   25.17  5154.2    25.5    5161   25.55    5190   25.87    5200   25.98
  5226.7   26.18    5257   26.41  5287.9   26.62  5327.6    26.9  5357.5   26.73
    5379    26.6    5494    26.3    5614    27.1    5814    27.6    5869    26.8
    5959    27.2  6009.3    27.7  6144.3    26.9  6159.3    26.4  6234.3    26.1
  6404.3    27.7  6448.9   26.51  6464.3    26.1  6539.3    26.2  6609.6      27
BR U #Mann= 4
  3568.4      .1    4918     .04  5066.4      .1  6448.9      .2
BR U Banks=4918,5066.4
BR D #Sta/Elev= 90
  3568.4   30.52  3578.4   29.82  3588.4   28.72  3938.4   28.12  3963.4   27.32
  3988.4   27.22  4058.4   28.02  4084.2   28.32  4239.2   28.32  4254.2   27.92
  4269.2   27.02  4329.2   27.92  4429.3   28.49  4433.7   28.52  4593.7   27.32
  4668.7   27.22  4668.9   27.22    4709   26.14  4712.5   26.05  4712.6   26.05
  4740.7   26.04    4752   26.01  4776.4   25.95    4780   25.94  4808.6   25.86
  4814.7   25.84  4842.3   25.76  4848.8   25.74  4882.9   25.05  4888.1   24.96
    4918   24.47 4933.49   18.23  4933.6   18.18 4933.71   18.14  4935.6   17.38
 4935.71   17.33  4935.8    17.3  4935.9   17.26  4937.9   16.45  4941.7    16.2
    4975    2.78  4979.2    1.05  4982.8     .12  4991.3    -.65    5001   -1.21
    5003   -1.33  5009.6    -.83  5013.8    -.28  5018.4     .02  5020.7    1.23
    5026     4.7  5026.1    7.14  5027.5    5.79  5035.3     8.8  5063.7    19.9
  5066.4   23.25  5066.5   23.27 5066.59   23.29  5066.7   23.31  5066.8   23.33
 5068.89   23.72    5069   23.74 5069.11   23.77  5073.5    24.6  5108.5   25.06
  5110.8   25.09  5154.2   25.42    5161   25.47    5190   25.79    5200    25.9
  5226.7    26.1    5257   26.33  5287.9   26.54  5327.6   26.82  5357.5   26.65
    5379   26.52    5494   26.22    5614   27.02    5814   27.52    5869   26.72
    5959   27.12  6009.3   27.62  6144.3   26.82  6159.3   26.32  6234.3   26.02
  6404.3   27.62  6448.9   26.43  6464.3   26.02  6539.3   26.12  6609.6   26.92
BR D #Mann= 4
  3568.4      .1    4918     .04  5066.4      .1  6448.9      .2
BR D Banks=4918,5066.4
BC Design=,, 0 ,, 0 ,,,,,,
BC HTab HWMax=30.59
BC Use User HTab Curves=0
BC User HTab FreeFlow(D)= 0

Type RM Length L Ch R = 1 ,11789.3 ,616.5,517.9,352.2
BEGIN DESCRIPTION:
Downstream Section of Bridge/Culvert/Weir
END DESCRIPTION:
XS GIS Cut Line= 6
      3160712.97     13811358.85      3161035.83     13812049.88
      3161078.23     13812568.92      3161067.69     13813069.53
       3161208.8     13813133.26      3162308.25     13813196.08
#Sta/Elev= 30
  3568.4    30.5  3588.4    28.7  3938.4    28.1  3988.4    27.2  4084.2    28.3
  4239.2    28.3  4269.2      27  4433.7    28.5  4668.9    27.2  4712.5   26.03
  4848.8   25.72    4918   24.45  4937.9   16.43  4941.7   16.18  4979.2    1.03
    5003   -1.35  5018.4       0    5026    4.68  5026.1    7.12  5027.5    5.77
  5063.7   19.88  5066.4   23.23  5073.5   24.58  5327.6    26.8    5494    26.2
  6009.3    27.6  6234.3      26  6404.3    27.6  6448.9   26.41  6609.6    26.9
#Mann= 4 , 1 , 0
  3568.4      .1       0    4918     .04       0  5066.4      .1       0
  6448.9      .2       0
#XS Ineff= 2 , 0
       0  4925.9    25.2  5073.7       0    24.2
Permanent Ineff=
       F       F
Bank Sta=4918,5066.4
XS Rating Curve= 0 ,0
Exp/Cntr=0.5,0.3

Type RM Length L Ch R = 1 ,11271.4 ,588.3,588.4,616
BEGIN DESCRIPTION:
Cross Section 11271.4
END DESCRIPTION:
XS GIS Cut Line= 5
      3159983.87      13812446.8      3160554.62     13812973.22
      3160992.38      13813078.5      3161219.57     13813167.16
      3161884.51     13813189.33
#Sta/Elev= 30
  4029.1    31.3  4039.1    31.5  4074.1    29.9  4179.1    29.6  4219.1    26.9
  4239.1    26.8  4264.1    28.5  4291.1   28.46  4805.5    27.6  4887.6   25.78
  4911.6   24.31  4976.4    4.72  4980.5    1.28  4983.5     .01  4999.2   -2.42
  5013.5   -2.15  5027.5    6.53  5081.5   24.14    5098   23.43  5180.5    26.1
  5360.8    25.2  5465.8    27.8  5629.7    26.3  5649.7    25.1  5674.7    25.3
  5694.7    26.5  5964.7    27.3  6024.7    24.8  6084.7    27.5    6165    27.7
#Mann= 5 , 1 , 0
  4029.1      .2       0  4291.1      .1       0  4911.6     .04       0
  5081.5      .1       0    6165      .2       0
Bank Sta=4911.6,5081.5
XS Rating Curve= 0 ,0
Exp/Cntr=0.3,0.1

Type RM Length L Ch R = 1 ,10683.0 ,475.4,413,381.3
BEGIN DESCRIPTION:
Cross Section 10683.0-Interpolated
END DESCRIPTION:
XS GIS Cut Line= 5
      3159640.56     13812977.03      3160102.37     13813353.32
      3160336.13     13813484.45       3160632.6     13813558.57
      3161670.24     13813815.13
#Sta/Elev= 30
  4001.2      29  4081.2    28.4  4111.2    27.3  4168.8   27.45  4596.9    28.6
  4864.9    26.1  4874.9    25.8  4894.9    23.8  4904.9    21.9  4923.2   20.86
  4954.5    9.13  4972.4    2.12  4973.2    1.52  5005.2   -3.01    5027     1.5
  5077.4   21.87  5200.5    24.9  5280.5    23.9  5300.5    24.5  5330.5    26.1
  5530.5    26.7  5540.5    26.5  5560.5    25.2  5600.5      25  5640.5    26.2
  5940.5    25.5  5960.5    24.6  5990.5      25  6030.5    26.7  6239.4    27.1
#Mann= 5 , 1 , 0
  4001.2      .2       0  4168.8      .1       0  4923.2     .04       0
  5077.4      .1       0  6239.4      .2       0
Bank Sta=4923.2,5077.4
XS Rating Curve= 0 ,0
Exp/Cntr=0.3,0.1

Type RM Length L Ch R = 1 ,10270.0 ,420.6,389.8,346.7
BEGIN DESCRIPTION:
Cross Section 10270.0-Interpolated
END DESCRIPTION:
XS GIS Cut Line= 4
       3159118.9     13813834.46      3160039.66     13813780.92
      3160455.85     13813775.22      3161698.75     13813877.85
#Sta/Elev= 30
  3953.5    31.9  3983.5      30  4023.5    26.6  4043.5    26.6  4073.5    27.7
  4125.7   27.68  4403.5    27.6  4603.5    28.4  4643.5    27.9  4673.5      26
  4693.5    25.8  4753.5    27.3  4875.8    24.7  4885.8    24.2  4895.8    22.9
  4905.8    20.8  4945.8     8.7  4954.5    8.71  4973.2     1.1  5005.2   -3.43
    5027    1.08  5077.4   21.45    5292    23.6    5432    22.9    5502    25.2
    5782      27    5842    24.9    6342    25.4    6402    26.9  6539.2      27
#Mann= 5 , 1 , 0
  3953.5      .2       0  4125.7      .1       0  4905.8     .04       0
  5077.4      .1       0  6539.2      .2       0
Bank Sta=4905.8,5077.4
XS Rating Curve= 0 ,0
Exp/Cntr=0.3,0.1

Type RM Length L Ch R = 1 ,9880.2  ,643.8,677.8,709.8
BEGIN DESCRIPTION:
Cross Section 9880.2
END DESCRIPTION:
XS GIS Cut Line= 6
      3159097.27     13814369.61      3159878.59     13814264.33
      3160443.79     13814092.55      3160687.61     13813992.81
      3160881.47     13813926.07      3161762.61     13813931.85
#Sta/Elev= 30
  3791.5    31.2  3811.5    31.5  3856.5    29.1  3974.4    29.3  4026.5    26.8
  4346.5    26.9  4579.9    25.8  4679.9    24.1  4744.9    21.2  4804.9    22.7
  4864.9    22.3  4923.2   20.05  4973.2     .71  5005.2   -3.82    5027     .69
  5077.4   21.06  5089.7   22.62  5170.6    23.4  5215.6    23.2  5260.6    21.5
  5295.6    23.9  5639.1    27.1  5724.1    26.2  5749.1      25  5799.1    25.2
  5869.1    27.4  6054.1    27.2  6309.1    25.3  6364.1    26.9  6520.2    27.1
#Mann= 6 , 1 , 0
  3791.5      .2       0  3791.5      .1       0  3974.4      .1       0
  4923.2    .035       0  5077.4      .1       0  6520.2      .2       0
Bank Sta=4923.2,5077.4
XS Rating Curve= 0 ,0
Exp/Cntr=0.3,0.1

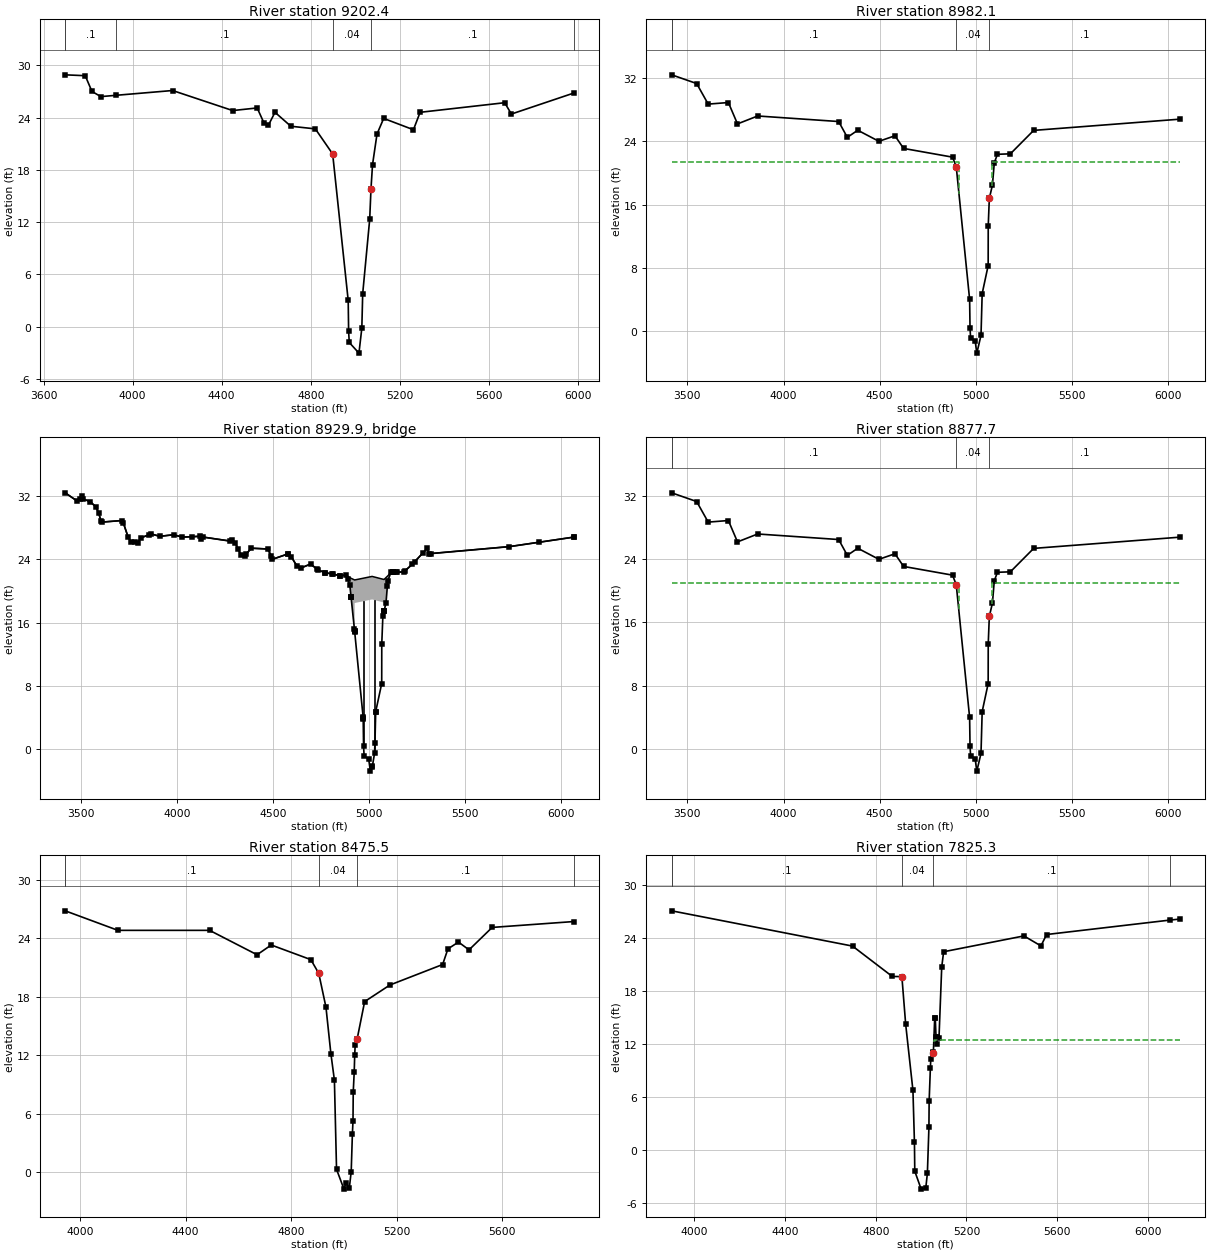
Type RM Length L Ch R = 1 ,9202.4  ,111.7,220.3,208.7
BEGIN DESCRIPTION:
Cross Section 9202.4
END DESCRIPTION:
XS GIS Cut Line= 6
      3159193.12     13814380.48      3159652.88     13814526.43
      3160119.93     13814734.42      3160324.27      13814807.4
      3160557.79      13814800.1      3161397.03      13814807.4
#Sta/Elev= 30
  3697.2    28.9  3787.2    28.8  3817.2      27  3857.2    26.4  3925.1   26.55
  4179.6    27.1  4449.6    24.8  4559.6    25.1  4589.6    23.4  4609.6    23.1
  4639.6    24.6  4710.8      23  4820.8    22.7 4898.67   19.82 4968.47    3.01
 4970.37    -.54 4973.27   -1.81 5016.77   -3.03 5029.67    -.16 5033.57    3.79
 5065.07   12.33 5070.77   15.82  5077.8    18.6  5097.8    22.1  5127.8    23.9
  5261.5    22.6  5291.5    24.6  5671.5    25.7  5701.5    24.4  5980.7    26.8
#Mann= 6 , 1 , 0
  3697.2      .2       0  3697.2      .1       0  3925.1      .1       0
 4898.67     .04       0 5070.77      .1       0  5980.7      .2       0
Bank Sta=4898.67,5070.77
XS Rating Curve= 0 ,0
Exp/Cntr=0.5,0.3

Type RM Length L Ch R = 1 ,8982.1  ,104.4,104.4,104.4
BEGIN DESCRIPTION:
Upstream Section of Bridge/Culvert/Weir
END DESCRIPTION:
XS GIS Cut Line= 6
      3158962.46      13814483.2      3159197.92      13814483.2
      3159603.54     13814600.14      3159808.56     13814727.58
      3160473.51     13815015.73      3161490.66     13815093.08
#Sta/Elev= 30
  3418.2   32.39  3548.2   31.29  3608.2   28.69  3713.2   28.89  3760.6   26.19
  3865.6   27.19    4287   26.49    4332   24.49  4386.3   25.39  4496.3   23.99
  4579.8   24.69  4624.8   23.09  4879.4   21.99  4898.7   20.78  4968.3    4.01
  4970.4     .42  4973.3    -.85  4997.1   -1.24  5005.7   -2.77  5027.5    -.53
  5033.6    4.75  5064.8     8.3  5065.1   13.29  5070.8   16.78    5087   18.46
  5096.6   21.27  5112.9   22.35  5180.4   22.41  5301.5   25.37  6062.8   26.79
#Mann= 4 , 1 , 0
  3418.2      .2       0  3418.2      .1       0  4898.7     .04       0
  5070.8      .1       0
#XS Ineff= 2 , 0
       0    4913    21.4    5086       0    21.4
Permanent Ineff=
       F       F
Bank Sta=4898.7,5070.8
XS Rating Curve= 0 ,0
Exp/Cntr=0.5,0.3

Type RM Length L Ch R = 3 ,8929.9  ,,,
BEGIN DESCRIPTION:
ALLENDALE ROAD
Structure ID: C06-5
END DESCRIPTION:
Node Name=ALLENDALE ROAD
Bridge Culvert--1,0,-1,-1, 0
Deck Dist Width WeirC Skew NumUp NumDn MinLoCord MaxHiCord MaxSubmerge Is_Ogee
10,84.4,2.6,0, 60, 60, , , 0.95, 0, 1,1,,
  3418.2  3478.2  3493.2  3503.2  3513.2  3548.2  3578.2  3593.2  3603.2  3608.2
  3713.2  3720.6  3745.6  3760.6  3795.6  3810.6  3865.6  3910.6    3982    4027
    4117    4127    4137    4277    4287    4302    4332    4352  4361.3  4386.3
  4471.3  4491.3  4496.3  4579.8  4594.8  4624.8  4644.8  4694.8  4733.4  4769.9
  4847.9  4879.4  4898.7  4923.9 4924.01  4924.1  5014.9 5076.79  5076.9    5087
  5096.6  5112.9 5124.49  5139.8  5180.4  5223.5  5301.5  5309.2  5729.2  6062.8
    32.4    31.4    31.6      32    31.6    31.3    30.6    29.8    28.9    28.7
    28.9    28.6    26.8    26.2   26.11   26.71   27.21   26.91   27.11   26.81
   26.91   26.61   26.81   26.31   26.51   26.11   24.64   24.55   24.71   25.41
   25.31   24.41   24.01   24.71   24.31   23.11   22.91   23.41   22.67   22.32
   21.94   22.01   21.68   21.39   21.39   21.39   21.84   21.45   21.45   21.69
   21.91   22.37   22.45   22.35   22.43   23.37   25.39   24.71   25.61    26.8
    32.4    31.4    31.6      32    31.6    31.3    30.6    29.8    28.9    28.7
    28.9    28.6    26.8    26.2    26.1    26.7    27.2    26.9    27.1    26.8
    26.9    26.6    26.8    26.3    26.5    26.1    24.5    24.4    24.7    25.4
    25.3    24.4      24    24.7    24.3    23.1    22.9    23.4   22.66   22.31
   21.93      22   20.79   14.92   14.89   18.48   18.93   18.54   17.42   18.47
   21.28   22.36   22.35   22.34   22.42   23.36   25.38    24.7    25.6    26.8
  3418.2  3478.2  3493.2  3503.2  3513.2  3548.2  3578.2  3593.2  3603.2  3608.2
  3713.2  3720.6  3745.6  3760.6  3795.6  3810.6  3865.6  3910.6    3982    4027
    4117    4127    4137    4277    4287    4302    4332    4352  4361.3  4386.3
  4471.3  4491.3  4496.3  4579.8  4594.8  4624.8  4644.8  4694.8  4733.4  4769.9
  4847.9  4879.4  4898.7  4923.9 4924.01  4924.1  5014.9 5076.79  5076.9    5087
  5096.6  5112.9 5124.49  5139.8  5180.4  5223.5  5301.5  5309.2  5729.2  6062.8
    32.4    31.4    31.6      32    31.6    31.3    30.6    29.8    28.9    28.7
    28.9    28.6    26.8    26.2   26.11   26.71   27.21   26.91   27.11   26.81
   26.91   26.61   26.81   26.31   26.51   26.11   24.64   24.55   24.71   25.41
   25.31   24.41   24.01   24.71   24.31   23.11   22.91   23.41   22.67   22.32
   21.94   22.01   21.68   21.39   21.39   21.39   21.84   21.45   21.45   21.69
   21.91   22.37   22.45   22.35   22.43   23.37   25.39   24.71   25.61    26.8
   32.32   31.32   31.52   31.92   31.52   31.22   30.52   29.72   28.82   28.62
   28.82   28.52   26.72   26.12   26.02   26.62   27.12   26.82   27.02   26.72
   26.82   26.52   26.72   26.22   26.42   26.02   24.42   24.32   24.62   25.32
   25.22   24.32   23.92   24.62   24.22   23.02   22.82   23.32   22.58   22.23
   21.85   21.92   20.71   14.84   14.81    18.4   18.85   18.46   17.34   18.39
    21.2   22.28   22.27   22.26   22.34   23.28    25.3   24.62   25.52   26.72
Pier Skew, UpSta & Num, DnSta & Num=  ,4970.4, 2 ,4970.4, 2 , 0 , 0 , 0 ,,
     2.1     2.1
   -1.03   19.71
     2.1     2.1
   -1.11   19.63
Pier Skew, UpSta & Num, DnSta & Num=  ,5027.5, 2 ,5027.5, 2 , 0 , 0 , 0 ,,
     2.1     2.1
   -1.67   19.86
     2.1     2.1
   -1.75   19.78
Abutment Skew #Up #Dn= , 2 , 2
  4923.9  4968.5
   18.48     3.8
  4923.9  4968.5
    18.4    3.72
Abutment Skew #Up #Dn= , 2 , 2
  5033.6 5076.99
    4.76   18.54
  5033.6 5076.99
    4.68   18.46
BR Coef= 1 , 1 , 0 ,1.25, 0 ,,,0.8,0,2,0,
WSPro=,,,, 1 ,,,, 0 ,,,, 0 ,,,,-1 ,-1 ,-1 , 0 , 0 , 0 , 0 , 0
BR U #Sta/Elev= 101
  3418.2    32.4  3478.2    31.4  3493.2    31.6  3503.2      32  3513.2    31.6
  3548.2    31.3  3578.2    30.6  3593.2    29.8  3603.2    28.9  3608.2    28.7
  3713.2    28.9  3720.6    28.6  3745.6    26.8  3760.6    26.2  3781.2   26.14
  3795.6    26.1  3810.6    26.7  3856.2   27.11  3865.6    27.2  3910.6    26.9
    3982    27.1    4027    26.8  4075.8   26.85    4117    26.9    4127    26.6
    4137    26.8    4277    26.3    4287    26.5    4302    26.1  4317.2   25.29
    4332    24.5    4352    24.4  4361.3    24.7  4386.3    25.4  4471.3    25.3
  4491.3    24.4  4496.3      24    4575   24.66  4579.8    24.7  4594.8    24.3
  4624.8    23.1  4644.8    22.9  4694.8    23.4  4726.3    22.8  4733.4   22.66
  4767.5   22.33  4769.9   22.31  4805.9   22.16  4810.8   22.14  4846.3   21.94
  4847.9   21.93  4879.4      22  4887.4    21.5  4898.7   20.79 4905.19   19.28
  4905.3   19.26 4905.41   19.23  4922.7   15.21  4923.9   14.92 4924.01   14.89
  4924.1   14.87  4968.3    4.02  4968.4    3.98  4968.5     3.8  4970.4     .43
  4973.3    -.84  4997.1   -1.23  5005.7   -2.76  5014.9   -2.18  5016.8   -2.06
  5027.5    -.52  5029.7     .81  5033.5    4.66  5033.6    4.76  5064.8    8.31
  5065.1    13.3  5070.8   16.79 5076.79   17.41  5076.9   17.42    5077   17.43
    5087   18.47  5094.2   20.58  5096.6   21.28  5112.9   22.36 5124.49   22.35
  5124.6   22.35 5124.71   22.35  5139.8   22.34  5145.6   22.35  5180.4   22.42
  5186.5   22.55  5223.5   23.36  5237.4   23.72  5279.9   24.82  5301.5   25.38
  5309.2    24.7  5319.9   24.72  5729.2    25.6  5882.4   26.15  6062.7    26.8
  6062.8    26.8
BR U #Mann= 4
  3418.2      .2  3418.2      .1  4898.7     .04  5070.8      .1
BR U Banks=4898.7,5070.8
BR D #Sta/Elev= 101
  3418.2   32.32  3478.2   31.32  3493.2   31.52  3503.2   31.92  3513.2   31.52
  3548.2   31.22  3578.2   30.52  3593.2   29.72  3603.2   28.82  3608.2   28.62
  3713.2   28.82  3720.6   28.52  3745.6   26.72  3760.6   26.12  3781.2   26.06
  3795.6   26.02  3810.6   26.62  3856.2   27.03  3865.6   27.12  3910.6   26.82
    3982   27.02    4027   26.72  4075.8   26.77    4117   26.82    4127   26.52
    4137   26.72    4277   26.22    4287   26.42    4302   26.02  4317.2   25.21
    4332   24.42    4352   24.32  4361.3   24.62  4386.3   25.32  4471.3   25.22
  4491.3   24.32  4496.3   23.92    4575   24.58  4579.8   24.62  4594.8   24.22
  4624.8   23.02  4644.8   22.82  4694.8   23.32  4726.3   22.72  4733.4   22.58
  4767.5   22.25  4769.9   22.23  4805.9   22.08  4810.8   22.06  4846.3   21.86
  4847.9   21.85  4879.4   21.92  4887.4   21.42  4898.7   20.71 4905.19    19.2
  4905.3   19.18 4905.41   19.15  4922.7   15.13  4923.9   14.84 4924.01   14.81
  4924.1   14.79  4968.3    3.94  4968.4     3.9  4968.5    3.72  4970.4     .35
  4973.3    -.92  4997.1   -1.31  5005.7   -2.84  5014.9   -2.26  5016.8   -2.14
  5027.5     -.6  5029.7     .73  5033.5    4.58  5033.6    4.68  5064.8    8.23
  5065.1   13.22  5070.8   16.71 5076.79   17.33  5076.9   17.34    5077   17.35
    5087   18.39  5094.2    20.5  5096.6    21.2  5112.9   22.28 5124.49   22.27
  5124.6   22.27 5124.71   22.27  5139.8   22.26  5145.6   22.27  5180.4   22.34
  5186.5   22.47  5223.5   23.28  5237.4   23.64  5279.9   24.74  5301.5    25.3
  5309.2   24.62  5319.9   24.64  5729.2   25.52  5882.4   26.07  6062.7   26.72
  6062.8   26.72
BR D #Mann= 4
  3418.2      .2  3418.2      .1  4898.7     .04  5070.8      .1
BR D Banks=4898.7,5070.8
BC Design=,, 0 ,, 0 ,,,,,,
BC HTab HWMax=32.39
BC Use User HTab Curves=0
BC User HTab FreeFlow(D)= 0

Type RM Length L Ch R = 1 ,8877.7  ,430.8,402.2,367.7
BEGIN DESCRIPTION:
Downstream Section of Bridge/Culvert/Weir
END DESCRIPTION:
XS GIS Cut Line= 6
      3158969.52     13814587.36      3159204.98     13814587.36
       3159610.6      13814704.3      3159815.62     13814831.74
      3160480.57     13815119.89      3161497.73     13815197.24
#Sta/Elev= 30
  3418.2   32.35  3548.2   31.25  3608.2   28.65  3713.2   28.85  3760.6   26.15
  3865.6   27.15    4287   26.45    4332   24.45  4386.3   25.35  4496.3   23.95
  4579.8   24.65  4624.8   23.05  4879.4   21.95  4898.7   20.74  4968.3    3.97
  4970.4     .38  4973.3    -.89  4997.1   -1.28  5005.7   -2.81  5027.5    -.57
  5033.6    4.71  5064.8    8.26  5065.1   13.25  5070.8   16.74    5087   18.42
  5096.6   21.23  5112.9   22.31  5180.4   22.37  5301.5   25.33  6062.8   26.75
#Mann= 4 , 1 , 0
  3418.2      .2       0  3418.2      .1       0  4898.7     .04       0
  5070.8      .1       0
#XS Ineff= 2 , 0
       0    4913      21    5086       0      21
Permanent Ineff=
       F       F
Bank Sta=4898.7,5070.8
XS Rating Curve= 0 ,0
Exp/Cntr=0.5,0.3

Type RM Length L Ch R = 1 ,8475.5  ,468.8,650.2,779
BEGIN DESCRIPTION:
Cross Section 8475.5-Interpolated
END DESCRIPTION:
XS GIS Cut Line= 6
      3159693.01     13814924.16      3160021.41     13815362.02
       3160214.8     13815493.38      3160404.54     13815533.52
      3161046.74     13815493.38      3161320.41     13815351.08
#Sta/Elev= 30
  3943.6    26.8  4143.6    24.8  4490.9    24.8  4670.9    22.3  4724.7    23.3
  4874.7    21.8  4904.7    20.4 4932.08   16.93 4950.68   12.18 4964.08    9.46
 4972.18     .32 5000.28   -1.71 5007.78   -1.07 5020.58   -1.61 5027.78     .09
 5032.28    3.94 5034.58    5.28 5035.48    8.23 5039.18   10.27 5041.08   12.05
 5042.78   13.02 5050.38   13.68  5078.7    17.5  5174.4    19.2  5374.4    21.3
  5394.4    22.9  5434.4    23.6  5474.4    22.8  5562.1    25.1  5870.6    25.7
#Mann= 5 , 1 , 0
  3943.6      .2       0  3943.6      .1       0  4904.7     .04       0
 5050.38      .1       0  5870.6      .2       0
Bank Sta=4904.7,5050.38
XS Rating Curve= 0 ,0
Exp/Cntr=0.5,0.3

Type RM Length L Ch R = 1 ,7825.3  ,24,24,24
BEGIN DESCRIPTION:
Upstream Section of Bridge/Culvert/Weir
END DESCRIPTION:
XS GIS Cut Line= 6
      3159588.89      13815055.6      3160109.19     13815945.44
      3160111.48     13815948.02      3160169.03     13816030.71
       3160181.5     13816048.26      3160837.74     13816912.77
#Sta/Elev= 30
    3900    27.1  4697.7   23.11 4873.18   19.67 4915.28   19.66 4932.08   14.25
 4964.08    6.78 4970.68     .91 4972.18   -2.36 5000.28   -4.39 5020.58   -4.29
 5027.78   -2.59 5034.58     2.6 5035.48    5.55 5041.08    9.37 5042.78   10.34
 5050.38      11 5054.28   11.14 5060.08      15 5062.48      15 5065.88   12.84
 5069.68      12 5071.38    12.8 5078.88   12.67 5090.98   20.73  5099.4   22.47
  5453.6   24.26  5528.6   23.13  5553.6   24.42  6099.9   26.06  6141.9   26.17
#Mann= 5 , 1 , 0
    3900      .2       0    3900      .1       0 4915.28     .04       0
 5050.38      .1       0  6099.9      .2       0
#XS Ineff= 2 , 0
       0  4938.5    12.5    5056       0    12.5
Permanent Ineff=
       F       F
Bank Sta=4915.28,5050.38
XS Rating Curve= 0 ,0
Exp/Cntr=0.5,0.3

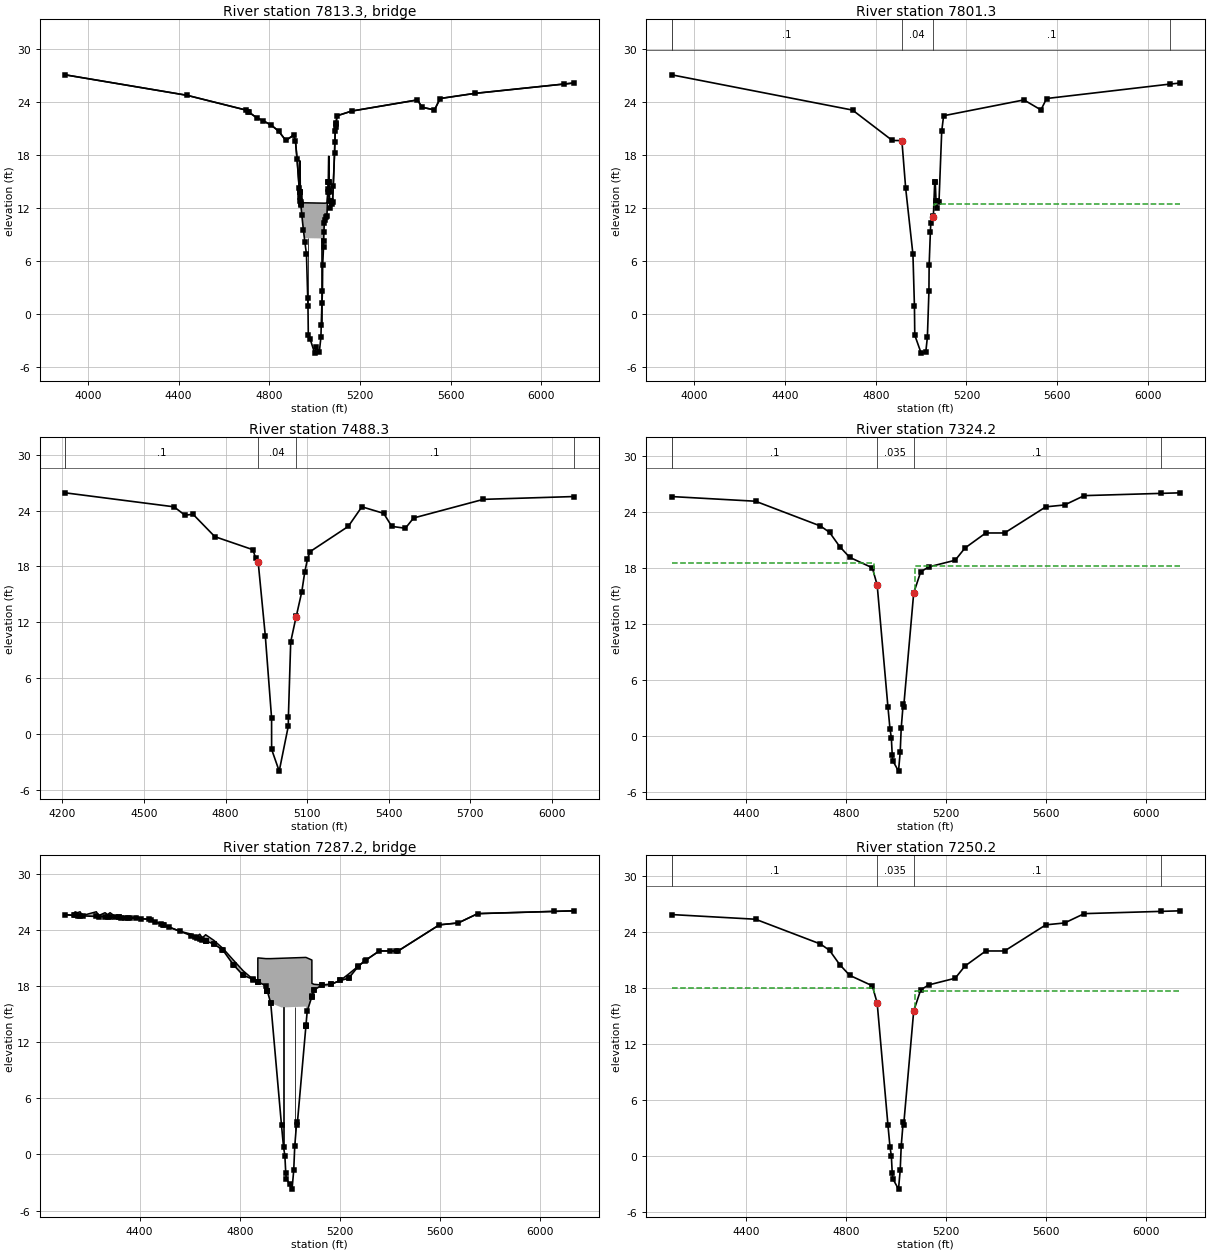
Type RM Length L Ch R = 3 ,7813.3  ,,,
BEGIN DESCRIPTION:
48" PIPELINE
END DESCRIPTION:
Bridge Culvert--1,0,-1,-1, 0
Deck Dist Width WeirC Skew NumUp NumDn MinLoCord MaxHiCord MaxSubmerge Is_Ogee
10,4,2.6,0, 50, 50, , , 0.95, 0, 1,1,,
    3900  4437.7  4697.7 4743.68 4808.68 4841.28 4873.18 4907.08 4915.28 4922.58
 4932.08 4933.58 4935.88 4937.58 4938.88 4939.28 4943.48 4950.68 4957.08 5039.98
 5041.08 5042.78 5050.38 5054.28 5058.38 5060.08 5061.58 5062.48 5064.18 5064.28
 5065.88 5069.68 5071.38 5075.68 5078.88 5082.08 5087.88 5089.18 5090.98 5092.98
 5093.08  5094.4  5099.4  5163.6  5453.6  5473.6  5528.6  5553.6  5706.5  6141.9
    27.1   24.78   23.11   22.26   21.41   20.73   19.67   20.28   19.66   17.57
   14.25   17.38   17.35   12.93    12.9   12.58   12.59    12.6   12.62   12.58
   12.58   12.58   12.59    12.6   13.88   15.01   17.88   17.87   17.86   13.86
   12.84      12    12.8   12.54   12.67    14.5   18.22   19.49   20.73   21.52
   21.23   21.69   22.47      23   24.26   23.43   23.13   24.42      25   26.17
    27.1   24.78   23.11   22.26   21.41   20.73   19.67   20.28   19.66   17.57
   14.25   13.87   13.35   12.86   12.52   12.41   11.25     9.5    8.62    8.58
    9.37   10.34      11   11.14   13.87      15      15      15   13.92   13.86
   12.84      12    12.8   12.54   12.67    14.5   18.22   19.49   20.73   21.52
   21.23   21.69   22.47      23   24.26   23.43   23.13   24.42      25   26.17
    3900  4437.7  4697.7 4743.68 4808.68 4841.28 4873.18 4907.08 4915.28 4922.58
 4932.08 4933.58 4935.88 4937.58 4938.88 4939.28 4943.48 4950.68 4957.08 5039.98
 5041.08 5042.78 5050.38 5054.28 5058.38 5060.08 5061.58 5062.48 5064.18 5064.28
 5065.88 5069.68 5071.38 5075.68 5078.88 5082.08 5087.88 5089.18 5090.98 5092.98
 5093.08  5094.4  5099.4  5163.6  5453.6  5473.6  5528.6  5553.6  5706.5  6141.9
    27.1   24.78   23.11   22.26   21.41   20.73   19.67   20.28   19.66   17.57
   14.25   17.38   17.35   12.93    12.9   12.58   12.59    12.6   12.62   12.58
   12.58   12.58   12.59    12.6   13.88   15.01   17.88   17.87   17.86   13.86
   12.84      12    12.8   12.54   12.67    14.5   18.22   19.49   20.73   21.52
   21.23   21.69   22.47      23   24.26   23.43   23.13   24.42      25   26.17
    27.1   24.78   23.11   22.26   21.41   20.73   19.67   20.28   19.66   17.57
   14.25   13.87   13.35   12.86   12.52   12.41   11.25     9.5    8.62    8.58
    9.37   10.34      11   11.14   13.87      15      15      15   13.92   13.86
   12.84      12    12.8   12.54   12.67    14.5   18.22   19.49   20.73   21.52
   21.23   21.69   22.47      23   24.26   23.43   23.13   24.42      25   26.17
Pier Skew, UpSta & Num, DnSta & Num=  ,4970.7, 2 ,4970.7, 2 , 0 , 0 , 0 ,,
     2.5     2.5
   -2.82    9.64
     2.5     2.5
   -2.82    9.64
Pier Skew, UpSta & Num, DnSta & Num=  ,5029.2, 2 ,5029.2, 2 , 0 , 0 , 0 ,,
     2.5     2.5
   -3.44    9.59
     2.5     2.5
   -3.44    9.59
BR Coef= 1 , 1 , 0 ,1.25, 0 ,,,0.8,0,2,0,
WSPro=,,,, 1 ,,,, 0 ,,,, 0 ,,,,-1 ,-1 ,-1 , 0 , 0 , 0 , 0 , 0
BR U #Sta/Elev= 75
    3900    27.1  4437.7   24.78  4697.7   23.11 4707.98   22.88 4709.48   22.88
 4743.68   22.26 4773.78    21.9 4808.68   21.41 4841.28   20.73 4873.18   19.67
 4907.08   20.28 4915.28   19.66 4922.58   17.57 4932.08   14.25 4933.58   13.87
 4933.69   13.84 4933.78   13.82 4935.88   13.29 4937.58   12.86 4938.38   12.66
 4938.88   12.52 4939.28   12.41 4943.48   11.25 4950.68     9.5 4957.08    8.18
 4964.08    6.78 4969.68     1.8 4970.68     .91 4972.18   -2.36 4980.68   -2.84
 5000.28   -4.39 5007.78   -3.75 5020.58   -4.29 5027.78   -2.59 5029.18   -1.22
 5032.28    1.26 5034.58     2.6 5035.48    5.55 5039.18    7.59 5039.98    8.34
 5041.08    9.37 5042.78   10.34 5046.58    10.7 5050.38      11 5054.28   11.14
 5058.38   13.87 5058.78   14.13 5059.98   14.93 5060.08      15 5061.58      15
 5062.48      15 5064.07   13.99 5064.18   13.92 5064.28   13.86 5065.88   12.84
 5069.68      12 5071.38    12.8 5075.68   12.54 5078.88   12.67 5082.08    14.5
 5087.88   18.22 5089.18   19.49 5090.98   20.73 5092.98   21.52 5093.08   21.23
  5094.4   21.69  5099.4   22.47  5163.6      23  5453.6   24.26  5473.6   23.43
  5528.6   23.13  5553.6   24.42  5706.5      25  6099.9   26.06  6141.9   26.17
BR U #Mann= 5
    3900      .2    3900      .1 4915.28    .035 5050.38      .1  6099.9      .2
BR U Banks=4915.28,5050.38
BR D #Sta/Elev= 75
    3900    27.1  4437.7   24.78  4697.7   23.11 4707.98   22.88 4709.48   22.88
 4743.68   22.26 4773.78    21.9 4808.68   21.41 4841.28   20.73 4873.18   19.67
 4907.08   20.28 4915.28   19.66 4922.58   17.57 4932.08   14.25 4933.58   13.87
 4933.69   13.84 4933.78   13.82 4935.88   13.29 4937.58   12.86 4938.38   12.66
 4938.88   12.52 4939.28   12.41 4943.48   11.25 4950.68     9.5 4957.08    8.18
 4964.08    6.78 4969.68     1.8 4970.68     .91 4972.18   -2.36 4980.68   -2.84
 5000.28   -4.39 5007.78   -3.75 5020.58   -4.29 5027.78   -2.59 5029.18   -1.22
 5032.28    1.26 5034.58     2.6 5035.48    5.55 5039.18    7.59 5039.98    8.34
 5041.08    9.37 5042.78   10.34 5046.58    10.7 5050.38      11 5054.28   11.14
 5058.38   13.87 5058.78   14.13 5059.98   14.93 5060.08      15 5061.58      15
 5062.48      15 5064.07   13.99 5064.18   13.92 5064.28   13.86 5065.88   12.84
 5069.68      12 5071.38    12.8 5075.68   12.54 5078.88   12.67 5082.08    14.5
 5087.88   18.22 5089.18   19.49 5090.98   20.73 5092.98   21.52 5093.08   21.23
  5094.4   21.69  5099.4   22.47  5163.6      23  5453.6   24.26  5473.6   23.43
  5528.6   23.13  5553.6   24.42  5706.5      25  6099.9   26.06  6141.9   26.17
BR D #Mann= 5
    3900      .2    3900      .1 4915.28    .035 5050.38      .1  6099.9      .2
BR D Banks=4915.28,5050.38
BC Design=,, 0 ,, 0 ,,,,,,
BC HTab HWMax=27.1
BC Use User HTab Curves=0
BC User HTab FreeFlow(D)= 0

Type RM Length L Ch R = 1 ,7801.3  ,374.4,313,269.7
BEGIN DESCRIPTION:
Downstream Section of Bridge/Culvert/Weir
END DESCRIPTION:
XS GIS Cut Line= 6
      3159569.72     13815070.03      3160090.01     13815959.88
       3160092.3     13815962.46      3160149.85     13816045.15
      3160162.32      13816062.7      3160818.57     13816927.21
#Sta/Elev= 30
    3900   27.11  4697.7   23.12 4873.18   19.68 4915.28   19.67 4932.08   14.26
 4964.08    6.79 4970.68     .92 4972.18   -2.35 5000.28   -4.38 5020.58   -4.28
 5027.78   -2.58 5034.58    2.61 5035.48    5.56 5041.08    9.38 5042.78   10.35
 5050.38   11.01 5054.28   11.15 5060.08   15.01 5062.48   15.01 5065.88   12.85
 5069.68   12.01 5071.38   12.81 5078.88   12.68 5090.98   20.74  5099.4   22.48
  5453.6   24.27  5528.6   23.14  5553.6   24.43  6099.9   26.07  6141.9   26.18
#Mann= 5 , 1 , 0
    3900      .2       0    3900      .1       0 4915.28     .04       0
 5050.38      .1       0  6099.9      .2       0
#XS Ineff= 2 , 0
       0  4938.5    12.5    5056       0    12.5
Permanent Ineff=
       F       F
Bank Sta=4915.28,5050.38
XS Rating Curve= 0 ,0
Exp/Cntr=0.5,0.3

Type RM Length L Ch R = 1 ,7488.3  ,155.5,164.1,143.8
BEGIN DESCRIPTION:
Cross Section 7488.3-Interpolated
END DESCRIPTION:
XS GIS Cut Line= 5
      3159229.61     13815865.57      3159871.81     13816212.21
      3159999.52     13816292.49      3160524.95     13816686.56
      3160721.99     13816952.93
#Sta/Elev= 29
  4210.4    25.9  4610.4    24.4  4650.4    23.5  4680.4    23.6  4760.4    21.2
  4900.4    19.8  4910.4    18.9  4919.7   18.49  4945.9   10.59  4969.1    1.74
  4969.2   -1.61  4997.1   -3.95  5030.6     .89  5030.9    1.89  5039.4    9.92
  5058.9   12.56  5060.2    12.7  5080.2    15.3    5091    17.4    5101    18.8
    5111    19.6    5251    22.3    5301    24.4    5381    23.7    5411    22.3
    5461    22.1    5491    23.2  5747.8    25.2  6079.1    25.5
#Mann= 5 , 1 , 0
  4210.4      .2       0  4210.4      .1       0  4919.7     .04       0
  5058.9      .1       0  6079.1      .2       0
Bank Sta=4919.7,5058.9
XS Rating Curve= 0 ,0
Exp/Cntr=0.5,0.3

Type RM Length L Ch R = 1 ,7324.2  ,74,74,74
BEGIN DESCRIPTION:
Upstream Section of Bridge/Culvert/Weir
END DESCRIPTION:
XS GIS Cut Line= 6
      3159054.59     13815954.89      3159512.41     13816196.75
      3159795.93     13816355.87      3159905.02      13816417.1
      3160179.53     13816571.16      3160701.57     13817107.73
#Sta/Elev= 30
  4102.7   25.69  4437.7   25.19    4697   22.54  4733.5   21.86  4774.2   20.33
  4814.1   19.18  4904.5   18.06  4923.9   16.22  4967.1    3.11  4975.2     .78
  4980.5    -.12  4984.1   -2.01  4986.2    -2.6  5009.2   -3.72  5015.9   -1.71
    5020     .89  5027.8    3.46  5029.7    3.12  5069.9   15.36  5097.8   17.62
  5129.5   18.15  5235.7   18.87  5274.5   20.17    5358   21.79    5433   21.79
    5598   24.59    5673   24.79  5751.4   25.79  6056.9   26.03  6134.1   26.09
#Mann= 5 , 1 , 0
  4102.7      .2       0  4102.7      .1       0  4923.9    .035       0
  5069.9      .1       0  6056.9      .2       0
#XS Ineff= 2 , 0
       0    4913    18.6    5074       0    18.2
Permanent Ineff=
       F       F
Bank Sta=4923.9,5069.9
XS Rating Curve= 0 ,0
Exp/Cntr=0.5,0.3

Type RM Length L Ch R = 3 ,7287.2  ,,,
BEGIN DESCRIPTION:
AHRENS STREET
Structure ID: C06-3
END DESCRIPTION:
Node Name=AHRENS STREET
Bridge Culvert--1,0,-1,-1, 0
Deck Dist Width WeirC Skew NumUp NumDn MinLoCord MaxHiCord MaxSubmerge Is_Ogee
10,54,2.6,0, 55, 48, , , 0.95, 0, 1,1,,
  4102.7  4137.7    4142    4152    4162    4172    4227    4237    4262    4272
    4282    4302    4317    4327    4362    4387    4407  4437.7    4447    4462
    4562    4607  4620.5  4630.5  4640.5  4650.5  4663.9    4697  4733.5  4774.2
  4814.1  4852.2 4872.39  4872.5  4904.5    4924  4967.1 5064.59  5064.7  5069.9
  5088.5 5088.61  5096.8  5128.3  5164.7  5202.3  5235.7  5274.5  5303.2    5358
    5433    5598    5673  5751.4  6134.1
    25.7    25.6      26    25.9      26    25.6      26    25.6    25.9    25.7
    25.9    25.5    25.6   25.39   25.34    25.5   25.26    25.2    25.2   24.94
   23.91    23.6   23.32    23.4    23.6    23.2   23.54   22.93   22.06   20.84
   19.67   18.79   18.56   21.06   20.98   20.98   21.02   21.11   21.11   21.05
   20.83   18.33   18.23   18.16   18.23   18.65   19.34   20.19   20.81   21.81
    21.8    24.6    24.8    25.8    26.1
    25.7    25.6    25.6   25.58   25.57   25.56    25.5   25.49   25.46   25.45
   25.44   25.42    25.4   25.38   25.33   25.28   25.25    25.2    25.1   24.93
    23.9   23.44   23.31   23.21    23.1      23   22.87   22.55   21.87   20.34
   19.19   18.78   18.51    18.5   18.07   16.22   15.75   15.84   13.79   15.37
   16.92   16.93   17.61   18.14   18.23   18.64   18.88   20.18    20.8    21.8
    21.8    24.6    24.8    25.8    26.1
  4102.7  4137.7    4142    4152    4162    4172    4227    4237    4262    4272
    4282    4302    4387  4437.7  4620.5  4630.5  4640.5  4650.5  4663.9    4697
  4733.5  4774.2  4814.1  4852.2 4872.39  4872.5  4904.5    4924  4967.1 5064.59
  5064.7  5069.9  5088.5 5088.61  5096.8  5097.8  5129.5  5163.8  5202.3  5235.7
  5274.5  5303.2    5358    5433    5598    5673  5751.4  6134.1
   25.86   25.76      26    25.9      26   25.72      26   25.65    25.9    25.7
    25.9   25.58    25.5   25.36   23.47    23.4    23.6    23.2   23.54   22.93
   22.06   20.84   19.67   18.94   18.67   21.06   20.98   20.98   21.02   21.11
   21.11   21.05   20.83   18.33   18.23   18.22   18.32   18.38    18.8   19.34
   20.34   20.96   21.96   21.96   24.76   24.96   25.96   26.26
   25.86   25.76   25.76   25.74   25.73   25.72   25.66   25.65   25.62   25.61
    25.6   25.58   25.44   25.36   23.47   23.37   23.26   23.16   23.03   22.71
   22.03    20.5   19.35   18.94   18.67   18.66   18.23   16.38   15.91      16
   13.95   15.53   17.08   17.09   17.77   17.79   18.32   18.38    18.8   19.04
   20.34   20.96   21.96   21.96   24.76   24.96   25.96   26.26
Pier Skew, UpSta & Num, DnSta & Num=  ,4975.2, 2 ,4975.2, 2 , 0 , 0 , 0 ,,
     1.5     1.5
    -.34   16.76
     1.5     1.5
    -.18   16.92
Pier Skew, UpSta & Num, DnSta & Num=  ,5019.9, 2 ,5019.9, 2 , 0 , 0 , 0 ,,
     1.5     1.5
    -.64    16.8
     1.5     1.5
    -.48   16.96
BR Coef= 1 , 1 , 0 ,1.25, 0 ,,,0.8,-1,2,0,
WSPro=,,,, 1 ,,,, 0 ,,,, 0 ,,,,-1 ,-1 ,-1 , 0 , 0 , 0 , 0 , 0
BR U #Sta/Elev= 98
  4102.7    25.7  4137.7    25.6    4142    25.6    4152   25.58    4162   25.57
    4172   25.56    4227    25.5    4237   25.49    4262   25.46    4272   25.45
    4282   25.44    4302   25.42    4317    25.4  4317.7    25.4    4327   25.38
    4342   25.36    4352   25.34    4362   25.33    4387   25.28    4407   25.25
  4437.7    25.2    4447    25.1    4462   24.93    4487   24.66  4492.7    24.6
    4497   24.56    4517   24.35    4562    23.9    4607   23.44  4620.5   23.31
  4630.5   23.21  4640.5    23.1  4650.5      23  4663.9   22.87  4665.7   22.85
  4665.8   22.85    4697   22.55  4698.7   22.52  4730.8   21.92  4733.5   21.87
  4774.2   20.34  4776.9   20.26  4813.7    19.2  4814.1   19.19  4852.2   18.78
    4855   18.74 4872.39   18.51  4872.5    18.5 4872.61    18.5  4904.5   18.07
 4910.01   17.55  4910.1   17.54  4910.2   17.53  4910.3   17.52  4923.9   16.23
    4924   16.22  4967.1    3.12  4975.2     .79  4980.5    -.11  4984.1      -2
  4986.2   -2.59    5000   -3.21  5009.2   -3.71  5015.9    -1.7    5020      .9
  5027.8    3.47  5029.7    3.13  5064.5   13.73 5064.59   13.75  5064.7   13.79
  5064.9   13.85  5069.9   15.37 5088.39   16.91  5088.5   16.92 5088.61   16.93
  5096.8   17.61  5097.8   17.63  5128.3   18.14  5129.5   18.16  5163.8   18.22
  5164.7   18.23  5202.2   18.64  5202.3   18.64  5235.7   18.88  5237.2   18.93
  5271.3   20.07  5274.5   20.18    5299   20.71  5303.2    20.8    5358    21.8
  5400.5    21.8  5422.8    21.8    5433    21.8    5598    24.6    5673    24.8
  5751.4    25.8  6056.9   26.04  6134.1    26.1
BR U #Mann= 5
  4102.7      .2  4102.7      .1  4923.9    .035  5069.9      .1  6056.9      .2
BR U Banks=4923.9,5069.9
BR D #Sta/Elev= 98
  4102.7   25.86  4137.7   25.76    4142   25.76    4152   25.74    4162   25.73
    4172   25.72    4227   25.66    4237   25.65    4262   25.62    4272   25.61
    4282    25.6    4302   25.58    4317   25.56  4317.7   25.56    4327   25.54
    4342   25.52    4352    25.5    4362   25.49    4387   25.44    4407   25.41
  4437.7   25.36    4447   25.26    4462   25.09    4487   24.82  4492.7   24.76
    4497   24.72    4517   24.51    4562   24.06    4607    23.6  4620.5   23.47
  4630.5   23.37  4640.5   23.26  4650.5   23.16  4663.9   23.03  4665.7   23.01
  4665.8   23.01    4697   22.71  4698.7   22.68  4730.8   22.08  4733.5   22.03
  4774.2    20.5  4776.9   20.42  4813.7   19.36  4814.1   19.35  4852.2   18.94
    4855    18.9 4872.39   18.67  4872.5   18.66 4872.61   18.66  4904.5   18.23
 4910.01   17.71  4910.1    17.7  4910.2   17.69  4910.3   17.68  4923.9   16.39
    4924   16.38  4967.1    3.28  4975.2     .95  4980.5     .05  4984.1   -1.84
  4986.2   -2.43    5000   -3.05  5009.2   -3.55  5015.9   -1.54    5020    1.06
  5027.8    3.63  5029.7    3.29  5064.5   13.89 5064.59   13.91  5064.7   13.95
  5064.9   14.01  5069.9   15.53 5088.39   17.07  5088.5   17.08 5088.61   17.09
  5096.8   17.77  5097.8   17.79  5128.3    18.3  5129.5   18.32  5163.8   18.38
  5164.7   18.39  5202.2    18.8  5202.3    18.8  5235.7   19.04  5237.2   19.09
  5271.3   20.23  5274.5   20.34    5299   20.87  5303.2   20.96    5358   21.96
  5400.5   21.96  5422.8   21.96    5433   21.96    5598   24.76    5673   24.96
  5751.4   25.96  6056.9    26.2  6134.1   26.26
BR D #Mann= 5
  4102.7      .2  4102.7      .1  4923.9    .035  5069.9      .1  6056.9      .2
BR D Banks=4923.9,5069.9
BC Design=,, 0 ,, 0 ,,,,,,
BC HTab HWMax=26.09
BC Use User HTab Curves=0
BC User HTab FreeFlow(D)= 0

Type RM Length L Ch R = 1 ,7250.2  ,395.2,480.5,576.9
BEGIN DESCRIPTION:
Downstream Section of Bridge/Culvert/Weir
END DESCRIPTION:
XS GIS Cut Line= 6
      3159018.77     13816019.64      3159476.59     13816261.51
      3159760.11     13816420.63       3159869.2     13816481.86
      3160143.71     13816635.92      3160665.75     13817172.48
#Sta/Elev= 30
  4102.7   25.84  4437.7   25.34    4697   22.69  4733.5   22.01  4774.2   20.48
  4814.1   19.33  4904.5   18.21  4923.9   16.37  4967.1    3.26  4975.2     .93
  4980.5     .03  4984.1   -1.86  4986.2   -2.45  5009.2   -3.57  5015.9   -1.56
    5020    1.04  5027.8    3.61  5029.7    3.27  5069.9   15.51  5097.8   17.77
  5129.5    18.3  5235.7   19.02  5274.5   20.32    5358   21.94    5433   21.94
    5598   24.74    5673   24.94  5751.4   25.94  6056.9   26.18  6134.1   26.24
#Mann= 5 , 1 , 0
  4102.7      .2       0  4102.7      .1       0  4923.9    .035       0
  5069.9      .1       0  6056.9      .2       0
#XS Ineff= 2 , 0
       0    4913      18    5074       0    17.6
Permanent Ineff=
       F       F
Bank Sta=4923.9,5069.9
XS Rating Curve= 0 ,0
Exp/Cntr=0.5,0.3