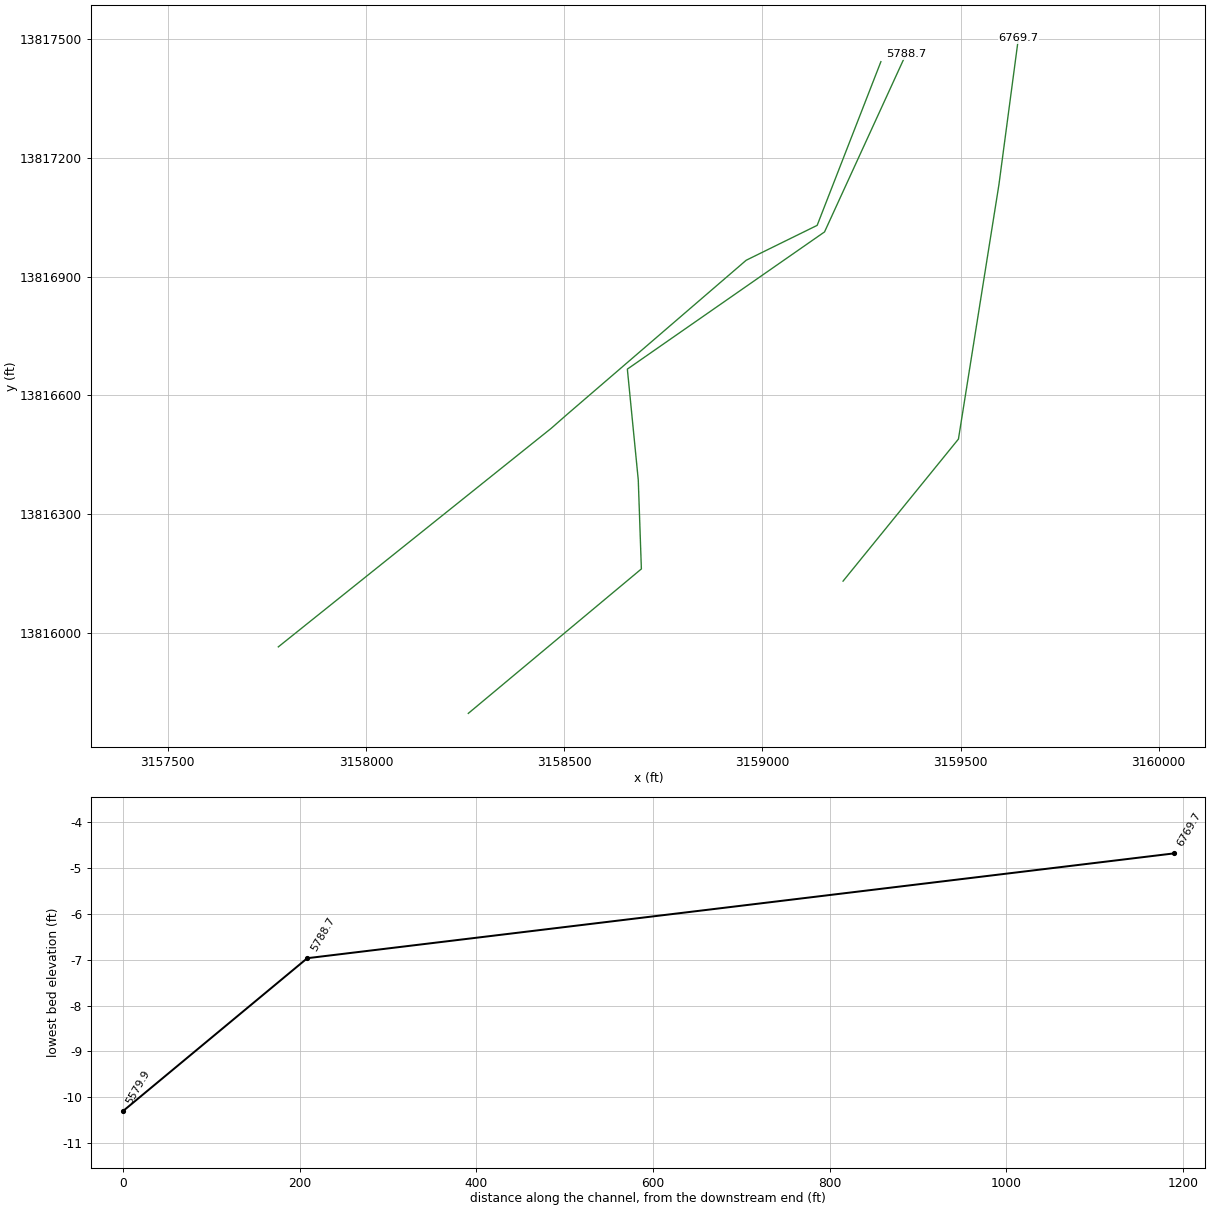
HEC-RAS study C106-00-00.PRJ: C106-00-00 2015

--- C106-00-00.g01 (geometry) --- (continued)

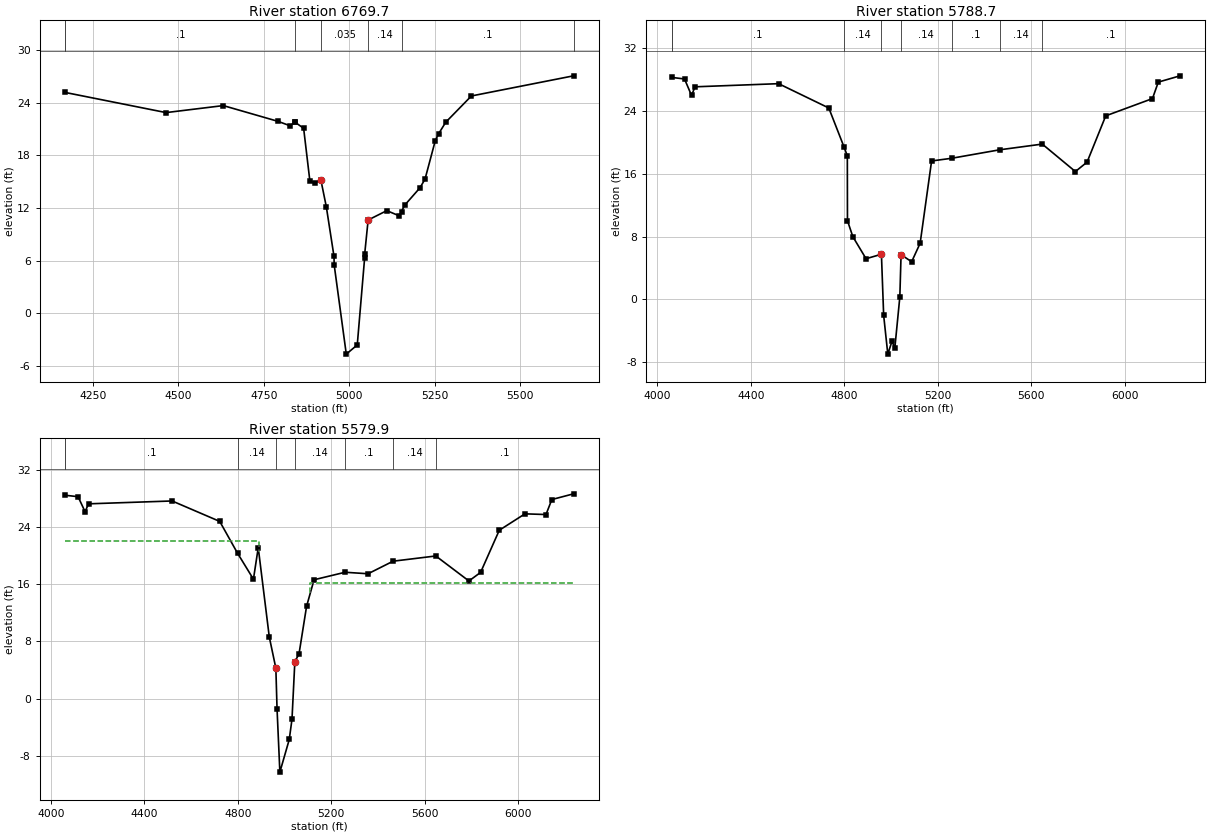
Type RM Length L Ch R = 1 ,6769.7  ,955.6,981,889.7
BEGIN DESCRIPTION:
Cross Section 6769.7
END DESCRIPTION:
XS GIS Cut Line= 4
       3159203.7     13816130.35      3159494.78     13816489.47
      3159596.84     13817132.09      3159645.98     13817502.55
#Sta/Elev= 30
    4169    25.2    4464    22.9  4631.3    23.7  4791.3    21.9  4826.3    21.4
  4841.3    21.8  4842.1   21.78  4866.3    21.1  4884.5   15.09  4898.2   14.82
  4916.5   15.24  4932.6   12.15  4955.1    6.47  4955.6    5.51    4991   -4.69
  5023.1   -3.64  5044.7    6.31  5044.9    6.78  5054.9   10.63  5109.5    11.7
  5146.3    11.1  5152.6    11.6  5161.3    12.3  5206.3    14.3  5221.3    15.3
  5251.3    19.7  5261.3    20.5  5281.9    21.8  5356.9    24.8  5655.6    27.1
#Mann= 7 , 1 , 0
    4169      .2       0    4169      .1       0  4842.1     .14       0
  4916.5    .035       0  5054.9     .14       0  5152.6      .1       0
  5655.6      .2       0
Bank Sta=4916.5,5054.9
XS Rating Curve= 0 ,0
Exp/Cntr=0.3,0.1

Type RM Length L Ch R = 1 ,5788.7  ,254.4,208.8,38.1
BEGIN DESCRIPTION:
Cross Section 5788.7
END DESCRIPTION:
XS GIS Cut Line= 6
      3158258.36     13815796.03      3158694.96     13816161.19
       3158687.1     13816386.26      3158659.58     13816666.31
      3159156.97     13817013.15      3159362.46     13817462.43
#Sta/Elev= 30
  4061.1    28.3  4116.1    28.1  4146.1      26  4161.1    27.1  4518.8    27.5
  4733.8    24.4    4799   19.43  4813.1    18.3 4813.65   10.04 4836.65       8
 4893.25    5.19 4959.05    5.76 4968.65   -2.03 4986.35   -6.97 5004.05   -5.35
 5016.55   -6.16 5037.85     .31 5043.15    5.71 5088.45     4.8 5124.85    7.17
 5173.85   17.65  5259.4   17.99  5464.9   19.07  5647.7    19.8  5789.4    16.3
  5839.4    17.5  5919.4    23.4  6119.4    25.6  6144.4    27.7  6237.3    28.5
#Mann= 8 , 1 , 0
  4061.1      .2       0  4061.1      .1       0    4799     .14       0
 4959.05     .04       0 5043.15     .14       0  5259.4      .1       0
  5464.9     .14       0  5647.7      .1       0
Bank Sta=4959.05,5043.15
XS Rating Curve= 0 ,0
Exp/Cntr=0.5,0.3

Type RM Length L Ch R = 1 ,5579.9  ,95,95,95
BEGIN DESCRIPTION:
Upstream Section of Bridge/Culvert/Weir
END DESCRIPTION:
XS GIS Cut Line= 6
      3157779.12     13815964.16       3158467.8     13816516.89
      3158506.85     13816551.23      3158959.41     13816941.58
      3159138.39     13817029.74      3159299.18     13817443.59
#Sta/Elev= 30
  4061.1   28.46  4116.1   28.26  4146.1   26.16  4161.1   27.26  4518.8   27.66
  4722.6    24.8    4799   20.34  4866.9   16.71  4887.5   21.12  4934.8    8.62
  4962.9    4.25    4968   -1.46  4980.1   -10.3  5020.3   -5.73    5032   -2.89
  5044.2    5.17    5062    6.24  5094.4   12.91  5126.4   16.63  5259.4   17.68
  5357.6   17.47  5464.9   19.23  5647.7   19.96  5789.4   16.46  5839.4   17.66
  5919.4   23.56  6029.4   25.86  6119.4   25.76  6144.4   27.86  6237.3   28.66
#Mann= 8 , 1 , 0
  4061.1      .2       0  4061.1      .1       0    4799     .14       0
  4962.9     .04       0  5044.2     .14       0  5259.4      .1       0
  5464.9     .14       0  5647.7      .1       0
#XS Ineff= 2 , 0
       0    4890      22    5110       0    16.2
Permanent Ineff=
       F       F
Bank Sta=4962.9,5044.2
XS Rating Curve= 0 ,0
Exp/Cntr=0.5,0.3