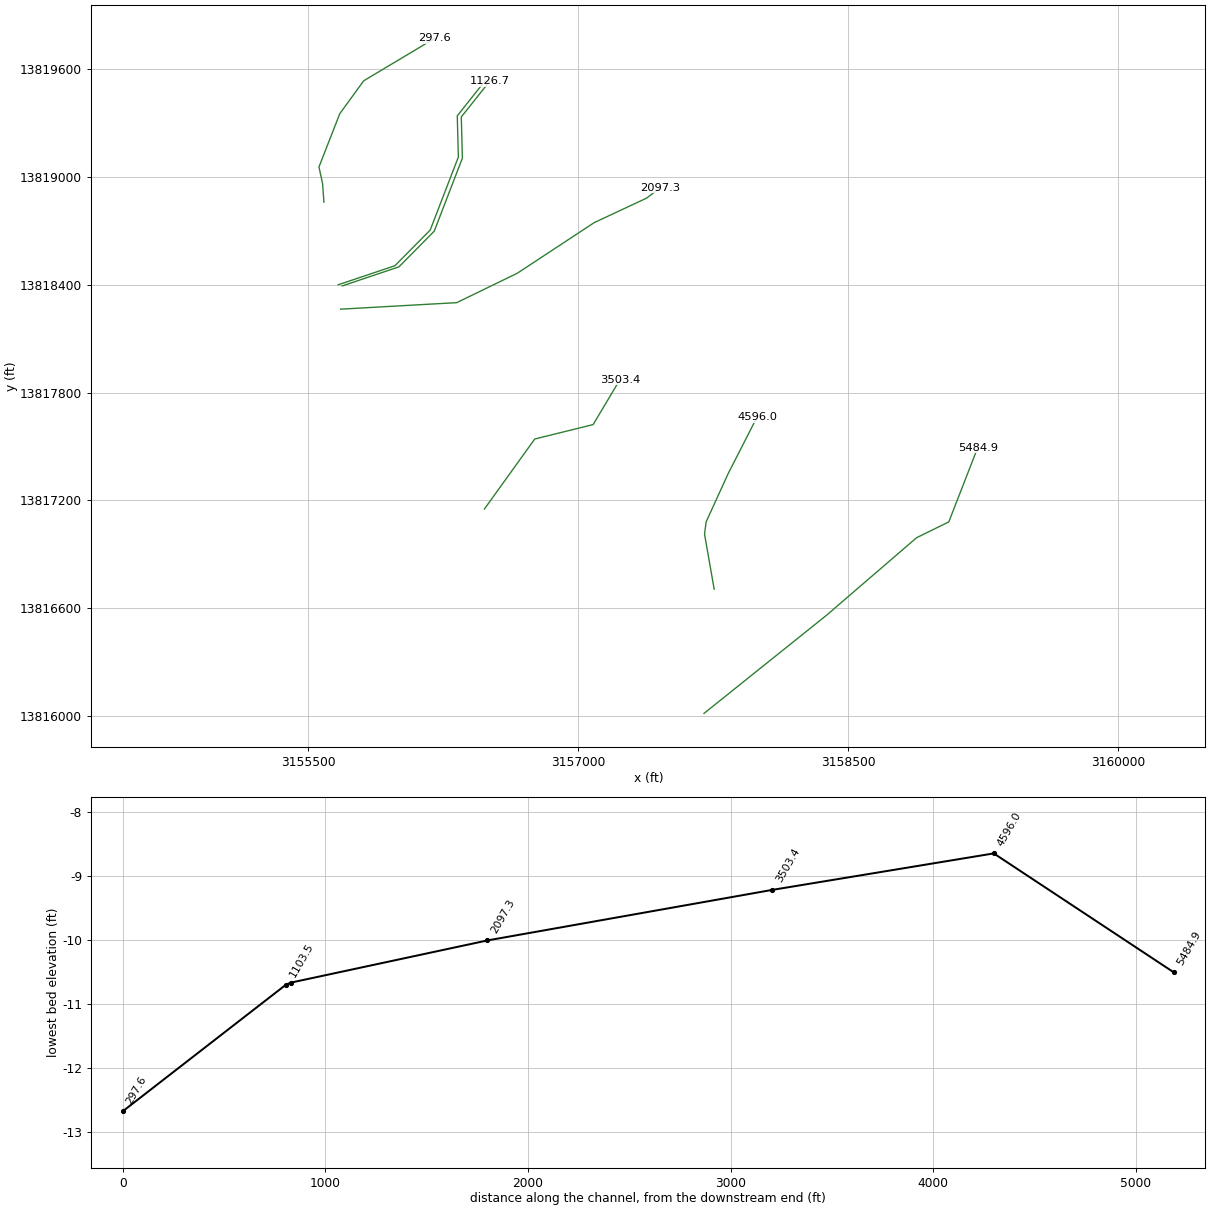
HEC-RAS study C106-00-00.PRJ: C106-00-00 2015

--- C106-00-00.g01 (geometry) --- (continued)

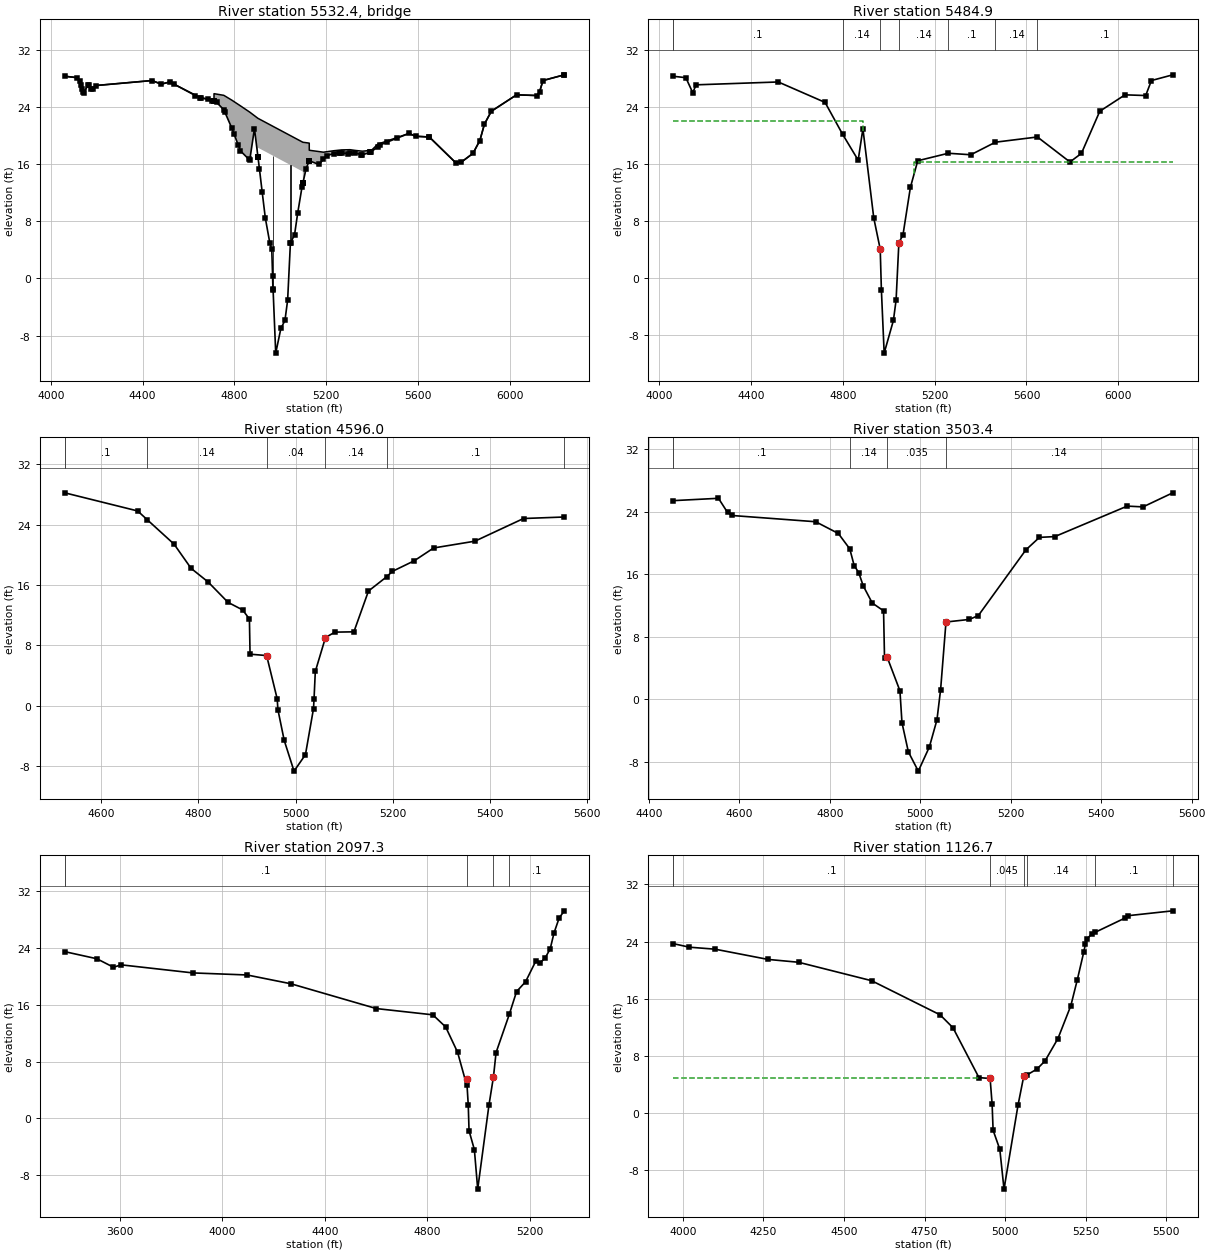
Type RM Length L Ch R = 3 ,5532.4  ,,,
BEGIN DESCRIPTION:
HOWARD DRIVE
Structure ID: C06-2
END DESCRIPTION:
Node Name=HOWARD DRIVE
Bridge Culvert--1,0,-1,-1, 0
Deck Dist Width WeirC Skew NumUp NumDn MinLoCord MaxHiCord MaxSubmerge Is_Ogee
10,75,2.6,0, 60, 60, , , 0.95, 0, 1,1,,
  4061.1  4116.1  4126.1  4136.1  4141.1  4146.1  4161.1  4166.1  4176.1  4186.1
  4196.1  4441.1  4481.1  4518.8  4652.1  4684.4  4702.8 4711.19  4711.3  4722.6
    4754  4789.1  4826.3  4866.9  4887.5 4902.61  4902.7 5098.39  5098.5  5112.5
  5126.2 5126.31  5126.4    5168  5187.9  5203.2  5232.1  5266.8  5303.5  5326.3
  5357.6  5392.4  5397.2    5425    5436    5561  5589.1  5649.1  5764.1  5789.4
  5839.4  5869.4  5889.4  5919.4  6029.4  6119.4  6129.4  6144.4  6237.2  6237.3
    28.3    28.1    27.6    26.5    26.1      26    27.1    27.1    26.5    26.5
      27    27.7    27.2    27.5    25.3   25.11   24.91   24.86   25.86    25.8
   25.63   24.95   24.16   23.28   22.78   22.41   22.41   19.06   19.06      19
   18.94   17.94   17.94   17.76   17.67   17.74   17.87   17.99   18.02   17.92
   17.81   17.92   17.93    18.8   18.92    20.3    19.9    19.8    16.2    16.3
    17.5    19.3    21.6    23.4    25.7    25.6    26.1    27.7    28.5    28.5
    28.3    28.1    27.6    26.5    26.1      26    27.1    27.1    26.5    26.5
      27    27.7    27.2    27.5   25.27    25.1   24.88   24.78   24.78   24.64
   23.61   21.02   17.86   16.55   20.96   17.03    18.3   14.95   13.34   15.37
   16.45   16.46   16.47   15.95   16.66    17.2   17.46   17.54   17.49   17.53
   17.31   17.64   17.76   18.43    18.7    20.3    19.9    19.8    16.2    16.3
    17.5    19.3    21.6    23.4    25.7    25.6    26.1    27.7    28.5    28.5
  4061.1  4116.1  4126.1  4136.1  4141.1  4146.1  4161.1  4166.1  4176.1  4186.1
  4196.1  4441.1  4481.1  4518.8  4652.1  4684.4  4702.8 4711.19  4711.3  4722.6
    4754  4789.1  4826.3  4866.9  4887.5 4902.61  4902.7 5098.39  5098.5  5112.5
  5126.2 5126.31  5126.4    5168  5187.9  5203.2  5232.1  5266.8  5303.5  5326.3
  5357.6  5392.4  5397.2    5425    5436    5561  5589.1  5649.1  5764.1  5789.4
  5839.4  5869.4  5889.4  5919.4  6029.4  6119.4  6129.4  6144.4  6237.2  6237.3
    28.3    28.1    27.6    26.5    26.1      26    27.1    27.1    26.5    26.5
      27    27.7    27.2    27.5    25.3   25.11   24.91   24.86   25.86    25.8
   25.63   24.95   24.16   23.28   22.78   22.41   22.41   19.06   19.06      19
   18.94   17.94   17.94   17.76   17.67   17.74   17.87   17.99   18.02   17.92
   17.81   17.92   17.93    18.8   18.92    20.3    19.9    19.8    16.2    16.3
    17.5    19.3    21.6    23.4    25.7    25.6    26.1    27.7    28.5    28.5
   28.24   28.04   27.54   26.44   26.04   25.94   27.04   27.04   26.44   26.44
   26.94   27.64   27.14   27.44   25.21   25.04   24.82   24.72   24.72   24.58
   23.55   20.96    17.8   16.49    20.9   16.97   18.24   14.89   13.28   15.31
   16.39    16.4   16.41   15.89    16.6   17.14    17.4   17.48   17.43   17.47
   17.25   17.58    17.7   18.37   18.64   20.24   19.84   19.74   16.14   16.24
   17.44   19.24   21.54   23.34   25.64   25.54   26.04   27.64   28.44   28.44
Pier Skew, UpSta & Num, DnSta & Num=  ,4968.6, 2 ,4968.6, 2 , 0 , 0 , 0 ,,
     3.5     3.5
   -3.88    18.2
     3.5     3.5
   -3.94   18.14
Pier Skew, UpSta & Num, DnSta & Num=  ,5045, 2 ,5045, 2 , 0 , 0 , 0 ,,
     3.5     3.5
    3.38    16.9
     3.5     3.5
    3.32   16.84
BR Coef= 1 , 1 , 0 ,1.25, 0 ,,,0.8,0,2,0,
WSPro=,,,, 1 ,,,, 0 ,,,, 0 ,,,,-1 ,-1 ,-1 , 0 , 0 , 0 , 0 , 0
BR U #Sta/Elev= 99
  4061.1    28.3  4116.1    28.1  4126.1    27.6  4131.1    27.1  4136.1    26.5
  4141.1    26.1  4146.1      26  4161.1    27.1  4166.1    27.1  4176.1    26.5
  4186.1    26.5  4196.1      27  4441.1    27.7  4481.1    27.2  4518.8    27.5
  4538.1   27.17  4630.1    25.6  4652.1   25.27  4652.9   25.26  4684.4    25.1
  4702.8   24.88 4711.19   24.78  4711.3   24.78 4711.41   24.77  4722.6   24.64
    4754   23.61  4758.6   23.27  4789.1   21.02    4799   20.18  4816.6   18.68
  4826.3   17.86  4863.5   16.66  4866.9   16.55  4887.5   20.96  4902.5   17.06
 4902.61   17.03  4902.7   17.01  4902.8   16.98  4909.2   15.32  4920.9   12.16
  4934.8    8.46  4954.6    4.93  4962.9    4.09  4966.5      .3    4968   -1.62
  4968.6   -1.52  4980.1  -10.46  5002.7   -6.99  5020.3   -5.89    5032   -3.05
  5044.2    5.01    5045    5.01    5062    6.08  5075.7    9.12  5094.4   12.75
  5098.3   13.31 5098.39   13.33  5098.5   13.34  5098.6   13.36  5112.5   15.37
 5126.09   16.45  5126.2   16.45 5126.31   16.46  5126.4   16.47    5168   15.95
  5187.9   16.66  5203.2    17.2  5232.1   17.46  5256.7   17.52  5259.4   17.52
  5266.8   17.54  5295.5   17.47  5303.5   17.49  5326.3   17.53  5353.7   17.34
  5357.6   17.31  5392.3   17.64  5392.4   17.64  5397.2   17.76    5425   18.43
    5436    18.7  5464.9   19.07  5506.8   19.61    5561    20.3  5589.1    19.9
  5647.7    19.8  5649.1    19.8  5764.1    16.2  5789.4    16.3  5839.4    17.5
  5869.4    19.3  5889.4    21.6  5919.4    23.4  6029.4    25.7  6119.4    25.6
  6129.4    26.1  6144.4    27.7  6237.2    28.5  6237.3    28.5
BR U #Mann= 8
  4061.1      .2  4061.1      .1    4799     .14  4962.9     .04  5044.2     .14
  5259.4      .1  5464.9     .14  5647.7      .1
BR U Banks=4962.9,5044.2
BR D #Sta/Elev= 99
  4061.1   28.24  4116.1   28.04  4126.1   27.54  4131.1   27.04  4136.1   26.44
  4141.1   26.04  4146.1   25.94  4161.1   27.04  4166.1   27.04  4176.1   26.44
  4186.1   26.44  4196.1   26.94  4441.1   27.64  4481.1   27.14  4518.8   27.44
  4538.1   27.11  4630.1   25.54  4652.1   25.21  4652.9    25.2  4684.4   25.04
  4702.8   24.82 4711.19   24.72  4711.3   24.72 4711.41   24.71  4722.6   24.58
    4754   23.55  4758.6   23.21  4789.1   20.96    4799   20.12  4816.6   18.62
  4826.3    17.8  4863.5    16.6  4866.9   16.49  4887.5    20.9  4902.5      17
 4902.61   16.97  4902.7   16.95  4902.8   16.92  4909.2   15.26  4920.9    12.1
  4934.8     8.4  4954.6    4.87  4962.9    4.03  4966.5     .24    4968   -1.68
  4968.6   -1.58  4980.1  -10.52  5002.7   -7.05  5020.3   -5.95    5032   -3.11
  5044.2    4.95    5045    4.95    5062    6.02  5075.7    9.06  5094.4   12.69
  5098.3   13.25 5098.39   13.27  5098.5   13.28  5098.6    13.3  5112.5   15.31
 5126.09   16.39  5126.2   16.39 5126.31    16.4  5126.4   16.41    5168   15.89
  5187.9    16.6  5203.2   17.14  5232.1    17.4  5256.7   17.46  5259.4   17.46
  5266.8   17.48  5295.5   17.41  5303.5   17.43  5326.3   17.47  5353.7   17.28
  5357.6   17.25  5392.3   17.58  5392.4   17.58  5397.2    17.7    5425   18.37
    5436   18.64  5464.9   19.01  5506.8   19.55    5561   20.24  5589.1   19.84
  5647.7   19.74  5649.1   19.74  5764.1   16.14  5789.4   16.24  5839.4   17.44
  5869.4   19.24  5889.4   21.54  5919.4   23.34  6029.4   25.64  6119.4   25.54
  6129.4   26.04  6144.4   27.64  6237.2   28.44  6237.3   28.44
BR D #Mann= 8
  4061.1      .2  4061.1      .1    4799     .14  4962.9     .04  5044.2     .14
  5259.4      .1  5464.9     .14  5647.7      .1
BR D Banks=4962.9,5044.2
BC Design=,, 0 ,, 0 ,,,,,,
BC HTab HWMax=28.66
BC Use User HTab Curves=0
BC User HTab FreeFlow(D)= 0

Type RM Length L Ch R = 1 ,5484.9  ,790.2,888.9,946.8
BEGIN DESCRIPTION:
Downstream Section of Bridge/Culvert/Weir
END DESCRIPTION:
XS GIS Cut Line= 6
      3157698.56     13816014.51      3158387.24     13816567.25
      3158426.29     13816601.59      3158878.85     13816991.94
      3159057.83      13817080.1      3159218.62     13817493.94
#Sta/Elev= 30
  4061.1   28.26  4116.1   28.06  4146.1   25.96  4161.1   27.06  4518.8   27.46
  4722.6    24.6    4799   20.14  4866.9   16.51  4887.5   20.92  4934.8    8.42
  4962.9    4.05    4968   -1.66  4980.1   -10.5  5020.3   -5.93    5032   -3.09
  5044.2    4.97    5062    6.04  5094.4   12.71  5126.4   16.43  5259.4   17.48
  5357.6   17.27  5464.9   19.03  5647.7   19.76  5789.4   16.26  5839.4   17.46
  5919.4   23.36  6029.4   25.66  6119.4   25.56  6144.4   27.66  6237.3   28.46
#Mann= 8 , 1 , 0
  4061.1      .2       0  4061.1      .1       0    4799     .14       0
  4962.9     .04       0  5044.2     .14       0  5259.4      .1       0
  5464.9     .14       0  5647.7      .1       0
#XS Ineff= 2 , 0
       0    4890      22    5110       0    16.2
Permanent Ineff=
       F       F
Bank Sta=4962.9,5044.2
XS Rating Curve= 0 ,0
Exp/Cntr=0.5,0.3

Type RM Length L Ch R = 1 ,4596.0  ,1232.1,1092.6,1001.7
BEGIN DESCRIPTION:
Cross Section 4596.0
END DESCRIPTION:
XS GIS Cut Line= 5
      3157754.96     13816705.66      3157701.42     13817012.01
      3157710.34     13817080.42      3157832.29      13817348.1
       3157992.9     13817663.38
#Sta/Elev= 30
  4524.9    28.2  4674.9    25.8  4694.6   24.64  4749.9    21.4  4784.9    18.2
  4819.9    16.4  4860.9    13.7  4890.9    12.7  4904.9    11.5  4906.2    6.84
  4940.3    6.66  4962.1     .92  4963.5    -.49  4976.5   -4.57  4996.7   -8.64
  5020.2   -6.46  5036.8    -.36  5037.9     .94  5040.5    4.55  5061.4    9.04
  5080.8    9.76  5119.9     9.8  5149.9    15.2  5187.4   17.09    5199    17.8
    5244    19.2    5284    20.9    5369    21.8    5469    24.8  5552.9      25
#Mann= 7 , 1 , 0
  4524.9      .2       0  4524.9      .1       0  4694.6     .14       0
  4940.3     .04       0  5061.4     .14       0  5187.4      .1       0
  5552.9      .2       0
Bank Sta=4940.3,5061.4
XS Rating Curve= 0 ,0
Exp/Cntr=0.3,0.1

Type RM Length L Ch R = 1 ,3503.4  ,1238,1406.1,1489.2
BEGIN DESCRIPTION:
Cross Section 3503.4
END DESCRIPTION:
XS GIS Cut Line= 4
      3156478.99      13817151.8      3156758.57     13817541.43
      3157082.77     13817621.74      3157231.48     13817871.58
#Sta/Elev= 30
  4453.9    25.4  4553.9    25.7  4573.9    23.9  4583.9    23.5  4768.9    22.7
  4818.9    21.2  4844.2   19.23  4853.9    17.1  4863.9    16.2  4873.9    14.5
  4893.9    12.3  4918.9    11.3    4921    5.31  4926.8    5.38  4955.1    1.07
  4959.6   -3.01  4973.7   -6.74  4995.7   -9.21  5020.2   -6.11  5036.9   -2.66
    5045    1.21  5056.9    9.87  5108.5    10.2  5128.5    10.7  5233.5    19.1
  5263.5    20.7  5297.5    20.8  5457.5    24.7  5492.5    24.6  5558.2    26.4
#Mann= 5 , 1 , 0
  4453.9      .2       0  4453.9      .1       0  4844.2     .14       0
  4926.8    .035       0  5056.9     .14       0
Bank Sta=4926.8,5056.9
XS Rating Curve= 0 ,0
Exp/Cntr=0.3,0.1

Type RM Length L Ch R = 1 ,2097.3  ,760.5,970.6,1062.4
BEGIN DESCRIPTION:
Cross Section 2097.3-Interpolated
END DESCRIPTION:
XS GIS Cut Line= 6
      3155680.24     13818263.96      3156325.31      13818300.3
      3156661.47     13818463.84      3157088.49     13818745.49
      3157379.22     13818881.77      3157454.81     13818939.36
#Sta/Elev= 30
  3386.4    23.5  3511.4    22.5  3576.4    21.3  3606.4   21.64  3886.4    20.5
  4097.5   20.21  4268.2   18.97  4601.6   15.47  4821.6   14.59  4871.6   12.88
  4918.1    9.31  4953.1    4.74 4953.47    5.49 4959.67    1.91 4962.77   -1.76
 4983.57   -4.43 4996.57     -10 5040.27    1.81 5058.07    5.86  5068.1    9.26
  5119.6   14.64  5148.1   17.87  5183.1   19.25  5223.1   22.17  5239.2   21.91
  5259.2   22.59  5279.2   23.89  5294.2   26.15  5314.2   28.25  5334.2   29.26
#Mann= 5 , 1 , 0
  3386.4      .2       0  3386.4      .1       0 4953.47    .045       0
 5058.07     .14       0  5119.6      .1       0
Bank Sta=4953.47,5058.07
XS Rating Curve= 0 ,0
Exp/Cntr=0.5,0.3

Type RM Length L Ch R = 1 ,1126.7  ,23.2,23.2,23.2
BEGIN DESCRIPTION:
Upstream Section of Bridge/Culvert/Weir
END DESCRIPTION:
XS GIS Cut Line= 6
      3155688.97     13818393.28      3156004.18     13818499.41
      3156200.31     13818698.03      3156356.61     13819104.33
      3156350.61     13819333.61      3156507.16     13819531.18
#Sta/Elev= 30
  3970.3   23.71  4020.3   23.21  4100.3   22.93  4264.1    21.5  4359.1    21.1
  4585.7   18.52  4798.3   13.74  4838.3   11.93 4918.87    4.95 4953.47    4.83
 4959.67    1.25 4962.77   -2.42 4983.57   -5.09 4996.57  -10.66 5040.27    1.15
 5058.07     5.2  5066.8     5.3  5098.9    6.15  5123.9    7.29  5163.9   10.42
  5203.9   15.02  5223.9   18.63  5243.9    22.5  5248.9   23.59  5253.9   24.35
  5268.9   25.08  5279.3   25.29  5371.5   27.28  5381.5   27.62  5520.1    28.3
#Mann= 7 , 1 , 0
  3970.3      .2       0  3970.3      .1       0 4953.47    .045       0
 5058.07      .1       0  5066.8     .14       0  5279.3      .1       0
  5520.1      .2       0
#XS Ineff= 2 , 0
       0  4920.6    4.95  5087.6       0     5.8
Permanent Ineff=
       F       F
Bank Sta=4953.47,5058.07
XS Rating Curve= 0 ,0
Exp/Cntr=0.5,0.3

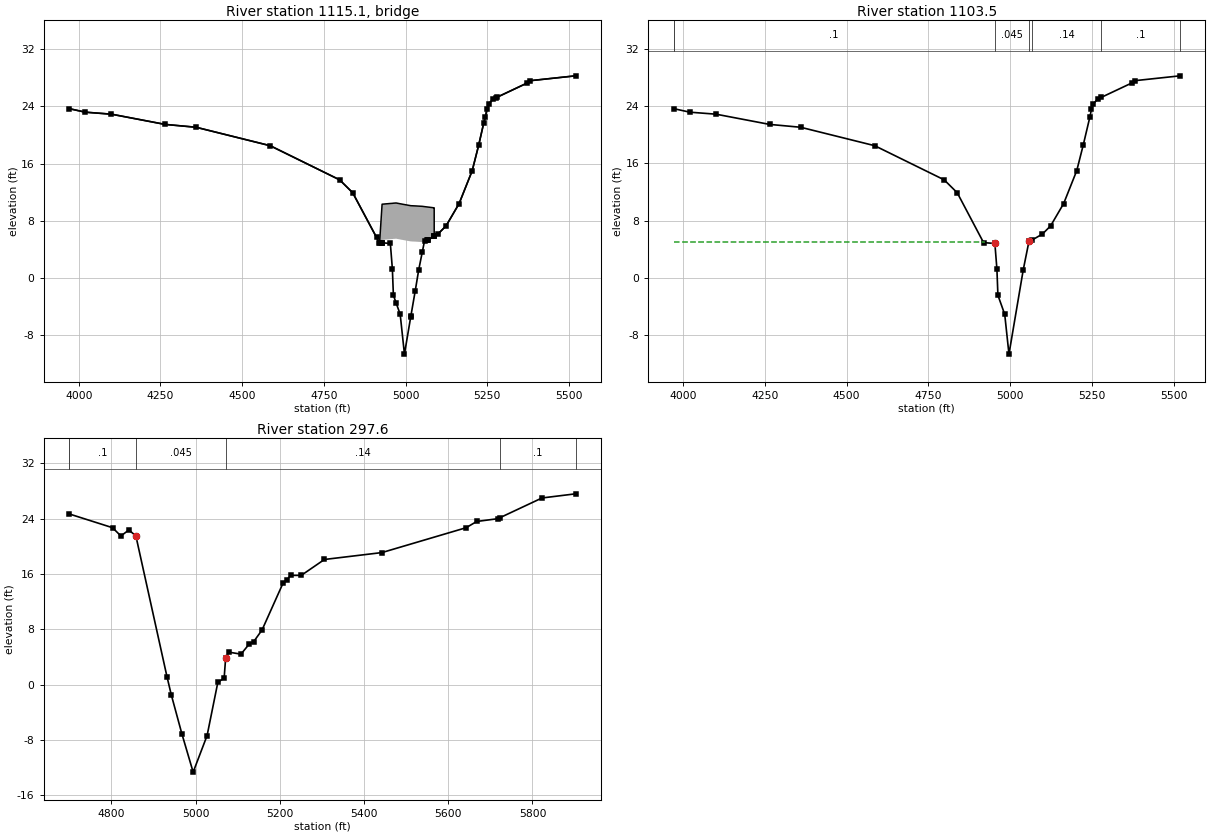
Type RM Length L Ch R = 3 ,1115.1  ,,,
BEGIN DESCRIPTION:
38" PIPELINE
END DESCRIPTION:
Bridge Culvert--1,0,-1,-1, 0
Deck Dist Width WeirC Skew NumUp NumDn MinLoCord MaxHiCord MaxSubmerge Is_Ogee
10,3.2,2.6,0, 47, 47, , , 0.95, 0, 1,1,,
  3970.3  4020.3  4100.3  4264.1  4359.1  4585.7  4798.3  4838.3  4911.3 4918.87
 4920.57 4928.17 4928.28 4928.37 4953.47 4959.67 4962.77 4971.07 4983.57 4996.57
 5015.97 5016.07 5029.67 5040.27 5051.47 5058.07  5066.8 5068.57 5068.67 5087.46
 5087.57 5087.67  5098.9  5123.9  5163.9  5203.9  5223.9  5238.9  5243.9  5248.9
  5253.9  5268.9  5276.5  5279.3  5371.5  5381.5  5520.1
    23.7    23.2   22.92   21.49   21.09   18.51   13.73   11.92    5.66    4.94
    4.95   10.32   10.32   10.32   10.42   10.44   10.46   10.49   10.38   10.27
   10.11   10.11   10.08   10.05   10.02    9.98    9.93    9.92    9.92    9.81
    9.81    5.83    6.14    7.28   10.41   15.01   18.62   21.64   22.49   23.58
   24.34   25.07   25.22   25.28   27.27   27.61   28.29
    23.7    23.2   22.92   21.49   21.09   18.51   13.73   11.92    5.66    4.94
    4.95    4.92    4.92    5.32    5.42    5.44    5.46    5.49    5.38    5.27
    5.11    5.11    5.08    5.05    5.02    5.19    5.29    5.31     5.3    5.82
    5.83    5.83    6.14    7.28   10.41   15.01   18.62   21.64   22.49   23.58
   24.34   25.07   25.22   25.28   27.27   27.61   28.29
  3970.3  4020.3  4100.3  4264.1  4359.1  4585.7  4798.3  4838.3  4911.3 4918.87
 4920.57 4928.17 4928.28 4928.37 4953.47 4959.67 4962.77 4971.07 4983.57 4996.57
 5015.97 5016.07 5029.67 5040.27 5051.47 5058.07  5066.8 5068.57 5068.67 5087.46
 5087.57 5087.67  5098.9  5123.9  5163.9  5203.9  5223.9  5238.9  5243.9  5248.9
  5253.9  5268.9  5276.5  5279.3  5371.5  5381.5  5520.1
    23.7    23.2   22.92   21.49   21.09   18.51   13.73   11.92    5.66    4.94
    4.95   10.32   10.32   10.32   10.42   10.44   10.46   10.49   10.38   10.27
   10.11   10.11   10.08   10.05   10.02    9.98    9.93    9.92    9.92    9.81
    9.81    5.83    6.14    7.28   10.41   15.01   18.62   21.64   22.49   23.58
   24.34   25.07   25.22   25.28   27.27   27.61   28.29
    23.7    23.2   22.92   21.49   21.09   18.51   13.73   11.92    5.66    4.94
    4.95    4.92    4.92    5.32    5.42    5.44    5.46    5.49    5.38    5.27
    5.11    5.11    5.08    5.05    5.02    5.19    5.29    5.31     5.3    5.82
    5.83    5.83    6.14    7.28   10.41   15.01   18.62   21.64   22.49   23.58
   24.34   25.07   25.22   25.28   27.27   27.61   28.29
BR Coef= 1 , 1 , 0 ,1.25, 0 ,,,0.8,0,2,0,
WSPro=,,,, 1 ,,,, 0 ,,,, 0 ,,,,-1 ,-1 ,-1 , 0 , 0 , 0 , 0 , 0
BR U #Sta/Elev= 47
  3970.3    23.7  4020.3    23.2  4100.3   22.92  4264.1   21.49  4359.1   21.09
  4585.7   18.51  4798.3   13.73  4838.3   11.92  4911.3    5.66 4918.87    4.94
 4920.57    4.95 4928.17    4.92 4928.28    4.92 4928.37    4.92 4953.47    4.82
 4959.67    1.24 4962.77   -2.43 4971.07    -3.5 4983.57    -5.1 4996.57  -10.67
 5015.97   -5.41 5016.07   -5.38 5029.67   -1.79 5040.27    1.14 5051.47    3.69
 5058.07    5.19  5066.8    5.29 5068.57    5.31 5068.67     5.3 5087.46    5.82
 5087.57    5.83 5087.67    5.83  5098.9    6.14  5123.9    7.28  5163.9   10.41
  5203.9   15.01  5223.9   18.62  5238.9   21.64  5243.9   22.49  5248.9   23.58
  5253.9   24.34  5268.9   25.07  5276.5   25.22  5279.3   25.28  5371.5   27.27
  5381.5   27.61  5520.1   28.29
BR U #Mann= 7
  3970.3      .2  3970.3      .1 4953.47    .045 5058.07      .1  5066.8     .14
  5279.3      .1  5520.1      .2
BR U Banks=4953.47,5058.07
BR D #Sta/Elev= 47
  3970.3    23.7  4020.3    23.2  4100.3   22.92  4264.1   21.49  4359.1   21.09
  4585.7   18.51  4798.3   13.73  4838.3   11.92  4911.3    5.66 4918.87    4.94
 4920.57    4.95 4928.17    4.92 4928.28    4.92 4928.37    4.92 4953.47    4.82
 4959.67    1.24 4962.77   -2.43 4971.07    -3.5 4983.57    -5.1 4996.57  -10.67
 5015.97   -5.41 5016.07   -5.38 5029.67   -1.79 5040.27    1.14 5051.47    3.69
 5058.07    5.19  5066.8    5.29 5068.57    5.31 5068.67     5.3 5087.46    5.82
 5087.57    5.83 5087.67    5.83  5098.9    6.14  5123.9    7.28  5163.9   10.41
  5203.9   15.01  5223.9   18.62  5238.9   21.64  5243.9   22.49  5248.9   23.58
  5253.9   24.34  5268.9   25.07  5276.5   25.22  5279.3   25.28  5371.5   27.27
  5381.5   27.61  5520.1   28.29
BR D #Mann= 7
  3970.3      .2  3970.3      .1 4953.47    .045 5058.07      .1  5066.8     .14
  5279.3      .1  5520.1      .2
BR D Banks=4953.47,5058.07
BC Design=,, 0 ,, 0 ,,,,,,
BC HTab HWMax=28.3
BC Use User HTab Curves=0
BC User HTab FreeFlow(D)= 0

Type RM Length L Ch R = 1 ,1103.5  ,676.5,805.9,707.2
BEGIN DESCRIPTION:
Downstream Section of Bridge/Culvert/Weir
END DESCRIPTION:
XS GIS Cut Line= 6
      3155666.66     13818399.62      3155981.86     13818505.75
      3156177.99     13818704.37      3156334.29     13819110.67
      3156328.29     13819339.95      3156484.84     13819537.52
#Sta/Elev= 30
  3970.3   23.68  4020.3   23.18  4100.3    22.9  4264.1   21.47  4359.1   21.07
  4585.7   18.49  4798.3   13.71  4838.3    11.9 4918.87    4.92 4953.47     4.8
 4959.67    1.22 4962.77   -2.45 4983.57   -5.12 4996.57  -10.69 5040.27    1.12
 5058.07    5.17  5066.8    5.27  5098.9    6.12  5123.9    7.26  5163.9   10.39
  5203.9   14.99  5223.9    18.6  5243.9   22.47  5248.9   23.56  5253.9   24.32
  5268.9   25.05  5279.3   25.26  5371.5   27.25  5381.5   27.59  5520.1   28.27
#Mann= 7 , 1 , 0
  3970.3      .2       0  3970.3      .1       0 4953.47    .045       0
 5058.07      .1       0  5066.8     .14       0  5279.3      .1       0
  5520.1      .2       0
#XS Ineff= 2 , 0
       0  4920.6    4.95  5087.6       0     5.8
Permanent Ineff=
       F       F
Bank Sta=4953.47,5058.07
XS Rating Curve= 0 ,0
Exp/Cntr=0.5,0.3

Type RM Length L Ch R = 1 ,297.6   ,0,0,0
BEGIN DESCRIPTION:
Cross Section 297.6
END DESCRIPTION:
XS GIS Cut Line= 6
      3155587.79     13818859.36      3155580.26     13818962.35
      3155560.16      13819055.3      3155675.72     13819351.72
      3155808.85      13819535.1      3156203.24     13819771.23
#Sta/Elev= 30
  4699.5    24.7  4802.8    22.7  4822.8    21.5  4841.6   22.37  4858.3   21.51
  4932.1    1.16  4942.2   -1.44  4967.4    -7.1  4994.3  -12.67  5027.4   -7.38
  5052.9     .32  5067.9     .94  5071.5    3.88  5079.3    4.69  5107.9     4.4
  5127.9     5.9  5137.9     6.2  5157.9     7.9  5207.9    14.7    5216    15.1
    5226    15.8    5251    15.8    5306    18.1  5442.6    19.1  5642.6    22.7
  5667.6    23.6  5717.6      24  5723.6   24.17  5822.6      27  5902.3    27.6
#Mann= 6 , 1 , 0
  4699.5      .2       0  4699.5      .1       0  4858.3    .045       0
  5071.5     .14       0  5723.6      .1       0  5902.3      .2       0
Bank Sta=4858.3,5071.5
XS Rating Curve= 0 ,0
Exp/Cntr=0.3,0.1

Chan Stop Cuts=-1
Use User Specified Reach Order=0
Composite Channel Slope=5